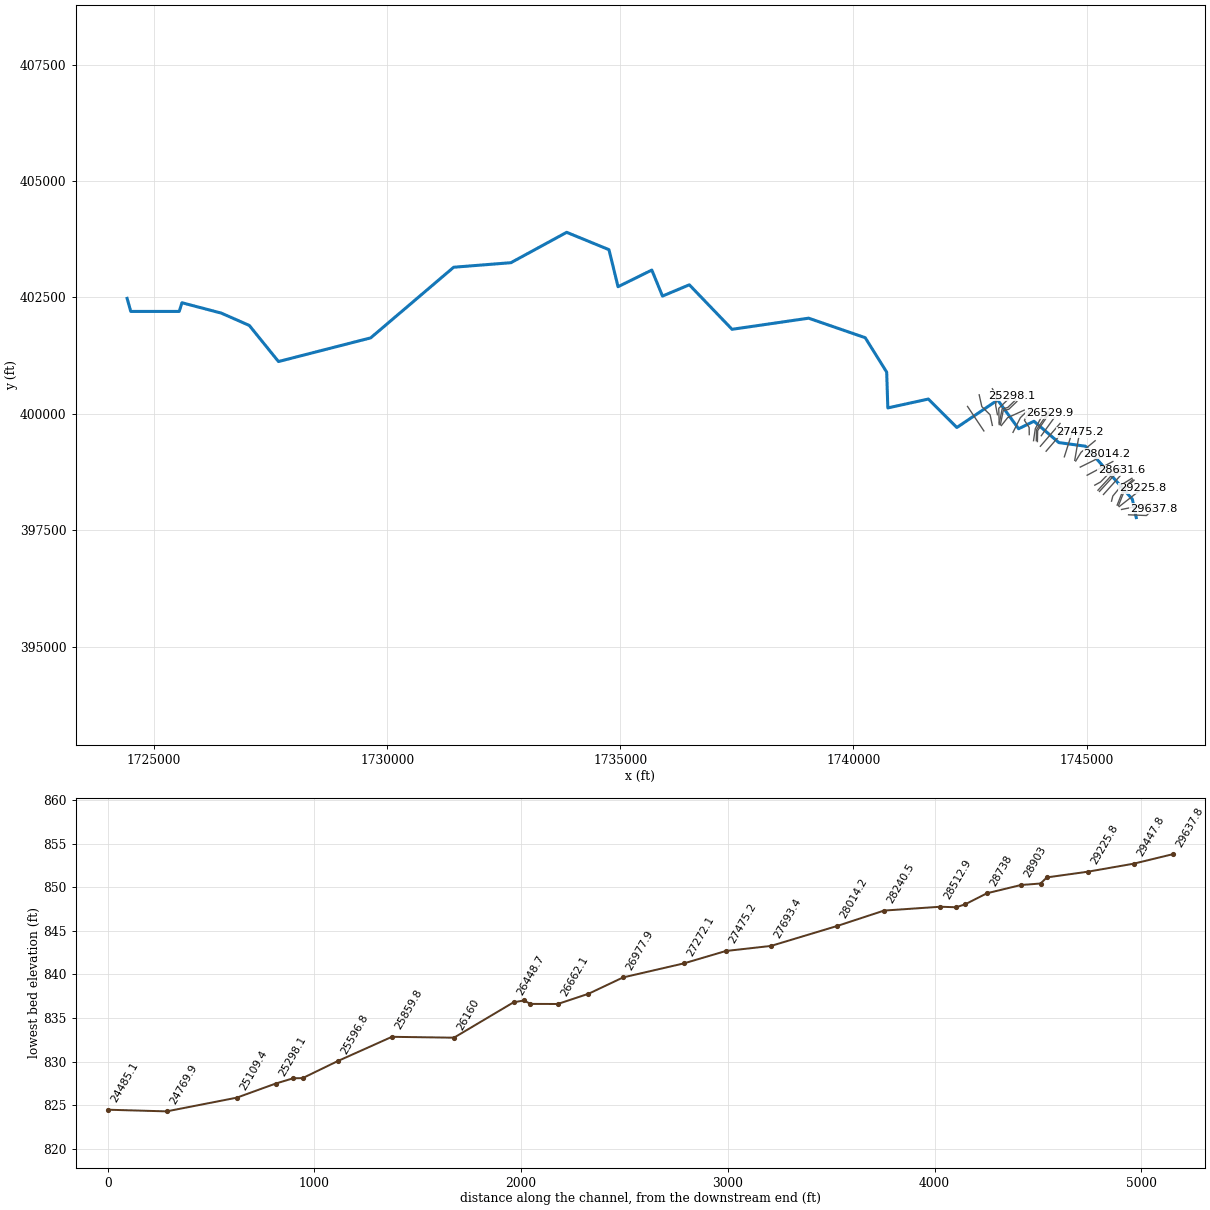
--- ROCKCK.prj (project) ---

Proj Title=ROCKCK
Current Plan=p01
Default Exp/Contr=0,0
English Units
Geom File=g01
Flow File=f01
Plan File=p01
BEGIN DESCRIPTION:
END DESCRIPTION:
DSS Export Rating Curves= 0
DSS Export Rating Curve Sorted= 0
DSS Export Volume Flow Curves= 0
DXF OffsetX= 0
DXF OffsetY= 0
DXF ScaleX= 0
DXF ScaleY= 0

--- ROCKCK.p01 (plan) ---

Plan Title=Floodplain
Program Version=4.00
Geom File=g01
Flow File=f01
K Sum by GR=0
Std Step Tol=0.01
Critical Tol=0.01
Num of Std Step Trials=20
Max Error Tol=0.3
Flow Tol Ratio=0.001
Split Flow NTrial=30
Split Flow Tol=0.02
Split Flow Ratio=0.02
Log Output Level=0
Friction Slope Method=1
Unsteady Friction Slope Method=2
Unsteady Bridges Friction Slope Method=1
Global Log Level=0
CheckData=False
Run HTab=0
Run UNet=0
Run PostProcess=0
UNET Theta=0
UNET Theta Warmup=0
UNET ZTol=0
UNET ZSATol=0
UNET MxIter=0
UNET MaxInSteps=0
UNET DtIC=0
UNET DtMin=0
UNET MaxCRTS=0
UNET WFStab=0
UNET SFStab=0
UNET WFX=0
UNET SFX=0
UNET DSS MLevel=0
UNET DZMax Abort=0
UNET Convert EG Bridges=0
UNET Use Existing IB Tables=0
UNET Froude Limit=0
UNET Froude Power=0
Write IC File=0
Echo Input=False
Echo Output=False
Write Detailed=0

--- ROCKCK.f01 (steady flow) ---

Flow Title=NFF Regression Equation
Program Version=4.10
Number of Profiles= 1
Profile Names=P100yr
River Rch & RM=ROCKCK,Main            ,29637.8
1206.035
River Rch & RM=ROCKCK,Main            ,29225.8
1397.963
River Rch & RM=ROCKCK,Main            ,26160
1433.488
River Rch & RM=ROCKCK,Main            ,25859.8
1636.754
River Rch & RM=ROCKCK,Main            ,21784.5
1776.158
River Rch & RM=ROCKCK,Main            ,17376.2
1959.889
River Rch & RM=ROCKCK,Main            ,12441.2
2156.381
River Rch & RM=ROCKCK,Main            ,8116.5
2274.908
River Rch & RM=ROCKCK,Main            ,334.1
 2505.84
River Rch & RM=ROCKCK,Main            ,198.2
2506.895
Boundary for River Rch & Prof#=ROCKCK,Main            , 1
Up Type= 0
Dn Type= 3
Dn Slope=0.00246
DSS Import GetInterval= 0
DSS Import GetPeak= 0
DSS Import FillOption= 0

--- ROCKCK.g01 (geometry) ---

Geom Title=USGS 10m DEM
Program Version=4.10

River Reach=ROCKCK          ,Main
Reach XY= 30
      1746065.56      397770.862     1745980.918      398166.902
     1744974.504      399304.306     1744405.632      399382.122
     1743870.479       399840.55      1743541.47      399679.459
     1743092.324      400296.659     1742217.513      399706.558
     1741605.501      400317.614     1740736.151      400127.171
      1740712.26      400895.361     1740251.647      401635.769
     1739037.861      402055.222     1737394.997      401816.315
     1736478.412      402772.831     1735902.577      402530.511
     1735673.909      403089.554     1734949.405      402731.193
     1734754.866      403527.574     1733847.701      403900.406
     1732650.707      403247.506     1731423.952      403150.236
     1729643.478      401632.014     1727665.871      401123.756
     1727039.719      401899.375     1726438.698      402164.598
     1725595.723      402386.887     1725536.506      402200.464
     1724497.235      402200.464     1724418.906      402480.882

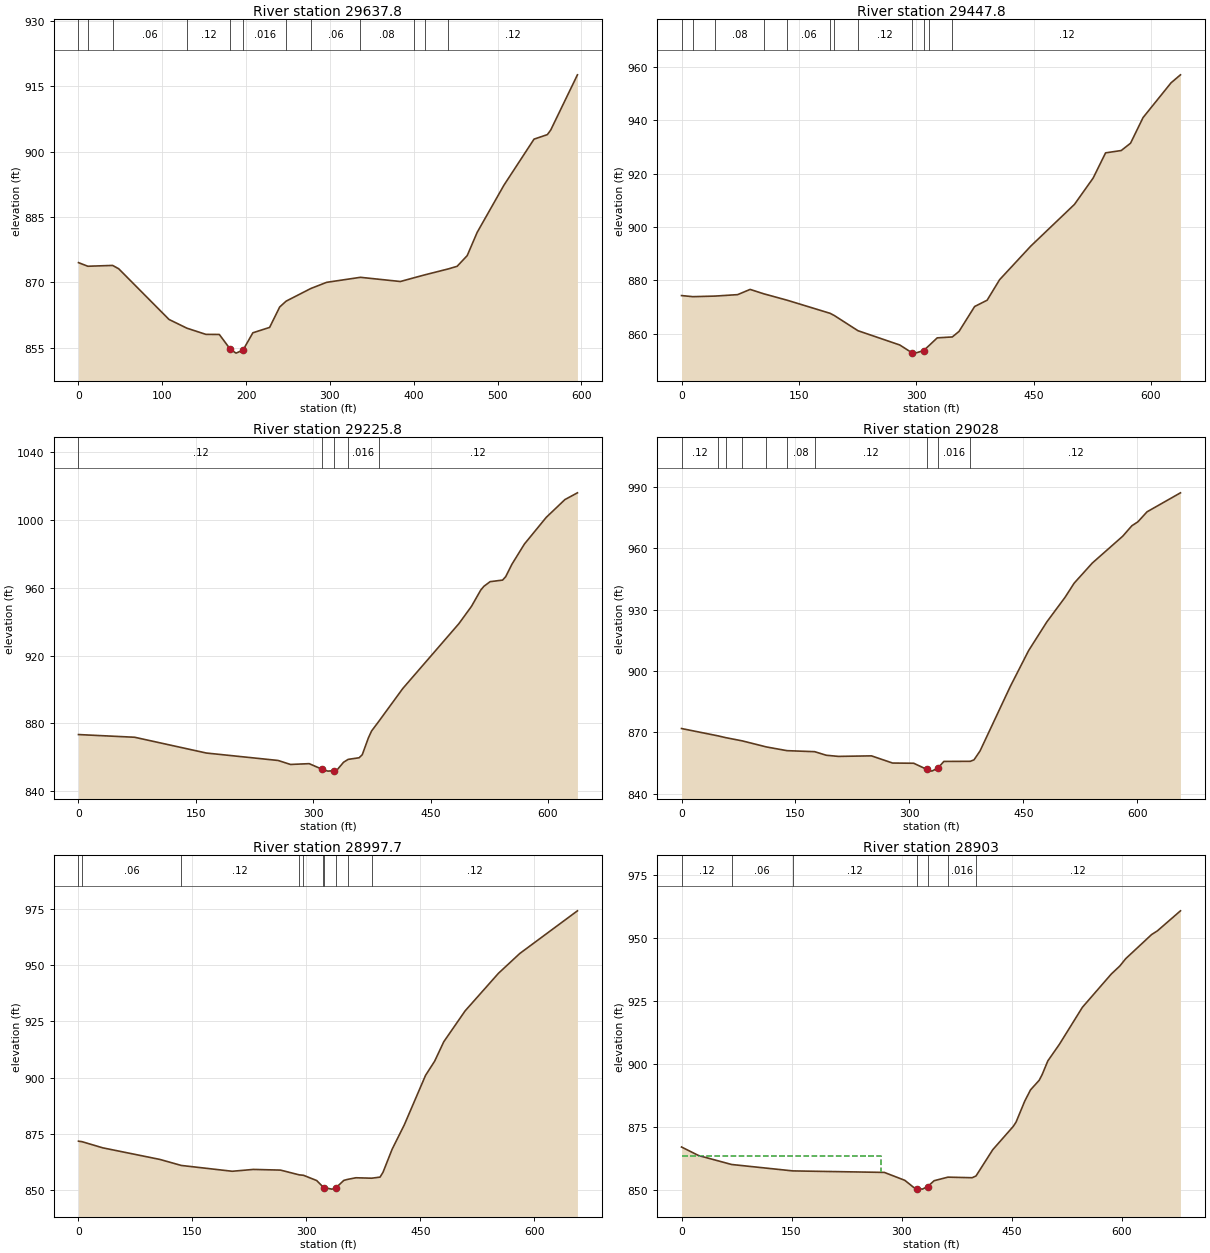
Type RM Length L Ch R = 1 ,29637.8 ,181,190,199.2
XS GIS Cut Line= 3
     1745900.995      397830.187     1746284.676      397814.562
     1746435.718      397962.131
#Sta/Elev= 30
       0  874.53   11.16873.6988   40.72873.8886      48  873.12     108   861.5
   129.4 859.495     152  858.08     168  858.06   181.3  854.62     188  853.78
   196.3  854.48     208  858.44     228  859.68     240  864.35  247.64865.6932
   277.2 868.602     296  870.01  336.32871.1612     384   870.2  399.99871.0465
  413.93871.7654  441.28873.0951   451.7  873.69   463.7  876.14   475.6  881.47
   507.5  892.28   543.4  902.84   559.3  903.88   563.3  904.92   595.2  917.59
#Mann= 12 ,-1 , 0
       0     .06       0   11.16     .08       0   40.72     .06       0
   129.4     .12       0   181.3    .045       0   196.3    .016       0
  247.64     .12       0   277.2     .06       0  336.32     .08       0
  399.99     .12       0  413.93     .08       0  441.28     .12       0
Bank Sta=181.3,196.3
XS Rating Curve= 0 ,0
Exp/Cntr=0.3,0.1

Type RM Length L Ch R = 1 ,29447.8 ,204.2,222,239.3
XS GIS Cut Line= 2
     1745750.309      397944.959     1746374.971      398073.178
#Sta/Elev= 30
       0  874.29   14.46873.8774   43.14874.0999    71.7  874.64    87.7   876.6
  104.92874.9718  135.07872.5436  190.02867.6188  195.37866.7879  225.52861.1054
     279  855.74   294.5  852.83   298.9  852.69   309.5  853.67  315.98855.4166
   326.8  858.42  346.13858.7656   354.7  860.84   374.6  870.18   390.6  872.55
   406.5  880.23   446.4  892.86   502.2   908.5   526.1  918.39     542  927.85
     562  928.72   573.9  931.47   589.9  941.09   625.7  954.14   637.7  957.13
#Mann= 12 ,-1 , 0
       0     .08       0   14.46     .06       0   43.14     .08       0
  104.92     .12       0  135.07     .06       0  190.02     .12       0
  195.37     .06       0  225.52     .12       0   294.5    .045       0
   309.5     .12       0  315.98    .016       0  346.13     .12       0
Bank Sta=294.5,309.5
XS Rating Curve= 0 ,0
Exp/Cntr=0.3,0.1

Type RM Length L Ch R = 1 ,29225.8 ,176.5,197.8,216.5
XS GIS Cut Line= 2
     1745698.975       398006.66      1746200.61      398400.366
#Sta/Elev= 30
       0  873.37    71.7  871.78   163.4  862.46   255.1  858.07     271  855.71
   294.9  856.18   311.7   852.8   318.8  851.77   326.7  852.08   330.8  852.66
   338.8  857.02  344.65858.7092   358.7  859.67   362.7  861.48   370.6   871.5
   374.6  875.48  383.64881.0466   414.5  900.58   486.2  938.88   502.2  949.05
   514.1  958.69   518.1  960.92   526.1  963.68     542   964.6     546  966.62
     554  973.99   569.9  985.88   597.8 1001.64   621.7 1012.16   637.7 1016.15
#Mann= 5 ,-1 , 0
       0     .12       0   311.7    .045       0   326.7     .12       0
  344.65    .016       0  383.64     .12       0
Bank Sta=311.7,326.7
XS Rating Curve= 0 ,0
Exp/Cntr=0.3,0.1

Type RM Length L Ch R = 1 ,29028   ,30.3,30.3,30.3
XS GIS Cut Line= 3
      1745683.95      398026.926     1745832.604      398403.445
     1746018.151      398573.801
#Sta/Elev= 30
       0  871.94   48.22868.3397   58.43867.4578   79.97865.9047  111.73862.9385
  138.86861.1222  175.24860.6248   190.5  858.88   206.4  858.32     250  858.58
   277.8  855.07   305.6  854.97   322.5  852.04   329.4  851.12   337.5  852.62
   345.3  855.86  380.16855.9191     385  856.65   392.9  860.97   432.8  892.56
   456.8     910   480.8  924.04   504.8  936.07   516.8  942.99   540.7  952.83
   580.7  965.93   592.7  971.03   600.7  972.97   612.7  977.85   656.7  987.13
#Mann= 10 ,-1 , 0
       0     .12       0   48.22     .06       0   58.43     .12       0
   79.97     .06       0  111.73     .12       0  138.86     .08       0
  175.24     .12       0   322.5    .045       0   337.5    .016       0
  380.16     .12       0
Bank Sta=322.5,337.5
XS Rating Curve= 0 ,0
Exp/Cntr=0.3,0.1

Type RM Length L Ch R = 1 ,28997.7 ,106.5,94.7,82.9
XS GIS Cut Line= 3
     1745655.738      398037.776     1745804.392      398414.296
     1745989.939      398584.652
#Sta/Elev= 30
       0  871.74     4.8871.5046    31.8  868.79   107.2  863.62  135.26860.9512
   202.4  858.36   230.2  859.18   265.9  858.88  290.59856.7578  296.12856.5745
   313.5  854.24  322.34851.2324   323.5  851.07   333.4  850.42   338.5   850.9
   349.2   854.3  354.09854.7412   365.1  855.47  385.85 855.279   396.9  855.76
   400.8  857.91   412.8  868.16   428.8  878.98   456.8  901.01   468.8  907.33
   480.8  915.96   508.8  929.64   552.7  946.37   580.7  955.16   656.7  974.16
#Mann= 10 ,-1 , 0
       0     .12       0     4.8     .06       0  135.26     .12       0
  290.59     .06       0  296.12     .12       0  322.34     .06       0
   323.5    .045       0   338.5     .06       0  354.09    .016       0
  385.85     .12       0
Bank Sta=323.5,338.5
XS Rating Curve= 0 ,0
Exp/Cntr=0.3,0.1

Type RM Length L Ch R = 1 ,28903   ,166.4,165,163.6
XS GIS Cut Line= 4
     1745535.078      398123.714     1745562.422      398233.089
     1745778.568      398494.808     1745972.578      398614.599
#Sta/Elev= 30
       0  866.98    23.3  863.59   68.24860.0363  151.76857.4876   276.5  856.89
   304.4  853.75   316.4  850.96   320.6  850.49   328.4  850.25   335.6  851.27
   344.4   853.6   363.2 855.006   396.3  854.78   401.5 855.493   424.2  865.87
   452.2  875.15   456.1  876.89   467.9   885.2   475.8  889.68   487.6  893.48
   491.5  895.65   499.4  901.19   515.1  907.75   546.5  922.47   585.8  935.66
   597.6   938.9   605.5  941.77   640.9  951.38   648.7  952.82   680.2  960.79
#Mann= 7 ,-1 , 0
       0     .12       0   68.24     .06       0  151.76     .12       0
   320.6    .045       0   335.6     .12       0   363.2    .016       0
   401.5     .12       0
#XS Ineff= 2 , 0
       0   272.5  863.57               0
Permanent Ineff=
       F       F
Bank Sta=320.6,335.6
XS Rating Curve= 0 ,0
Exp/Cntr=0.3,0.1

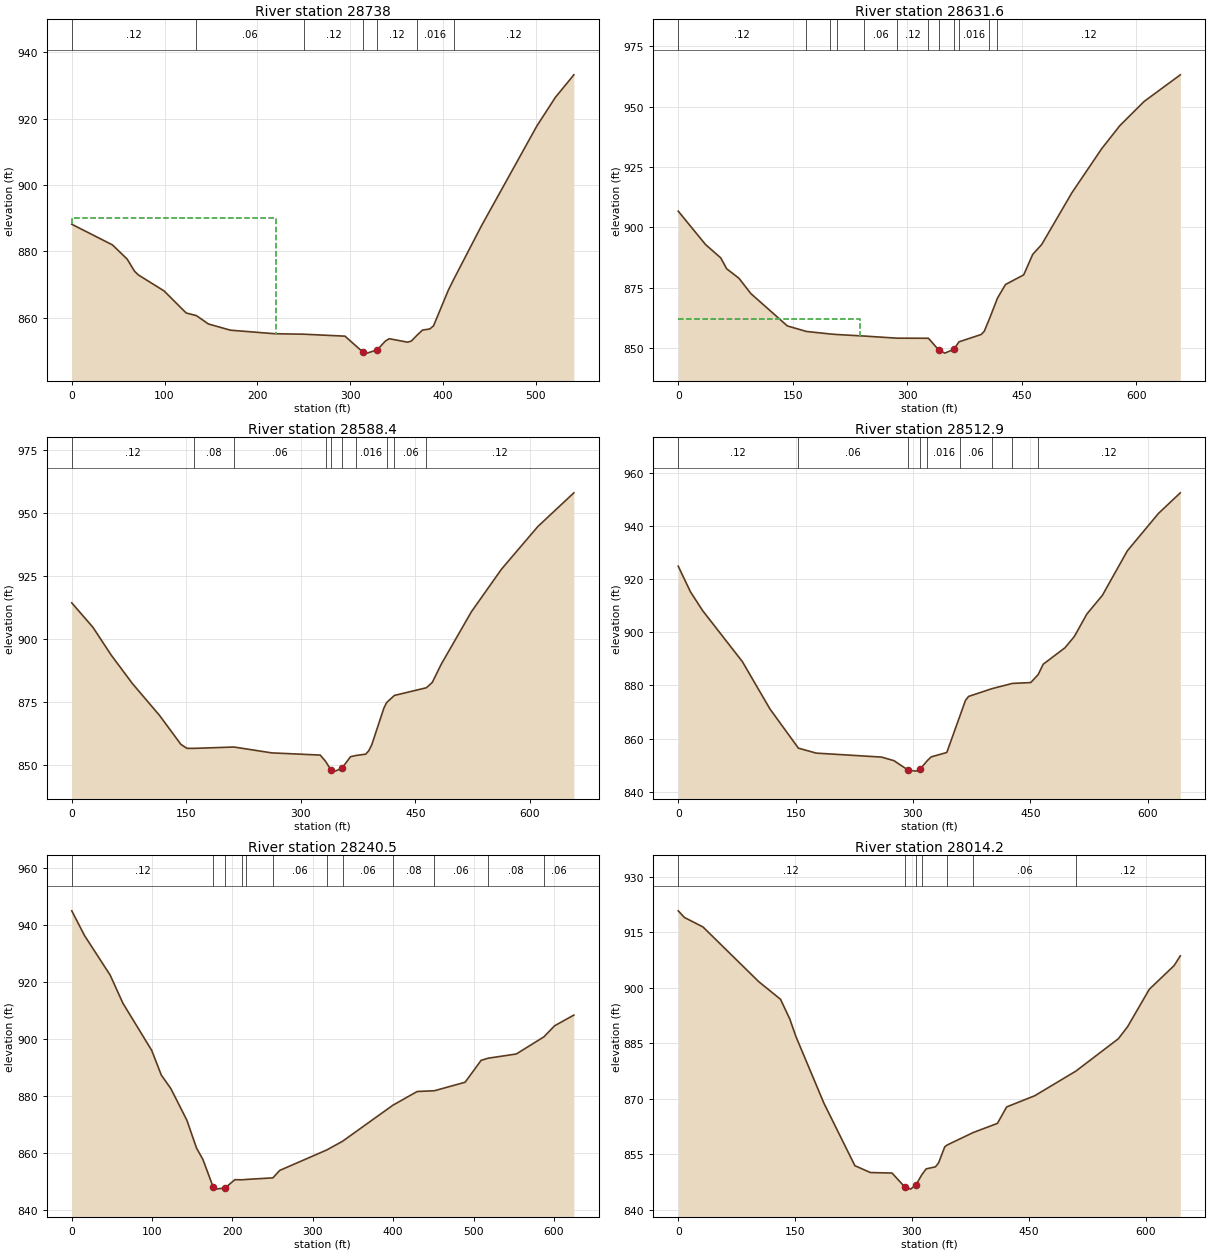
Type RM Length L Ch R = 1 ,28738   ,106.7,106.5,106.2
XS GIS Cut Line= 2
     1745361.897      398266.911     1745722.176      398670.465
#Sta/Elev= 30
       0  888.18    43.8  881.96    59.7  877.67    67.6  874.03    71.6  872.92
    99.4  868.08   123.3  861.41  134.35860.6168   147.2   858.1     171  856.22
   218.8  855.15  249.71855.0123   294.4  854.42   314.1  849.52   318.2   849.3
   329.1   850.3   338.1  852.98   342.1  853.65     362   852.6     366  852.97
  371.91854.6732   377.9  856.25   385.8  856.59   389.8  857.53   405.7  868.26
   411.5 871.528   441.5  887.73   501.2  917.85   521.1  926.46     541  933.26
#Mann= 7 ,-1 , 0
       0     .12       0  134.35     .06       0  249.71     .12       0
   314.1    .045       0   329.1     .12       0  371.91    .016       0
   411.5     .12       0
#XS Ineff= 2 , 0
       0     220     890               0
Permanent Ineff=
       F       F
Bank Sta=314.1,329.1
XS Rating Curve= 0 ,0
Exp/Cntr=0.3,0.1

Type RM Length L Ch R = 1 ,28631.6 ,42.9,43.1,42.9
XS GIS Cut Line= 3
     1745275.964       398331.83     1745580.868      398666.032
     1745743.629      398790.815
#Sta/Elev= 30
       0  906.76    35.7  892.97    55.6  887.45    63.5   882.9    79.4  879.03
    95.2  872.63   142.9  859.28  167.73856.9945  198.96855.9446  207.71855.7198
  242.78855.0978   286.6854.2053  327.65854.1694   341.3  849.26   349.2  848.02
   361.1  849.65  367.63852.6904   396.8  855.74   400.8  857.08  407.61862.2744
  418.07870.7844   428.6  876.42   452.4  880.39   464.2  888.86     476  892.97
   515.5  914.36   554.9  932.76   578.6  942.24   610.2  952.17   657.5  963.16
#Mann= 12 ,-1 , 0
       0     .12       0  167.73     .08       0  198.96     .06       0
  207.71     .08       0  242.78     .06       0   286.6     .12       0
  327.65     .08       0   341.3    .045       0   361.1     .08       0
  367.63    .016       0  407.61     .06       0  418.07     .12       0
#XS Ineff= 2 , 0
          238.13  862.14
Permanent Ineff=
       F       F
Bank Sta=341.3,361.1
XS Rating Curve= 0 ,0
Exp/Cntr=0.3,0.1

Type RM Length L Ch R = 1 ,28588.4 ,77,75.5,74.3
XS GIS Cut Line= 3
     1745243.412      398357.872     1745548.316      398692.073
     1745711.076      398816.856
#Sta/Elev= 30
       0  914.37    27.8  904.67    51.6   893.7    79.4  882.41   115.1  869.72
   142.9  858.31   150.8  856.73  159.61856.7128  212.44857.2512   261.9  854.93
   325.4  854.06  332.38851.5782   339.1   848.3   345.2   847.7   354.1  848.99
   365.1  853.42  372.36853.9106   384.9  854.42   388.9  855.75   392.9  858.18
   408.7  872.65  412.34874.8795  422.55877.6954  464.26880.7294   472.1  882.84
   483.9  890.09   523.4  910.88   562.8  927.75   610.2  944.58   657.5  957.98
#Mann= 10 ,-1 , 0
       0     .12       0  159.61     .08       0  212.44     .06       0
  332.38     .08       0   339.1    .045       0   354.1     .08       0
  372.36    .016       0  412.34     .12       0  422.55     .06       0
  464.26     .12       0
Bank Sta=339.1,354.1
XS Rating Curve= 0 ,0
Exp/Cntr=0.3,0.1

Type RM Length L Ch R = 1 ,28512.9 ,283.8,272.4,261
XS GIS Cut Line= 4
     1745175.301       398467.34     1745298.565      398535.048
     1745498.218      398739.909     1745691.328      398834.652
#Sta/Elev= 30
       0  924.81    15.6  915.18    31.2   908.1      82  888.92   117.2  871.15
  153.63856.3938   176.4  854.53   259.8  853.04   275.7   851.7   293.8  848.17
   303.5  847.76   308.8   848.4  318.59851.7705   323.4  853.12   343.3  854.77
  359.83868.3173   367.1   874.3   371.1  875.84  401.07 878.765   427.2880.7338
   450.6  881.05   460.1884.0477   466.5  887.94   494.4  894.14   506.4   898.4
   522.3   906.8   542.2  913.85   574.1  930.58   613.9  944.65   641.8  952.38
#Mann= 9 ,-1 , 0
       0     .12       0  153.63     .06       0   293.8    .045       0
   308.8     .06       0  318.59    .016       0  359.83     .06       0
  401.07     .08       0   427.2     .06       0   460.1     .12       0
Bank Sta=293.8,308.8
XS Rating Curve= 0 ,0
Exp/Cntr=0.3,0.1

Type RM Length L Ch R = 1 ,28240.5 ,227.2,226.3,225.2
XS GIS Cut Line= 2
     1745012.107      398680.882      1745563.14      398975.433
#Sta/Elev= 30
       0  944.93    15.9  936.25    47.8  922.38    63.7   912.5    99.5  895.97
   111.4  887.34   123.4  882.54   143.3  871.45   155.2  861.77   163.2  857.72
   175.9  848.11   179.1  847.32   190.9  847.75     203  850.64  211.61850.5871
  216.81850.7155   250.3 851.275   258.7  853.87  317.28861.0512  336.91864.0981
  399.56876.7384   429.8  881.56  451.25881.8304   489.5  884.81   509.4  892.49
  518.23893.2421   553.2  894.72  587.51900.7218   600.9  904.62   624.8  908.36
#Mann= 12 ,-1 , 0
       0     .12       0   175.9    .045       0   190.9     .12       0
  211.61     .06       0  216.81    .016       0   250.3     .06       0
  317.28    .016       0  336.91     .06       0  399.56     .08       0
  451.25     .06       0  518.23     .08       0  587.51     .06       0
Bank Sta=175.9,190.9
XS Rating Curve= 0 ,0
Exp/Cntr=0.3,0.1

Type RM Length L Ch R = 1 ,28014.2 ,312.4,320.8,328.8
XS GIS Cut Line= 2
     1744863.918      398855.563     1745441.665      399141.303
#Sta/Elev= 30
       0  920.86       8  919.06    31.8  916.49   103.4  901.69   131.3  896.93
   143.2  891.61   151.2   886.8     187  868.83   226.8   851.9   246.7  850.05
   274.5  849.91   290.5  846.23   298.4  845.56   305.5  846.81  312.74849.4553
   318.3  851.04   330.2  851.59   334.2  852.64   342.2  857.02  345.69857.5435
  378.64860.8656   409.8  863.35   421.7  867.81   457.6  870.82  510.44877.4808
     565  886.24   576.9   889.5   604.8  899.64   636.6  906.03   644.6  908.68
#Mann= 7 ,-1 , 0
       0     .12       0   290.5    .045       0   305.5     .12       0
  312.74    .016       0  345.69     .12       0  378.64     .06       0
  510.44     .12       0
Bank Sta=290.5,305.5
XS Rating Curve= 0 ,0
Exp/Cntr=0.3,0.1

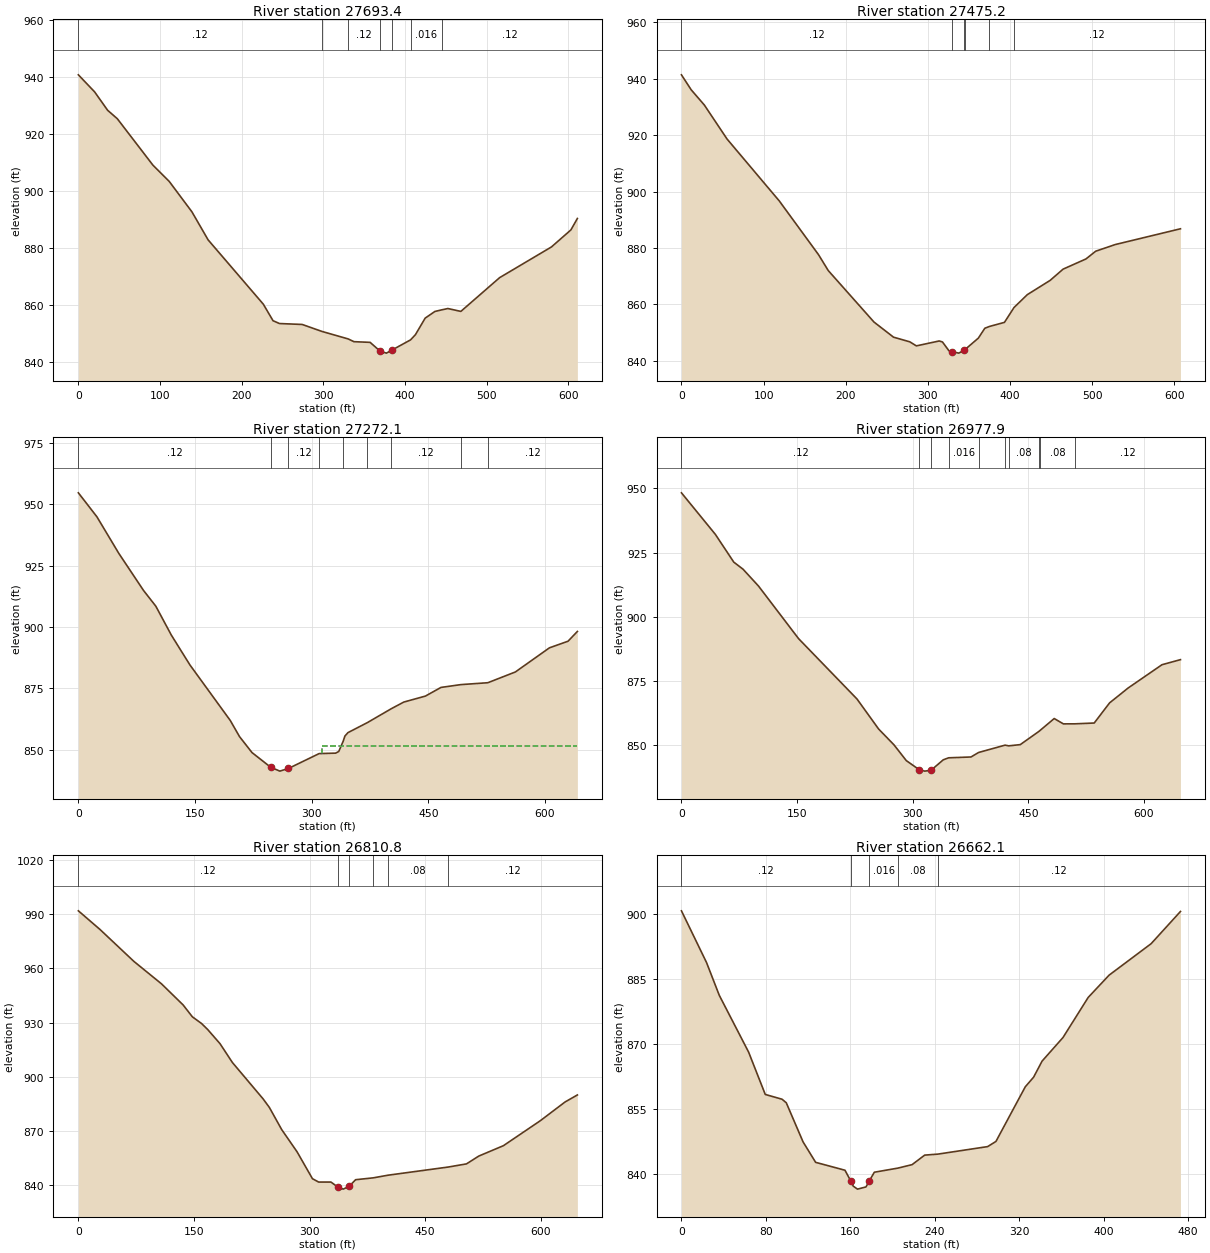
Type RM Length L Ch R = 1 ,27693.4 ,191.1,218.3,245.4
XS GIS Cut Line= 3
     1744767.066      398986.127     1744883.634      399175.673
     1745183.982      399422.201
#Sta/Elev= 30
       0  940.72    19.9  934.75    35.8  928.32    47.7  925.35    91.4  909.06
   111.3  903.39   139.1  892.73   158.9  882.93   226.5  860.41   238.4  854.62
   246.3  853.63   274.1  853.31  298.18850.8792  330.42848.2391   337.5  847.28
   357.3  847.04   369.5  843.97   377.2  843.27   384.5  844.41  406.85847.9164
   412.8  849.74   424.7  855.52   436.6  857.86  445.06858.4266   452.5  858.89
   468.4  857.88   515.9   869.7   579.4  880.46   603.2  886.42   611.1  890.42
#Mann= 7 ,-1 , 0
       0     .12       0  298.18     .06       0  330.42     .12       0
   369.5    .045       0   384.5     .12       0  406.85    .016       0
  445.06     .12       0
Bank Sta=369.5,384.5
XS Rating Curve= 0 ,0
Exp/Cntr=0.3,0.1

Type RM Length L Ch R = 1 ,27475.2 ,208.6,203.1,195
XS GIS Cut Line= 3
     1744745.968      399001.648     1744818.594      399428.509
      1744854.95      399599.286
#Sta/Elev= 30
       0  941.37    11.9  936.04    27.8  930.69    55.6  918.58   119.2  896.62
   166.8  877.64   178.8  871.95   234.4  853.72   258.2  848.35   278.1  846.69
     286  845.26   313.8     847   317.8  846.65   325.7  843.52   329.6  843.21
   337.7  842.69   344.6  843.79  345.06 843.905   361.5  848.01   369.4  851.51
  375.02852.1443   393.3   853.6  404.98858.8776   421.1  863.42   448.9  868.48
   464.7  872.47   492.5  876.08   504.4  878.83   528.2  881.19   607.6  886.78
#Mann= 6 ,-1 , 0
       0     .12       0   329.6    .045       0   344.6     .12       0
  345.06     .06       0  375.02    .016       0  404.98     .12       0
Bank Sta=329.6,344.6
XS Rating Curve= 0 ,0
Exp/Cntr=0.3,0.1

Type RM Length L Ch R = 1 ,27272.1 ,308.4,294.2,281.2
XS GIS Cut Line= 2
     1744522.839      399076.303     1744716.968      399687.826
#Sta/Elev= 30
       0  954.68    23.9  944.89    51.8  930.11    83.7  914.93    99.6  908.48
   119.6  896.67   143.5  884.52   195.3  861.92   207.2  855.34   223.2  848.85
   247.1   842.9     259  841.27   270.1  842.35  309.56848.4153   330.8   848.6
   334.8  849.28  340.55853.4906   342.7  855.56   346.7  856.97  371.54861.0309
  402.53 866.735   418.4  869.41   446.3  871.86   466.2  875.38  491.95876.5287
  526.48877.2944   561.9  881.68   605.7  891.52   629.6  894.21   641.6  898.18
#Mann= 9 ,-1 , 0
       0     .12       0   247.1    .045       0   270.1     .12       0
  309.56    .016       0  340.55     .12       0  371.54     .06       0
  402.53     .12       0  491.95     .06       0  526.48     .12       0
#XS Ineff= 2 , 0
                          313.61          851.33
Permanent Ineff=
       F       F
Bank Sta=247.1,270.1
XS Rating Curve= 0 ,0
Exp/Cntr=0.3,0.1

Type RM Length L Ch R = 1 ,26977.9 ,167.4,167.1,166.2
XS GIS Cut Line= 2
     1744131.813      399197.394     1744554.399      399687.858
#Sta/Elev= 30
       0  948.31      44  932.09    67.9  921.25    79.9  918.49    99.9  911.94
   151.9   891.4   227.8   867.8   255.8   856.1   275.8   849.9   291.7  843.77
   308.8  840.14   315.7  839.66   323.8     840   339.7  844.08  346.59844.8578
   375.6  845.18  385.58846.9457  419.86849.8044  424.56849.5272   439.6  850.01
  463.55855.1281  465.11855.5099   483.6  860.19   495.5  858.11  510.36858.1229
   535.5  858.44   555.5  866.32   579.5  872.11   623.4   881.2   647.4  883.18
#Mann= 10 ,-1 , 0
       0     .12       0   308.8    .045       0   323.8     .12       0
  346.59    .016       0  385.58     .06       0  419.86     .12       0
  424.56     .08       0  463.55     .12       0  465.11     .08       0
  510.36     .12       0
Bank Sta=308.8,323.8
XS Rating Curve= 0 ,0
Exp/Cntr=0.3,0.1

Type RM Length L Ch R = 1 ,26810.8 ,145.4,148.7,152.1
XS GIS Cut Line= 2
     1744008.549      399303.297     1744431.135       399793.76
#Sta/Elev= 30
       0   991.8      28  981.51    71.9  963.87   107.9  951.38   135.9  939.72
   147.9  933.15   159.8  929.45   167.8  926.11   183.8  918.27   199.8  907.89
   239.8  887.66   247.8     883   263.8  870.74   283.7  858.47   303.7  843.56
   311.7  841.71   327.7   841.7   336.5  838.97   343.7  837.79   351.5  839.44
   359.7     843  382.46 844.023  401.73845.4938  479.71850.0037   503.5  851.75
   519.5  856.08   551.5  861.84   599.4  875.67   631.4  886.01   647.4   889.9
#Mann= 6 ,-1 , 0
       0     .12       0   336.5    .045       0   351.5    .016       0
  382.46     .06       0  401.73     .08       0  479.71     .12       0
Bank Sta=336.5,351.5
XS Rating Curve= 0 ,0
Exp/Cntr=0.3,0.1

Type RM Length L Ch R = 1 ,26662.1 ,131.1,132.2,133.1
XS GIS Cut Line= 2
     1744027.732       399529.84     1744303.773       399913.52
#Sta/Elev= 30
       0   900.7    23.8  888.77    35.8  881.26    63.6  868.18    79.4  858.42
    95.3  857.32    99.3   856.5   115.2   847.5   127.1  842.79   154.9  840.97
  160.46  838.46   162.8  837.29   166.8  836.62   174.8  837.13   178.1  838.58
   182.7  840.51  205.01 841.457   218.5  842.26   230.4  844.45   242.9844.6805
     290  846.41   297.9   847.6   325.7  860.18   333.6   862.4   341.6  866.09
   361.4  871.52   385.3  880.76   405.1  885.89   444.9  893.13   472.7  900.55
#Mann= 5 ,-1 , 0
       0     .12       0  160.46    .045       0   178.1    .016       0
  205.01     .08       0   242.9     .12       0
Bank Sta=160.46,178.1
XS Rating Curve= 0 ,0
Exp/Cntr=0.3,0.1

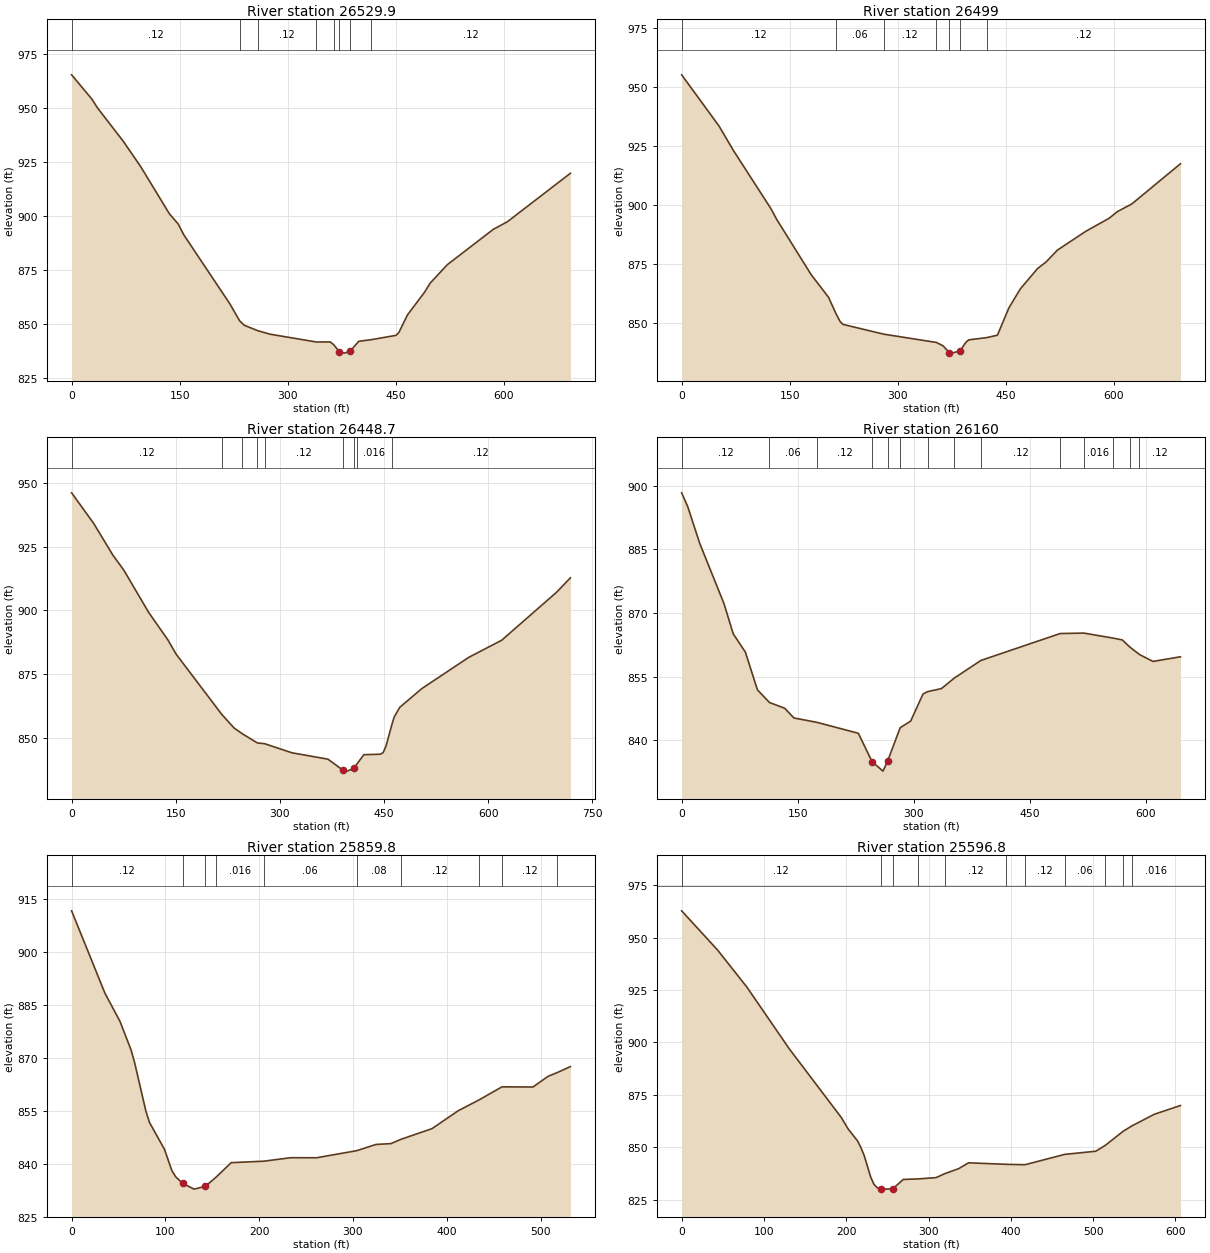
Type RM Length L Ch R = 1 ,26529.9 ,30.9,30.9,30.9
XS GIS Cut Line= 3
     1743944.867      399404.035     1743950.075      399639.712
     1744206.586      400017.316
#Sta/Elev= 30
       0  965.53      28  954.35      36  950.19    71.9  934.66    95.9     923
   135.8  901.13   147.8  896.49   155.8  891.36   219.8  859.36  233.21851.5667
   239.7  849.52  258.45847.0123   275.4   845.4   339.8841.7838   358.8  841.83
  363.58  840.59   371.6  837.26   378.6  836.63   386.6  837.56   398.5  842.11
  416.14842.8736   450.1  844.86   454.1  846.16     466  854.28   489.8  864.86
   497.7   869.1   521.5  877.62     585  893.92   604.9  897.53   692.2  919.94
#Mann= 8 ,-1 , 0
       0     .12       0  233.21     .06       0  258.45     .12       0
   339.8    .016       0  363.58     .12       0   371.6    .045       0
   386.6    .016       0  416.14     .12       0
Bank Sta=371.6,386.6
XS Rating Curve= 0 ,0
Exp/Cntr=0.3,0.1

Type RM Length L Ch R = 1 ,26499   ,45.6,50.2,54.8
XS GIS Cut Line= 3
     1743920.995      399423.566     1743926.204      399659.243
     1744182.714      400036.848
#Sta/Elev= 30
       0  955.03    51.9   933.3    71.9  922.92   123.9  898.27   131.8  893.78
   179.8  870.26   203.8  860.72  213.67854.0758   219.8  850.48   223.8  849.21
  280.48845.0582   353.5841.5518   362.8  840.11   371.3  837.28   374.7  837.02
   386.3  837.93   394.5  841.66   398.5  842.65   423.3843.5975   438.2  844.63
   454.1   856.2   469.9  864.23   493.8  872.86   505.7  875.67   521.5  880.72
   561.2  888.75     593  894.17   604.9  897.07   624.7  900.28   692.2  917.33
#Mann= 7 ,-1 , 0
       0     .12       0  213.67     .06       0  280.48     .12       0
   353.5    .016       0   371.3    .045       0   386.3    .016       0
   423.3     .12       0
Bank Sta=371.3,386.3
XS Rating Curve= 0 ,0
Exp/Cntr=0.3,0.1

Type RM Length L Ch R = 1 ,26448.7 ,250.2,288.8,320.8
XS GIS Cut Line= 4
     1743861.901      399423.193     1743899.259      399678.277
     1744013.843      399901.368     1744160.078        400052.1
#Sta/Elev= 30
       0  946.21    31.7  934.24    59.5  921.71    75.4  915.75     111  899.22
   138.8  888.37   150.7  882.75  216.28859.1387     234  853.79  246.13851.4727
  267.68847.8968  278.02847.6056   317.5  844.02   369.3  841.52   391.1  837.16
   397.1  836.82   406.1  837.88  410.83839.5234     421  843.28   444.9  843.47
   448.9  844.15   452.9  846.65  461.62855.3139   464.8  858.16   472.8  861.92
   504.6  869.28     572  881.52   619.6  888.27   698.8  907.17   718.6  912.82
#Mann= 9 ,-1 , 0
       0     .12       0  216.28     .06       0  246.13     .12       0
  267.68     .06       0  278.02     .12       0   391.1    .045       0
   406.1     .12       0  410.83    .016       0  461.62     .12       0
Bank Sta=391.1,406.1
XS Rating Curve= 0 ,0
Exp/Cntr=0.3,0.1

Type RM Length L Ch R = 1 ,26160   ,334.7,300.1,260.6
XS GIS Cut Line= 4
     1743769.977      399553.277     1743768.241      399706.055
      1743665.81      399862.305     1743818.588      400126.194
#Sta/Elev= 30
       0  898.28     7.8  895.06    23.5  886.31    54.8  872.15    66.6   865.1
    82.3  860.79    97.9   851.9  113.45848.9162   133.2  847.56     145  845.28
  174.94844.2377   228.3  841.67     246     835   260.1  832.76  265.98835.0594
  282.34842.9837   295.9  844.54   311.8   850.9  317.66851.4669   335.6  852.19
  352.52854.6981  386.65858.8193  489.04865.1531  519.82865.2552  557.29864.0828
   569.3  863.65  578.77862.0192  591.42860.2226   608.9  858.59   644.5  859.68
#Mann= 14 ,-1 , 0
       0     .12       0  113.45     .06       0  174.94     .12       0
     246    .045       0  265.98     .12       0  282.34    .016       0
  317.66     .12       0  352.52     .06       0  386.65     .12       0
  489.04     .08       0  519.82    .016       0  557.29     .12       0
  578.77     .06       0  591.42     .12       0
Bank Sta=246,265.98
XS Rating Curve= 0 ,0
Exp/Cntr=0.3,0.1

Type RM Length L Ch R = 1 ,25859.8 ,286.4,263.1,236.2
XS GIS Cut Line= 3
     1743421.019      399601.888     1743579.349      399916.683
     1743706.953      400042.985
#Sta/Elev= 30
       0  911.71    35.6  888.34    51.5  880.45    63.4   872.3    67.3   868.6
    79.2  854.96    83.1  851.73      99  844.16   106.9  838.12   110.9  836.38
   118.5  834.47   130.6  832.86   142.5  833.63  154.13836.2637   170.2  840.36
  204.82840.7703   233.6  841.76   261.3  841.75     304843.7505   324.6  845.52
   340.5  845.76  351.33846.9836   384.3     850   412.2  855.06  434.83858.1911
  458.89861.8378     492   861.8     508  864.81  517.94865.8936   531.9  867.58
#Mann= 10 ,-1 , 0
       0     .12       0   118.5    .045       0   142.5     .12       0
  154.13    .016       0  204.82     .06       0     304     .08       0
  351.33     .12       0  434.83     .06       0  458.89     .12       0
  517.94     .08       0
Bank Sta=118.5,142.5
XS Rating Curve= 0 ,0
Exp/Cntr=0.3,0.1

Type RM Length L Ch R = 1 ,25596.8 ,178,168.7,160.4
XS GIS Cut Line= 3
     1743172.515      399748.871     1743305.381      399916.451
     1743662.098        400079.6
#Sta/Elev= 30
       0  962.74    43.6  944.08    79.2  926.42   130.7  896.99   194.1  864.16
     202  858.92   213.9  852.96   217.8  849.88   221.8  846.08   229.7  835.82
   233.7  832.36   237.6  830.76   241.7  830.28   249.5  830.07   256.7   830.3
   269.3  834.68  287.27834.9423     309  835.55  319.75837.4465   336.7  839.85
   348.6  842.61  394.59841.8916  417.18841.7076   465.6846.6469   503.1  848.13
  514.61850.8957   536.6857.6865  547.09 860.208   574.4  865.77   606.1  869.93
#Mann= 11 ,-1 , 0
       0     .12       0   241.7    .045       0   256.7     .12       0
  287.27    .016       0  319.75     .12       0  394.59     .06       0
  417.18     .12       0   465.6     .06       0  514.61    .016       0
   536.6     .12       0  547.09    .016       0
Bank Sta=241.7,256.7
XS Rating Curve= 0 ,0
Exp/Cntr=0.3,0.1

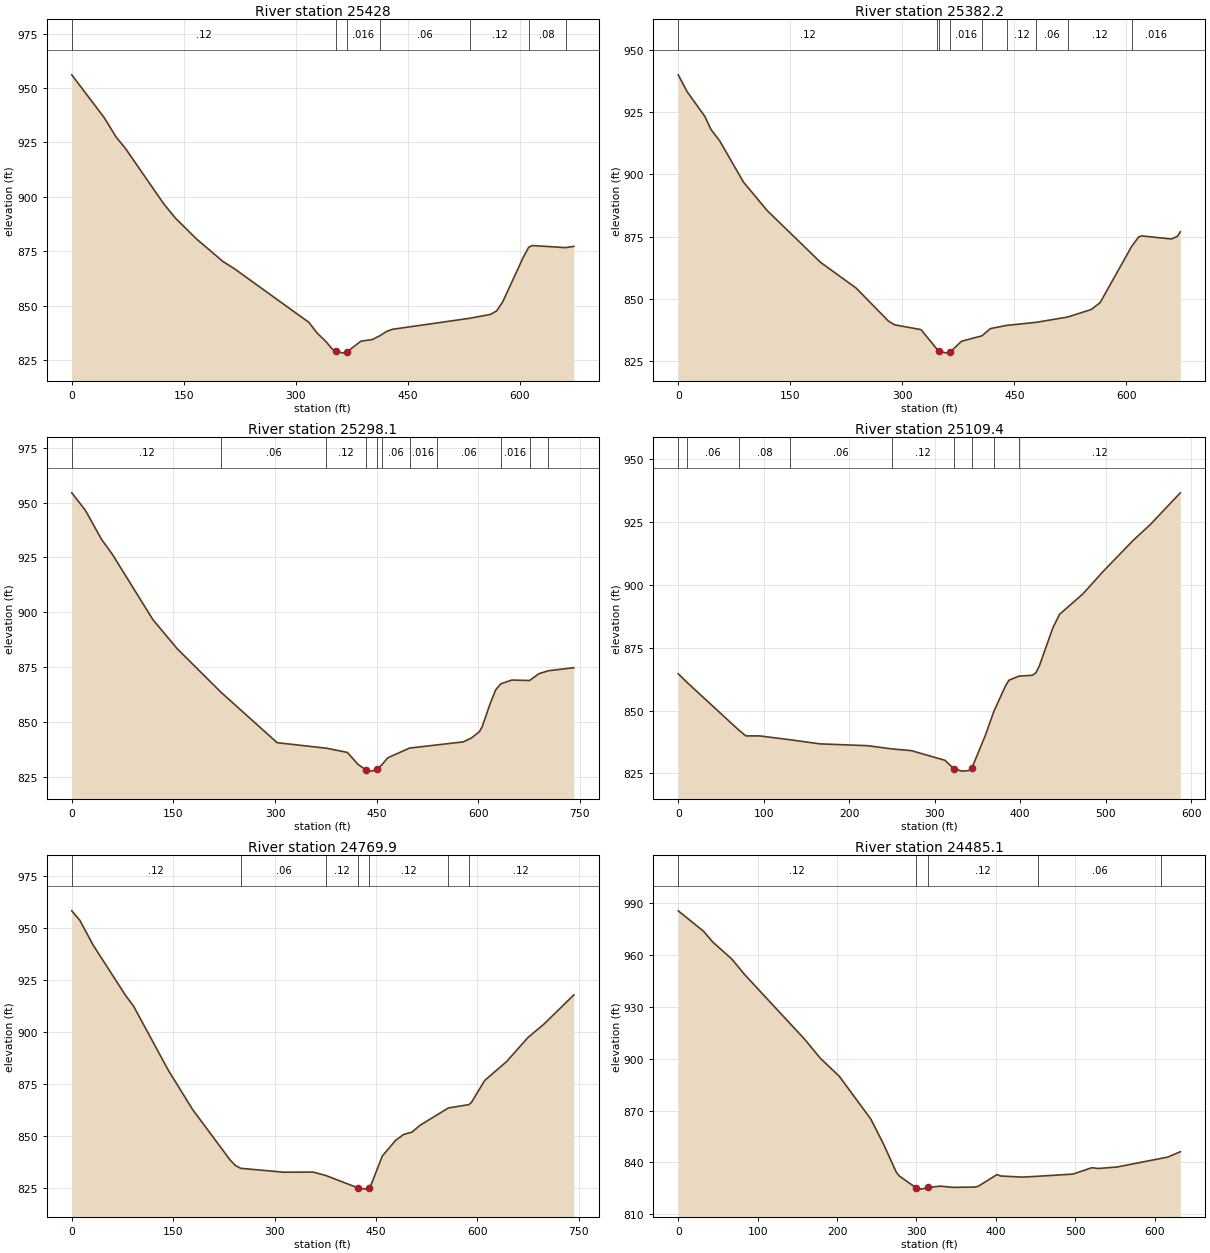
Type RM Length L Ch R = 1 ,25428   ,45.8,45.9,45.6
XS GIS Cut Line= 4
     1743151.398      399766.292     1743212.512       400069.77
     1743329.525      400096.854     1743504.352      400265.083
#Sta/Elev= 30
       0  956.04    43.7  936.24    59.5  927.38    71.4  922.43     123  896.82
   138.9  890.16   166.7  880.71   202.4  870.26   218.3   866.8   317.3  842.33
   328.9  837.24   340.6  833.37   348.3  830.17   353.4  829.03   363.8  828.13
   368.4  828.66   387.1  833.61   402.6  834.38  412.78836.1868   421.9  838.15
   429.7  839.09  533.49844.1827   560.9  845.95   568.9  847.54   576.8  851.52
   604.7  872.25  611.78876.7469   616.6  877.58  661.27876.6248   672.3  877.21
#Mann= 7 ,-1 , 0
       0     .12       0   353.4    .045       0   368.4    .016       0
  412.78     .06       0  533.49     .12       0  611.78     .08       0
  661.27    .016       0
Bank Sta=353.4,368.4
XS Rating Curve= 0 ,0
Exp/Cntr=0.3,0.1

Type RM Length L Ch R = 1 ,25382.2 ,62.3,84.1,106.9
XS GIS Cut Line= 4
     1743127.787      399803.792       1743188.9       400107.27
     1743305.914      400134.354     1743480.741      400302.583
#Sta/Elev= 30
       0  940.04    11.9  933.26    35.7  923.29    43.7  918.14    55.6  913.45
    87.3  896.93   119.1  885.45   190.5  864.64   238.1   854.3   281.8  840.91
   289.7   839.5   325.1  837.56  346.07829.8577   349.2  828.87   359.9  828.11
   364.2  828.58   379.3  832.88   406.7835.0739     418  837.98  439.61839.2554
  479.41840.4951  521.58 842.635     553  845.65   564.9  848.41  607.19871.0482
   616.6  874.85   620.6  875.25   660.4  874.02   668.3  875.06   672.3   876.9
#Mann= 9 ,-1 , 0
       0     .12       0  346.07    .016       0   349.2    .045       0
   364.2    .016       0   406.7     .06       0  439.61     .12       0
  479.41     .06       0  521.58     .12       0  607.19    .016       0
Bank Sta=349.2,364.2
XS Rating Curve= 0 ,0
Exp/Cntr=0.3,0.1

Type RM Length L Ch R = 1 ,25298.1 ,160.4,188.7,215.5
XS GIS Cut Line= 3
      1743125.64      399771.006     1743115.289      400117.947
     1743399.144      400391.385
#Sta/Elev= 30
       0  954.44      20  946.52    43.9  933.24    59.8  926.46   119.7  896.64
   155.6  883.35  220.72863.3704   303.2  840.48  375.65  837.98   406.8  836.05
   422.7  830.56   434.7     828   442.6  827.51   450.6  828.33  457.67830.3468
   466.5  833.59  498.68 838.025   539.7 839.495     578  840.85     590  842.62
   601.9  845.55   605.9  847.81   617.8  858.42   625.8  864.58  633.31 867.308
   649.7  869.06  675.88868.8346   689.5  871.93  703.74873.2996   741.2  874.68
#Mann= 11 ,-1 , 0
       0     .12       0  220.72     .06       0  375.65     .12       0
   434.7    .045       0   450.6     .12       0  457.67     .06       0
  498.68    .016       0   539.7     .06       0  633.31    .016       0
  675.88     .12       0  703.74    .016       0
Bank Sta=434.7,450.6
XS Rating Curve= 0 ,0
Exp/Cntr=0.3,0.1

Type RM Length L Ch R = 1 ,25109.4 ,307.5,339.5,370.5
XS GIS Cut Line= 4
     1743087.946      399981.229     1743048.883      400183.051
      1743065.81      400395.291     1742978.571      400539.822
#Sta/Elev= 30
       0  864.64   10.59861.1161   70.76842.2452    79.1  839.91    94.9  839.91
  130.92 838.376     166  836.73   221.3  836.02  250.57834.7083   272.6  834.05
     312   830.2   322.3  826.86   331.7  825.89   339.6   826.1   343.6  827.22
   359.3  840.15  369.09849.5714     383  859.93   386.9  862.07  398.71863.7037
   414.5  864.03   418.5   865.1   422.4  867.73   438.1  882.82     446  888.26
   473.4  896.44     497  905.34   532.3  917.76     552  923.93   587.3  936.63
#Mann= 9 ,-1 , 0
       0     .12       0   10.59     .06       0   70.76     .08       0
  130.92     .06       0  250.57     .12       0   322.3    .045       0
   343.6     .12       0  369.09    .016       0  398.71     .12       0
Bank Sta=322.3,343.6
XS Rating Curve= 0 ,0
Exp/Cntr=0.3,0.1

Type RM Length L Ch R = 1 ,24769.9 ,292.1,284.8,276.4
XS GIS Cut Line= 4
     1742978.504      399751.475     1742929.025      399980.641
     1742752.511      400155.672     1742695.952      400409.027
#Sta/Elev= 30
       0   958.1    11.9  953.56    31.8  941.52    79.5  917.48    91.4  912.29
     143  881.36   178.8  862.56   234.4  838.24   242.3  835.61  250.05834.3212
   313.4  832.46   356.8  832.52  375.89830.8567   423.8  824.85   435.7  824.32
   439.6  824.87   443.6  827.13   459.4  840.29   479.1  847.78     491  850.63
     503  851.67     515  854.98  557.05863.3409  587.31864.9307   590.9   865.9
   610.8  876.57   642.8  885.54   674.7  897.18   698.7  903.74   742.6  917.69
#Mann= 7 ,-1 , 0
       0     .12       0  250.05     .06       0  375.89     .12       0
   423.8    .045       0   439.6     .12       0  557.05    .016       0
  587.31     .12       0
Bank Sta=423.8,439.6
XS Rating Curve= 0 ,0
Exp/Cntr=0.3,0.1

Type RM Length L Ch R = 1 ,24485.1 ,167.8,159.2,150.9
XS GIS Cut Line= 2
      1742796.58      399632.829     1742446.103      400159.088
#Sta/Elev= 30
       0  985.53    31.8  973.75    43.7  967.39    67.6  957.59    83.5  948.71
   159.1  911.29     179   900.2   202.8  889.83   242.6  864.98   258.5  850.64
   274.4  834.49   278.4   832.1   299.5  825.32   306.2  824.51   314.5  825.46
   330.1  826.24     346  825.53   373.8   825.7   377.8  826.16   401.6  832.97
   405.6  832.13   433.4  831.46  453.61 831.964   497.1  833.21   520.9   836.9
   528.9  836.44   552.8  837.33  608.53842.3294   616.4  843.02   632.3  846.16
#Mann= 5 ,-1 , 0
       0     .12       0   299.5    .045       0   314.5     .12       0
  453.61     .06       0  608.53     .12       0
Bank Sta=299.5,314.5
XS Rating Curve= 0 ,0
Exp/Cntr=0.3,0.1