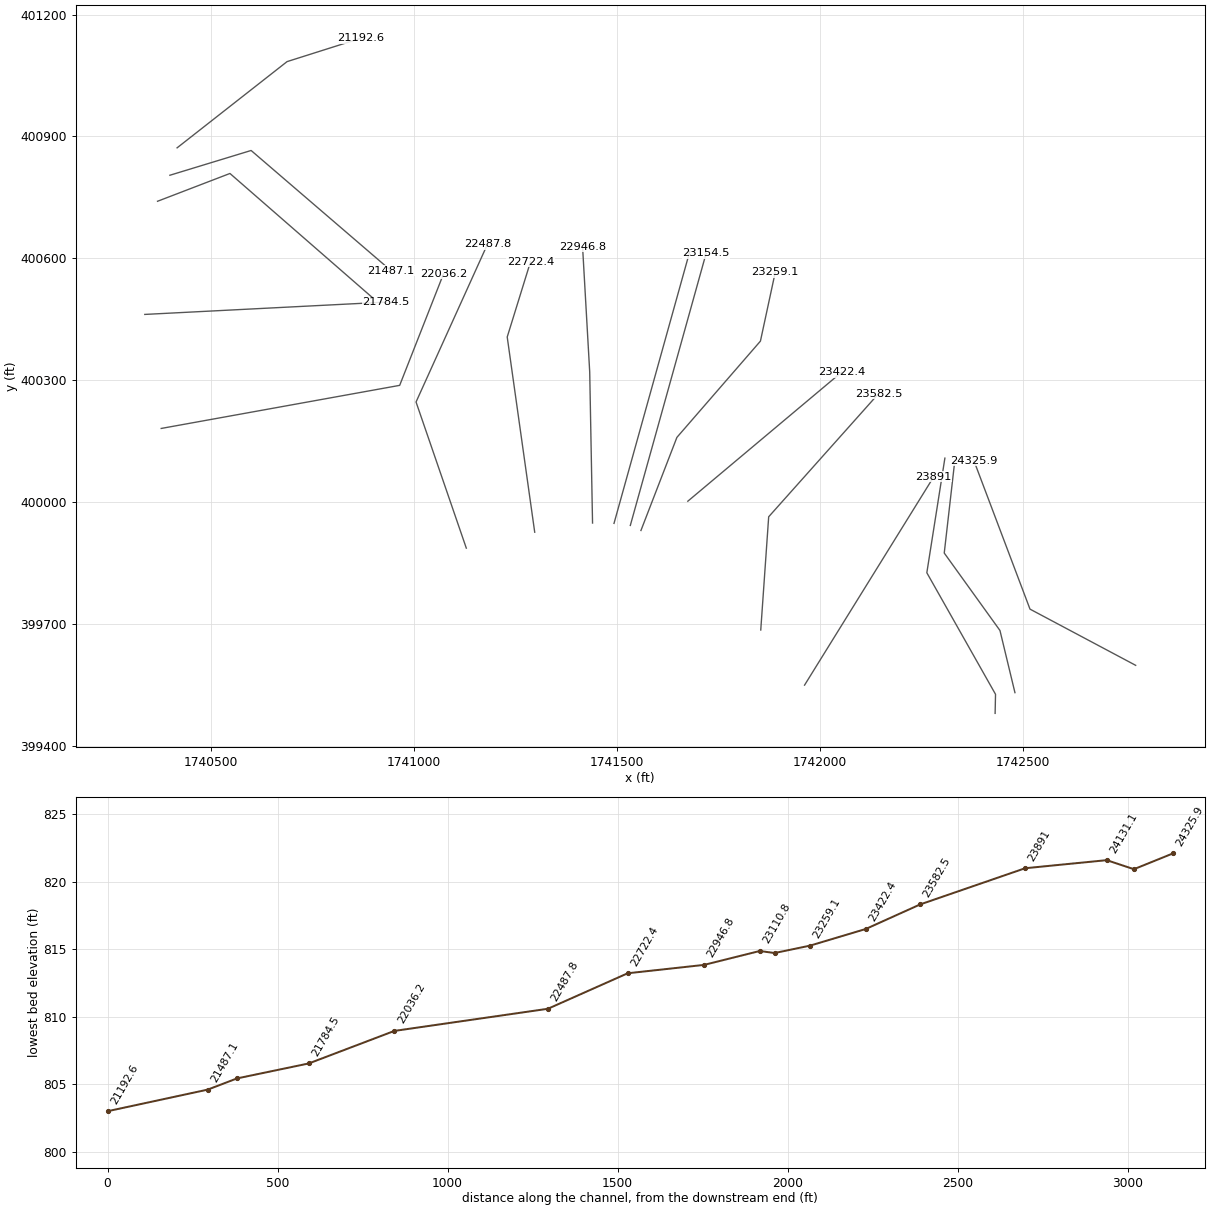
HEC-RAS study ROCKCK.prj: ROCKCK

--- ROCKCK.g01 (geometry) --- (continued)

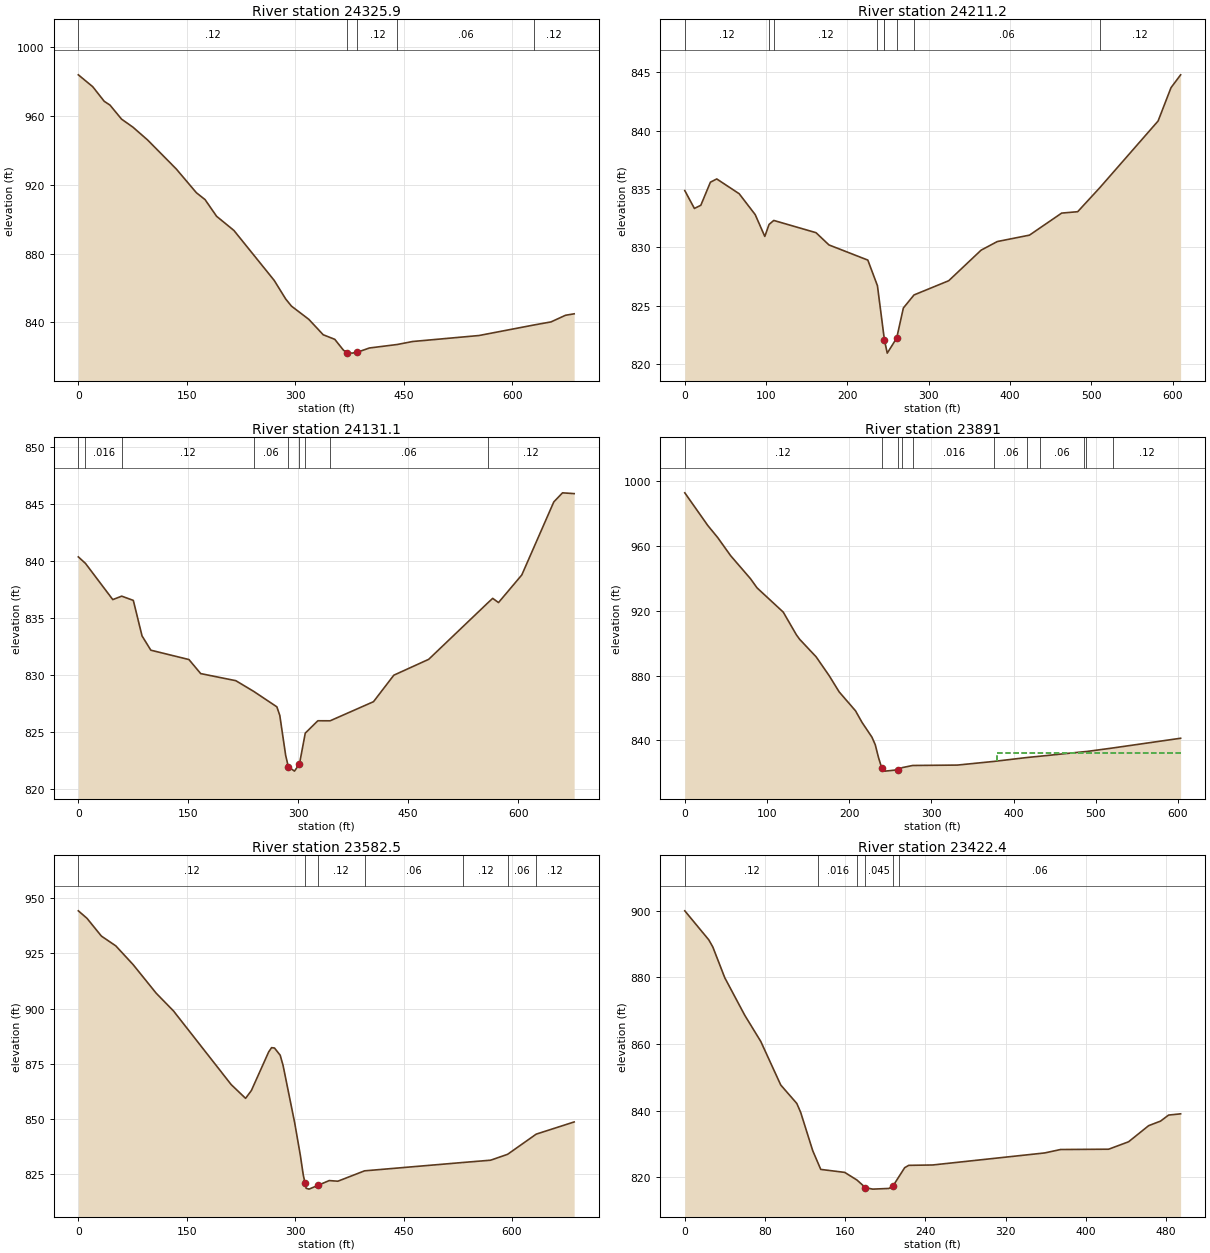
Type RM Length L Ch R = 1 ,24325.9 ,104.6,114.7,124.6
XS GIS Cut Line= 3
     1742778.134      399598.106     1742517.882      399736.447
     1742379.696      400102.013
#Sta/Elev= 30
       0  984.02    19.9  977.11    35.8  968.62    43.8   966.4    59.7  958.28
    75.7   953.5    95.6  946.19   135.4  929.25   163.3  915.39   175.2  911.44
   191.2  901.71   215.1  893.49   270.8  864.44   286.8  853.56   294.7  849.45
   318.7  841.76   338.6  832.79   354.6  830.13   366.5  823.86     371  822.44
   378.5   822.1     386  822.65   402.4  825.08  441.25827.1407   462.2  828.86
     554  832.34   630.7  838.53   653.6  840.26   673.6  844.12   685.6  844.97
#Mann= 5 ,-1 , 0
       0     .12       0     371    .045       0     386     .12       0
  441.25     .06       0   630.7     .12       0
Bank Sta=371,386
XS Rating Curve= 0 ,0
Exp/Cntr=0.3,0.1

Type RM Length L Ch R = 1 ,24211.2 ,83.5,80.1,75.2
XS GIS Cut Line= 4
     1742480.825      399530.832     1742443.932      399683.827
     1742306.696      399874.458     1742331.435      400090.604
#Sta/Elev= 30
       0  834.87    11.8  833.34    19.7  833.61    31.5  835.59    39.3  835.87
    66.9   834.6    86.6  832.81    98.4  830.94  103.63831.9673  109.43  832.31
   161.4  831.26   177.3  830.21   225.1  828.91  236.92826.7142  245.51822.0585
   245.6  822.03     249  820.93   260.6  822.22   268.8   824.8  281.91825.9205
   324.6  827.14   364.4  829.76   384.3   830.5   423.9  831.05   463.5  832.94
   483.2  833.06  510.22835.1046   582.1  840.84     598   843.7   609.8   844.8
#Mann= 9 ,-1 , 0
       0     .12       0  103.63    .016       0  109.43     .12       0
  236.92    .016       0  245.51     .12       0   245.6    .045       0
   260.6     .12       0  281.91     .06       0  510.22     .12       0
Bank Sta=245.6,260.6
XS Rating Curve= 0 ,0
Exp/Cntr=0.3,0.1

Type RM Length L Ch R = 1 ,24131.1 ,280.8,240.1,199.7
XS GIS Cut Line= 4
     1742431.997      399479.834     1742432.998      399526.801
     1742263.811      399825.971     1742308.299      400108.089
#Sta/Elev= 30
       0  840.36     9.7839.7939      47  836.62   59.17836.9225      75  836.55
    86.9  833.44    98.9  832.19   150.9  831.37   166.9  830.14   214.8  829.52
  239.17828.5848   270.8  827.23   274.8  826.48   282.8  822.98  286.42821.9893
   294.8   821.6   301.6  822.22  309.55824.9274   326.7  826.01  343.48826.0076
   402.6  827.68   430.3     830   477.9  831.39  558.39836.3242   565.2  836.73
   573.1  836.36   604.9  838.78   648.5  845.17   660.4  845.97   676.3   845.9
#Mann= 9 ,-1 , 0
       0     .08       0     9.7    .016       0   59.17     .12       0
  239.17     .06       0  286.42    .045       0   301.6     .12       0
  309.55    .016       0  343.48     .06       0  558.39     .12       0
Bank Sta=286.42,301.6
XS Rating Curve= 0 ,0
Exp/Cntr=0.3,0.1

Type RM Length L Ch R = 1 ,23891   ,314.8,308.5,302.8
XS GIS Cut Line= 2
     1741962.669      399549.331     1742280.654      400061.958
#Sta/Elev= 30
       0  992.83      28  972.65      40  965.23    55.9  953.93    79.9  939.82
    87.9  934.15   119.8  919.16   135.8  905.13   139.8  902.36   159.8  891.55
   175.8  879.81   187.8  869.93   207.7  858.23   215.7  851.02   227.7  841.95
   231.7  837.31   235.7  829.32   239.7  822.76   243.7     821   259.7  821.83
  264.53823.1634   277.2 824.488   331.6  824.73  376.59827.0235  416.23829.4056
  432.63830.2234  485.74832.9863  488.66833.1026  520.49835.2739   603.2   841.3
#Mann= 11 ,-1 , 0
       0     .12       0   239.7    .045       0   259.7     .12       0
  264.53     .06       0   277.2    .016       0  376.59     .06       0
  416.23    .016       0  432.63     .06       0  485.74    .016       0
  488.66     .06       0  520.49     .12       0
#XS Ineff= 2 , 0
                           380.1          832.17
Permanent Ineff=
       F       F
Bank Sta=239.7,259.7
XS Rating Curve= 0 ,0
Exp/Cntr=0.3,0.1

Type RM Length L Ch R = 1 ,23582.5 ,167.8,160.1,151.9
XS GIS Cut Line= 3
     1741854.806      399685.068     1741874.337      399963.714
     1742145.171      400267.099
#Sta/Elev= 30
       0  944.18      12  940.79    31.9  932.76    51.9  928.32    75.8  919.86
   107.7  906.93   131.7  898.89   211.5  865.59   231.4  859.38   239.4   862.9
   263.4   880.4   267.4   882.3   271.4  882.14   279.3  878.87   283.3  874.22
   299.3  848.38   307.2  833.55   311.2  824.75  313.73820.9297   315.2  818.71
   319.2  818.32   331.2  819.98   347.1  822.19   359.1   821.9  395.95826.5872
  532.66830.3836   570.4   831.4  593.91834.0623   633.5843.1902     686   848.7
#Mann= 7 ,-1 , 0
       0     .12       0  313.73    .045       0   331.2     .12       0
  395.95     .06       0  532.66     .12       0  593.91     .06       0
   633.5     .12       0
Bank Sta=313.73,331.2
XS Rating Curve= 0 ,0
Exp/Cntr=0.3,0.1

Type RM Length L Ch R = 1 ,23422.4 ,152.6,163.4,167.4
XS GIS Cut Line= 2
     1741675.185      400002.062     1742054.092       400319.77
#Sta/Elev= 30
       0  899.96    23.9  891.27    27.9  889.15    39.9  879.88    59.8  868.64
    75.8  860.78    95.7  847.72   111.7   842.2   115.6  839.49   127.6  828.02
  133.16 824.118   135.6  822.41   159.5  821.52  171.71819.2233   180.1  816.96
   187.4   816.5   203.4   816.7   207.4  817.32  213.63820.2722   219.3  822.93
   223.3  823.63   247.2  823.74   358.9  827.35   374.8  828.38   422.7  828.47
   442.6   830.7   462.6  835.53   474.5   836.9   482.5  838.71   494.5  839.08
#Mann= 6 ,-1 , 0
       0     .12       0  133.16    .016       0  171.71     .12       0
   180.1    .045       0   207.4     .12       0  213.63     .06       0
Bank Sta=180.1,207.4
XS Rating Curve= 0 ,0
Exp/Cntr=0.3,0.1

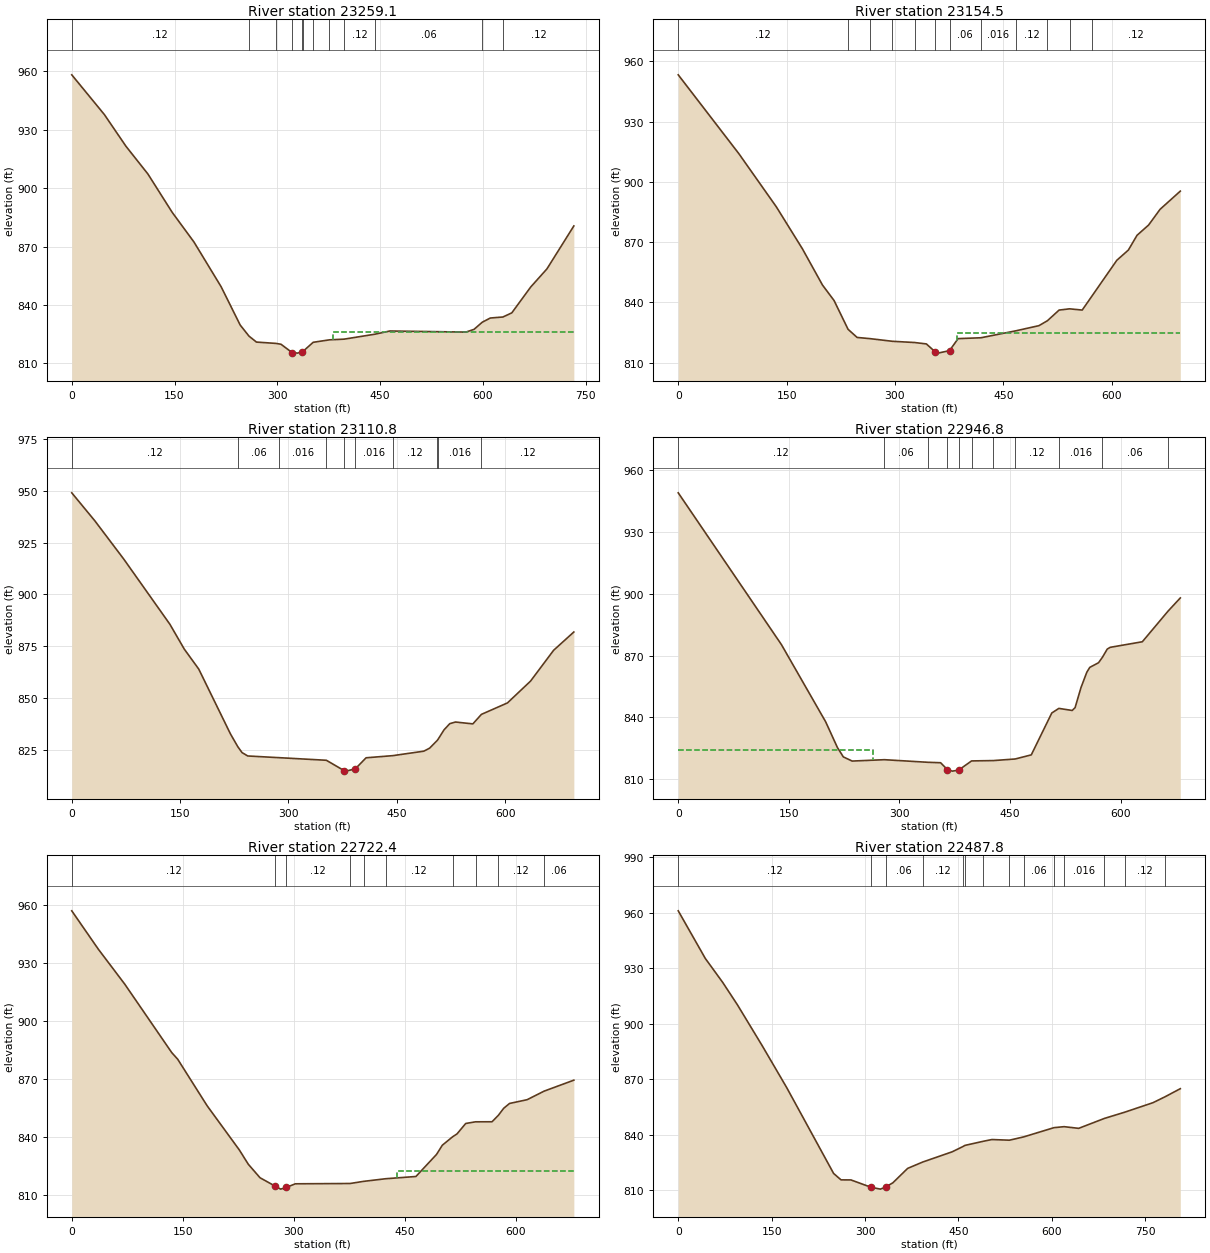
Type RM Length L Ch R = 1 ,23259.1 ,89.6,104.5,123.6
XS GIS Cut Line= 4
     1741559.731      399929.964     1741648.273      400159.131
     1741854.002       400396.11      1741890.46      400565.381
#Sta/Elev= 30
       0  958.13    47.6  937.72    79.2   921.4     111  907.28   146.6  887.51
   178.3  872.31   217.9  849.38   245.7  829.72  258.56824.0064   269.5  820.94
  297.67820.2702   305.3  819.83   321.4  815.58   329.1  815.27   336.4  815.93
  336.79 815.982  352.28820.8289   375.9822.0853  397.33 822.441  442.39824.9906
   464.2  826.63   575.2  826.07     587  827.48  598.95831.1411   610.7  833.29
  629.16833.8171   642.1  835.95   669.7  849.23   693.3  858.49   732.6  880.56
#Mann= 12 ,-1 , 0
       0     .12       0  258.56    .016       0  297.67     .12       0
   321.4    .045       0   336.4     .12       0  336.79     .06       0
  352.28     .12       0   375.9     .06       0  397.33     .12       0
  442.39     .06       0  598.95    .016       0  629.16     .12       0
#XS Ineff= 2 , 0
                             381          826.33
Permanent Ineff=
       F       F
Bank Sta=321.4,336.4
XS Rating Curve= 0 ,0
Exp/Cntr=0.3,0.1

Type RM Length L Ch R = 1 ,23154.5 ,44.6,43.7,40.6
XS GIS Cut Line= 2
     1741533.559      399942.421     1741720.191      400611.908
#Sta/Elev= 30
       0  953.23    83.9     914   135.8  887.53   171.8   866.7   199.7   848.6
   215.7  840.91  235.08826.5851   247.6  822.53  265.74821.9209   296.4 820.612
  327.06     820   343.5   819.3   355.5  815.42   359.5  814.72   375.5  815.95
   387.4  821.93  419.04822.3674  467.47825.8336   499.3  828.39  511.03830.8378
   527.2  836.14  541.69836.7667   559.2  836.15  572.35842.9467   607.1  860.92
   623.1  866.02   635.1  873.37   651.1  878.47     667   886.3     695  895.35
#Mann= 12 ,-1 , 0
       0     .12       0  235.08    .016       0  265.74     .06       0
   296.4     .12       0  327.06    .016       0   355.5    .045       0
   375.5     .06       0  419.04    .016       0  467.47     .12       0
  511.03     .08       0  541.69    .016       0  572.35     .12       0
#XS Ineff= 2 , 0
                          385.49          824.49
Permanent Ineff=
       F       F
Bank Sta=355.5,375.5
XS Rating Curve= 0 ,0
Exp/Cntr=0.3,0.1

Type RM Length L Ch R = 1 ,23110.8 ,153,164,176.5
XS GIS Cut Line= 2
     1741493.412      399947.499     1741680.043      400616.987
#Sta/Elev= 30
       0  948.93      32  935.42    71.9  917.04   135.8  885.63   155.8  873.62
   175.8  864.01   219.7  832.77   229.8826.6505   235.7   823.8   243.6  822.17
     287821.3521  352.45820.0949   377.5  815.02   379.5  814.87   392.5  815.97
   407.4  821.29  444.43  822.33   487.3  824.48   495.3  825.92  505.76829.6039
  506.99830.1758   515.3  834.75   523.3  837.74   531.2  838.52   555.2  837.63
  567.08842.2113   603.1  847.73   635.1  858.25     667  873.08     695  881.89
#Mann= 10 ,-1 , 0
       0     .12       0   229.8     .06       0     287    .016       0
  352.45     .12       0   377.5    .045       0   392.5    .016       0
  444.43     .12       0  505.76     .08       0  506.99    .016       0
  567.08     .12       0
Bank Sta=377.5,392.5
XS Rating Curve= 0 ,0
Exp/Cntr=0.3,0.1

Type RM Length L Ch R = 1 ,22946.8 ,218.9,224.4,227.4
XS GIS Cut Line= 3
     1741440.538      399948.334     1741433.552      400320.087
     1741415.962      400628.677
#Sta/Elev= 30
       0  949.04   139.9  875.33   199.9  837.83   215.9   825.3   223.9  820.75
   235.9  818.73  279.65819.3925  338.73818.1313   355.8  817.92   365.1  814.56
   371.8  813.84   380.1  814.31  397.85818.8006  427.43818.9603  457.02819.7407
   478.8  821.74   506.6  842.08  516.18844.3146   534.3  843.31   538.2  844.68
   546.2  854.42   554.1  861.88   558.1  864.24     570   866.5  575.35869.1886
   581.8  873.12   585.8  873.98   629.4  876.69   664.1891.4925   680.9  897.98
#Mann= 11 ,-1 , 0
       0     .12       0  279.65     .06       0  338.73     .12       0
   365.1    .045       0   380.1     .12       0  397.85    .016       0
  427.43     .06       0  457.02     .12       0  516.18    .016       0
  575.35     .06       0   664.1     .12       0
#XS Ineff= 2 , 0
          264.18  824.08
Permanent Ineff=
       F       F
Bank Sta=365.1,380.1
XS Rating Curve= 0 ,0
Exp/Cntr=0.3,0.1

Type RM Length L Ch R = 1 ,22722.4 ,227.6,234.6,242.1
XS GIS Cut Line= 3
     1741298.099      399925.797     1741230.391      400406.266
     1741287.682      400591.162
#Sta/Elev= 30
       0  957.12    35.8  937.34    71.6  919.23   135.2   883.8   143.2   880.4
     183  856.33   226.7   833.4   238.6  826.12   254.5  819.11   275.1  814.74
   282.4  813.22   290.1  814.13   302.3  815.97  376.29816.1309  394.61817.2369
  424.44818.5916   465.3  819.76   493.1  831.13     501  835.93  514.97840.3055
   520.8  841.76   532.6  847.16  545.89848.0263   568.2  848.05  576.81851.4169
     584  855.03   591.9  857.52   615.6  859.46  638.65863.8911   678.8  869.56
#Mann= 10 ,-1 , 0
       0     .12       0   275.1    .045       0   290.1     .12       0
  376.29     .06       0  394.61    .016       0  424.44     .12       0
  514.97     .08       0  545.89    .016       0  576.81     .12       0
  638.65     .06       0
#XS Ineff= 2 , 0
       0                     440       0  822.45
Permanent Ineff=
       F       F
Bank Sta=275.1,290.1
XS Rating Curve= 0 ,0
Exp/Cntr=0.3,0.1

Type RM Length L Ch R = 1 ,22487.8 ,516.6,451.5,385.4
XS GIS Cut Line= 3
     1741129.631      399886.557     1741005.848      400246.266
     1741181.629      400634.287
#Sta/Elev= 30
       0  960.91    43.6  935.13    71.3  922.31    95.1  910.13   134.7  888.15
   174.4  865.32   249.6  819.04   261.5  815.59   277.4  815.56   309.7  811.59
   324.7  810.59   332.9  811.67   344.8  814.03   368.5   821.8  392.72825.2327
   440.1  830.76  457.57833.6379  460.37834.2012  489.99836.4376   503.8  837.37
  531.95  837.02  554.84 838.804  603.53 843.789  619.69844.3234   643.2  843.42
  684.54848.7863  716.96 852.129   762.6  857.29  781.81860.4593   806.4  864.84
#Mann= 14 ,-1 , 0
       0     .12       0   309.7    .045       0   332.9     .06       0
  392.72     .12       0  457.57     .06       0  460.37     .12       0
  489.99     .06       0  531.95     .12       0  554.84     .06       0
  603.53     .08       0  619.69    .016       0  684.54     .06       0
  716.96     .12       0  781.81     .06       0
Bank Sta=309.7,332.9
XS Rating Curve= 0 ,0
Exp/Cntr=0.3,0.1

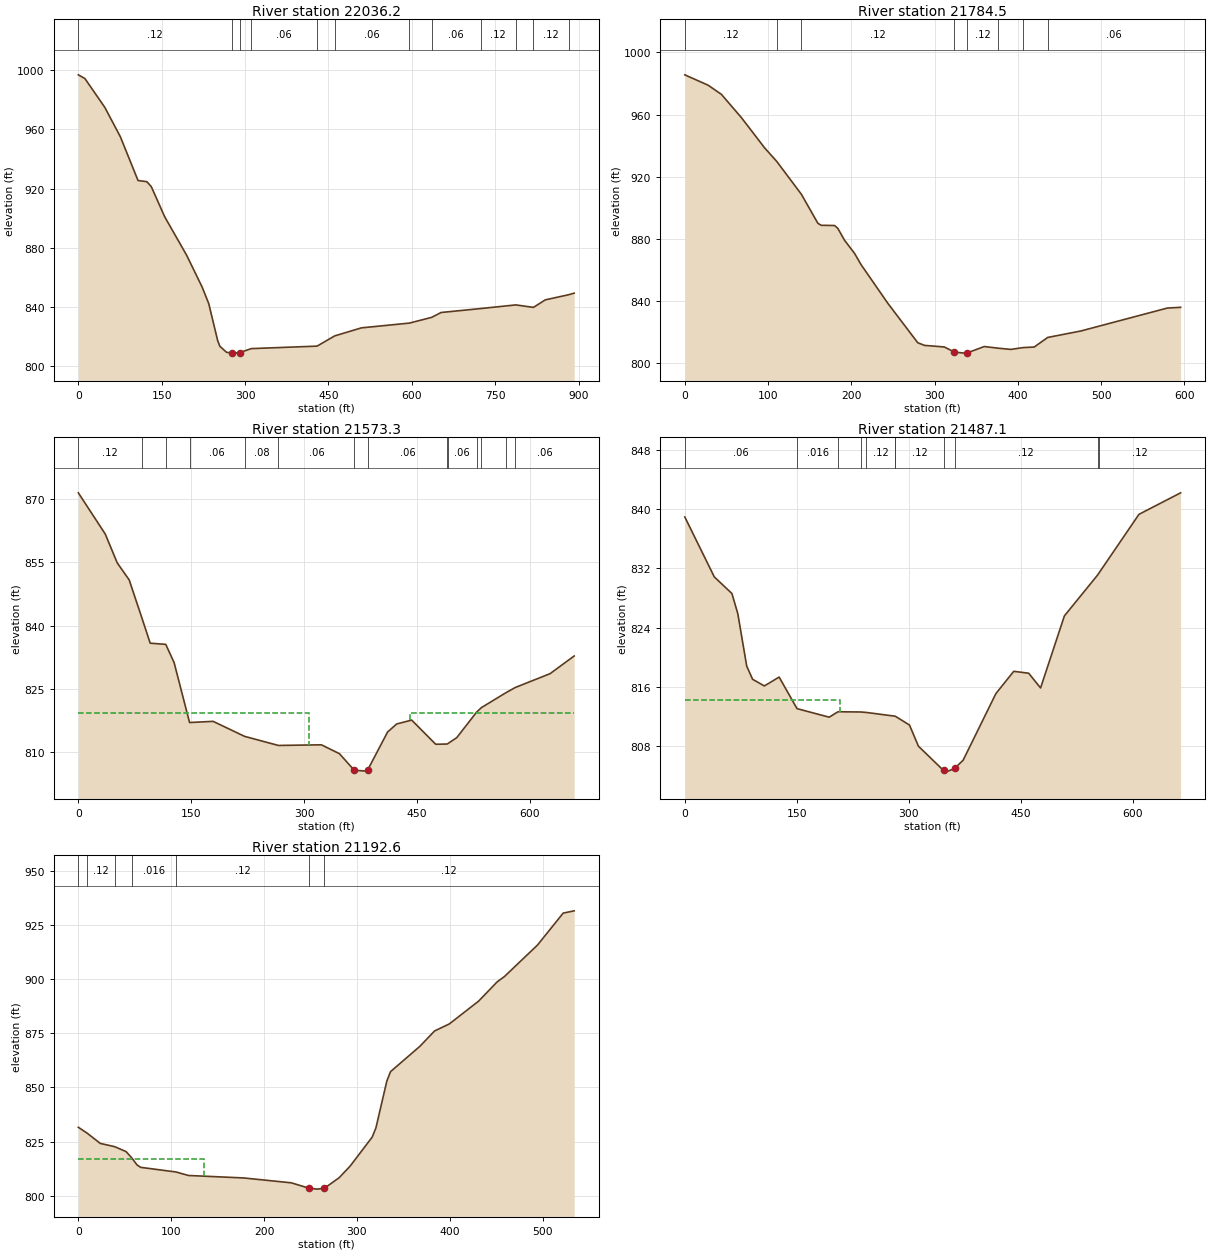
Type RM Length L Ch R = 1 ,22036.2 ,256.3,251.7,246.7
XS GIS Cut Line= 3
     1740378.244      400181.162      1740965.55      400287.218
     1741073.623      400561.958
#Sta/Elev= 30
       0  996.84    11.9   994.3    47.7  974.84    75.6  955.04   107.4  925.49
   123.3  924.69   131.3  921.34   155.2  901.14     195  874.93   222.8  853.51
   234.7  842.29   250.7  817.39   254.6  813.59   266.6  809.54   275.9  808.96
   278.5  808.95   290.9  809.35  311.13812.0026  429.47813.6748  461.19820.5817
   509.3  826.01  595.65829.2299  635.66 833.096   652.7  836.39  723.54839.0232
  787.01841.5039  818.75839.8415   840.2  844.92  882.23848.3917     892  849.44
#Mann= 12 ,-1 , 0
       0     .12       0   275.9    .045       0   290.9     .12       0
  311.13     .06       0  429.47     .12       0  461.19     .06       0
  595.65     .12       0  635.66     .06       0  723.54     .12       0
  787.01    .016       0  818.75     .12       0  882.23    .016       0
Bank Sta=275.9,290.9
XS Rating Curve= 0 ,0
Exp/Cntr=0.3,0.1

Type RM Length L Ch R = 1 ,21784.5 ,242.5,211.2,176.3
XS GIS Cut Line= 2
     1740337.813      400461.822     1740932.431      400492.204
#Sta/Elev= 30
       0  985.56      28  978.89      44  972.98    67.9  958.09    95.9  938.55
  110.47929.8224  140.04908.6815   159.8  890.07   163.8  888.76   179.8  888.64
   183.8  886.76   191.8  879.16   203.8  870.74   211.8  863.36   243.8   838.6
   279.7  813.25   287.7  811.53   311.7   810.5   323.7  807.22   335.7  806.54
   338.7   806.6   359.6  810.78  376.63809.6899   391.6  808.94  406.21810.1026
   419.6  810.46  435.78816.6234   475.5  820.77   579.4  835.53   595.4  836.01
#Mann= 8 ,-1 , 0
       0     .12       0  110.47     .06       0  140.04     .12       0
   323.7    .045       0   338.7     .12       0  376.63     .06       0
  406.21     .12       0  435.78     .06       0
Bank Sta=323.7,338.7
XS Rating Curve= 0 ,0
Exp/Cntr=0.3,0.1

Type RM Length L Ch R = 1 ,21573.3 ,84.5,86.2,91.4
XS GIS Cut Line= 3
     1740369.196      400740.343     1740547.515      400808.766
     1740900.379      400501.475
#Sta/Elev= 30
       0  871.51    35.8  861.72    51.7  854.88    67.6  850.83   84.56841.7625
    95.5  835.81  116.19835.5291   127.3  831.19  147.83816.9697   179.1  817.25
  220.91813.6854  265.88 811.526     323  811.68     347  809.57   366.7  805.63
     383  805.43  384.39805.6698     411  814.72     423  816.62     443  817.55
   474.9  811.81  490.04811.8669  490.75811.9272   502.9  813.38   529.2819.4272
  535.73820.5172  568.37824.0613   580.7825.2915   626.9  828.57   658.9  832.77
#Mann= 14 ,-1 , 0
       0     .12       0   84.56     .06       0  116.19     .12       0
  147.83     .06       0  220.91     .08       0  265.88     .06       0
   366.7    .045       0  384.39     .06       0  490.04    .016       0
  490.75     .06       0   529.2     .08       0  535.73     .06       0
  568.37     .12       0   580.7     .06       0
#XS Ineff= 2 , 0
       0     307  819.29  441.21       0  819.29
Permanent Ineff=
       F       F
Bank Sta=366.7,384.39
XS Rating Curve= 0 ,0
Exp/Cntr=0.3,0.1

Type RM Length L Ch R = 1 ,21487.1 ,241.5,294.5,346.8
XS GIS Cut Line= 3
     1740399.619      400804.399     1740599.664      400865.343
      1740944.65      400569.183
#Sta/Elev= 30
       0  838.95    39.5  830.85    63.1   828.6      71  825.87    82.9  818.79
    90.8  817.01   106.5  816.11   126.3  817.31  150.28813.0439   193.3  811.89
  205.11812.6232  235.45812.5922  242.98  812.53   280.8812.0333  281.91812.0123
   300.8  810.83   312.8  807.97   346.4  804.69   352.7   804.6   361.4  804.99
   372.6  806.07   416.5  815.08   440.4  818.09   460.4  817.83   476.3  815.84
   508.2  825.58  552.86831.1259  554.39831.3593     608   839.3   663.8  842.21
#Mann= 11 ,-1 , 0
       0     .06       0  150.28    .016       0  205.11     .08       0
  235.45    .016       0  242.98     .12       0   280.8    .016       0
  281.91     .12       0   346.4    .045       0   361.4     .12       0
  552.86    .016       0  554.39     .12       0
#XS Ineff= 2 , 0
          207.57  814.22
Permanent Ineff=
       F       F
Bank Sta=346.4,361.4
XS Rating Curve= 0 ,0
Exp/Cntr=0.3,0.1

Type RM Length L Ch R = 1 ,21192.6 ,189.2,190.6,191.7
XS GIS Cut Line= 3
     1740417.373      400871.854     1740688.206      401084.093
     1740869.196      401141.385
#Sta/Elev= 30
       0   831.6    9.53828.8673    23.7  824.13   39.09822.6427    51.4  820.37
   57.41817.5095    63.3  814.16    67.2  813.07  105.29810.9212   118.6  809.31
     178  808.17   229.4  805.91   248.1  803.46   257.1     803     265  803.42
   280.8  808.26   292.7  813.66   316.4  827.04   320.4  831.25   332.2  852.98
   336.2  857.34   367.8  869.05   383.6  876.14   399.5   879.4   431.1  889.97
   450.9  898.81   458.8   901.3   494.4  915.86   522.1  930.65   533.9   931.7
#Mann= 7 ,-1 , 0
       0     .06       0    9.53     .12       0   39.09     .06       0
   57.41    .016       0  105.29     .12       0   248.1    .045       0
     265     .12       0
#XS Ineff= 2 , 0
       0     135  817.14               0
Permanent Ineff=
       F       F
Bank Sta=248.1,265
XS Rating Curve= 0 ,0
Exp/Cntr=0.3,0.1