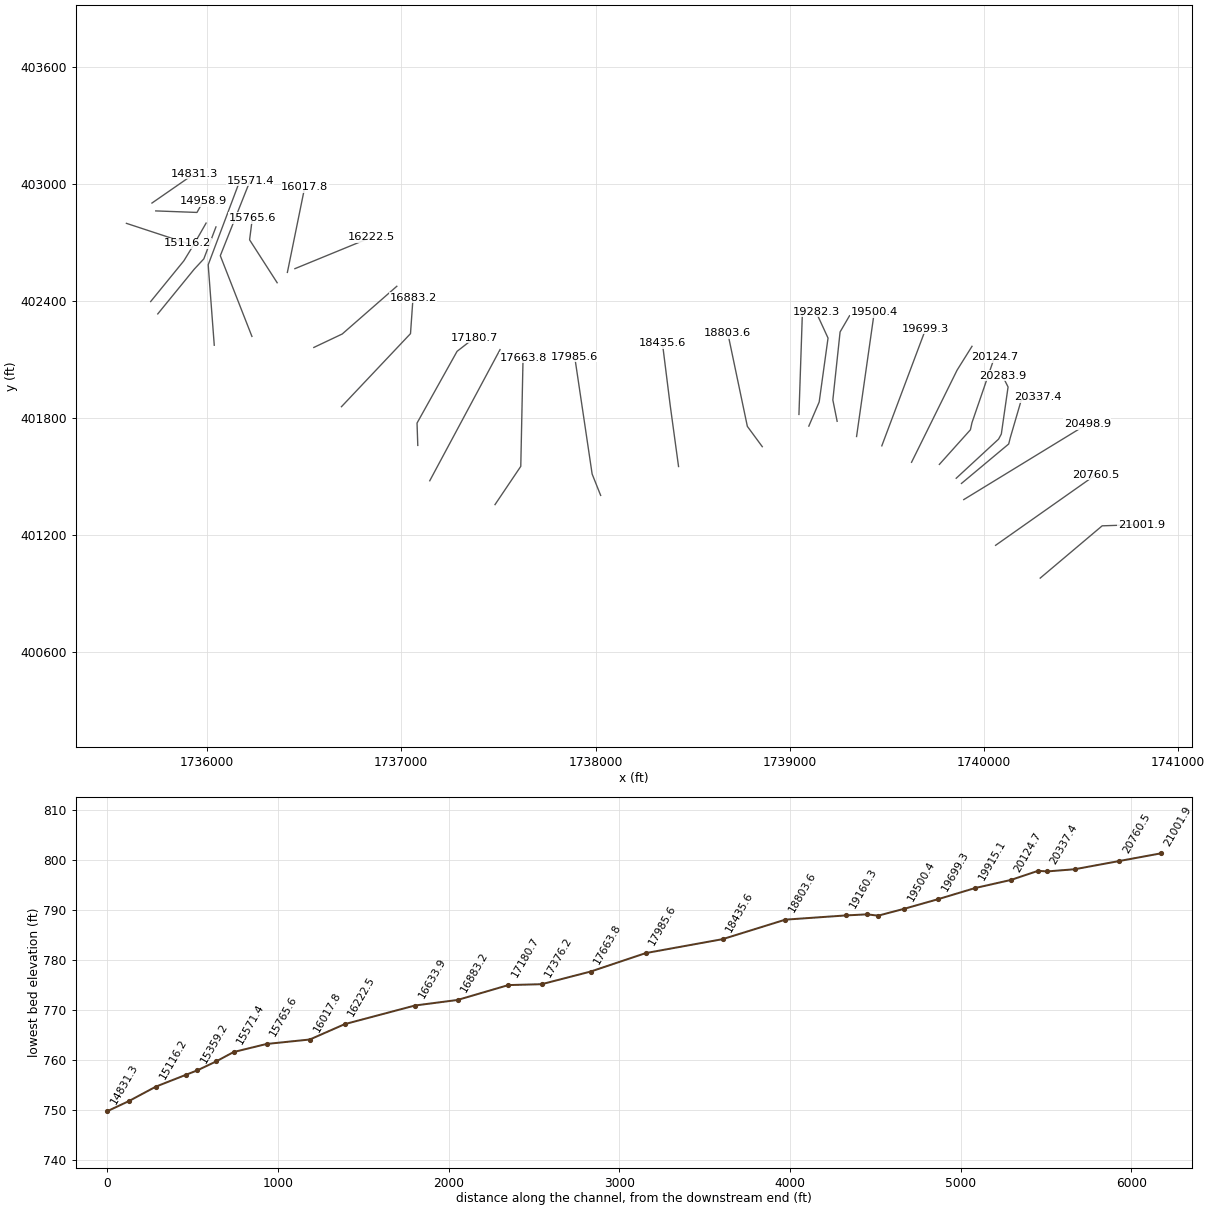
HEC-RAS study ROCKCK.prj: ROCKCK

--- ROCKCK.g01 (geometry) --- (continued)

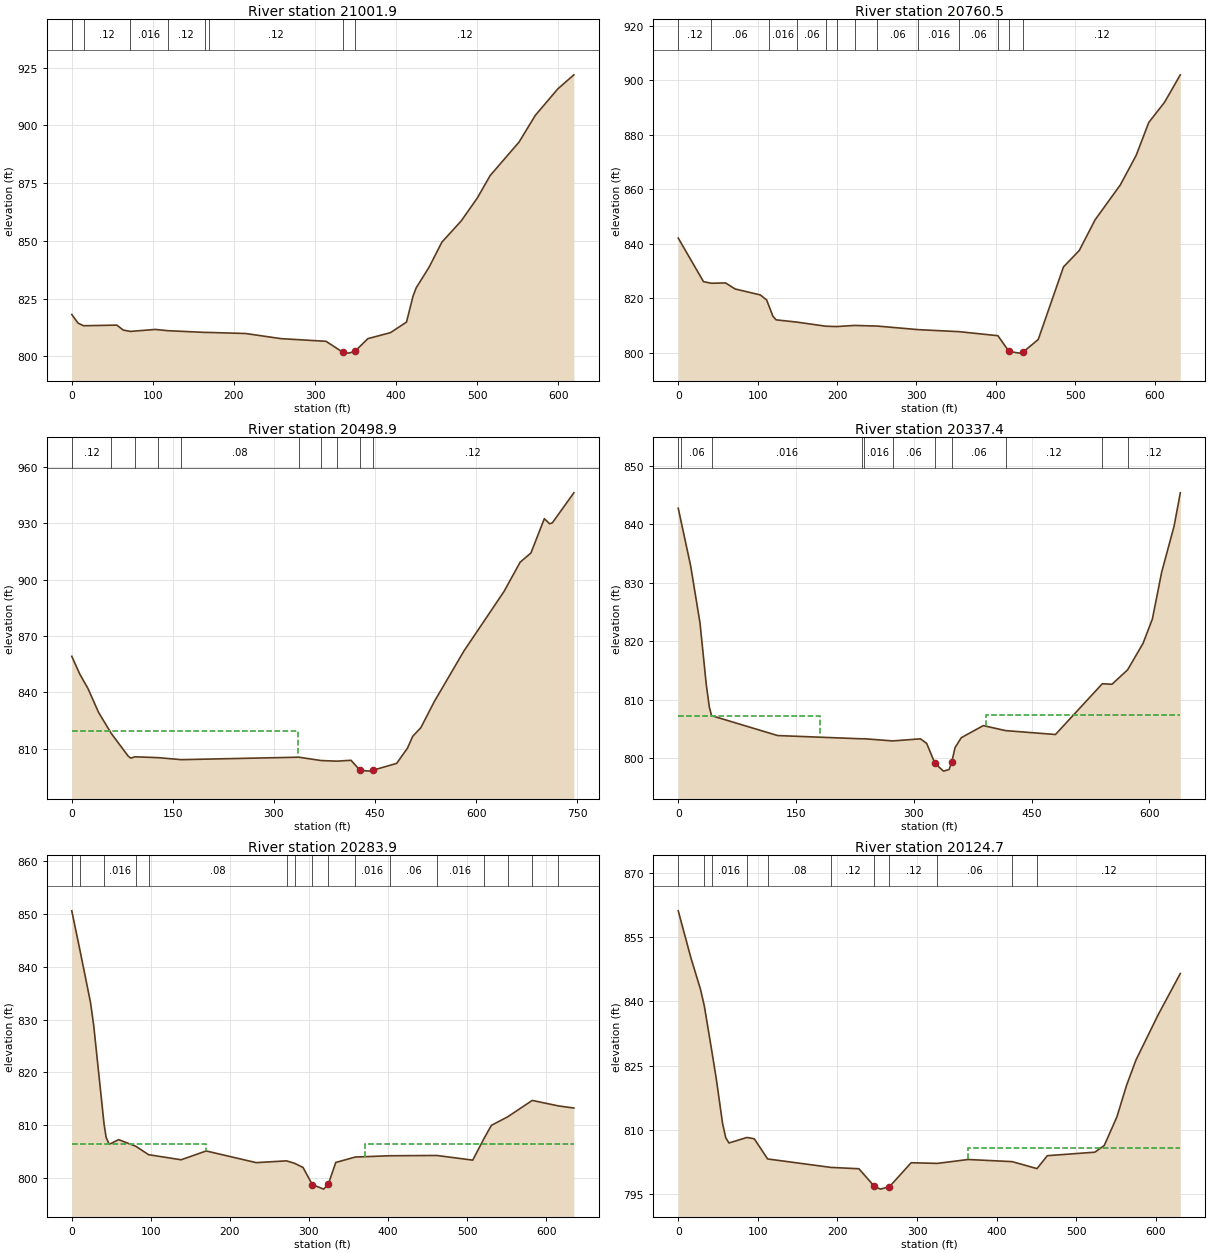
Type RM Length L Ch R = 1 ,21001.9 ,244.7,241.5,238.1
XS GIS Cut Line= 3
     1740289.287      400978.867     1740608.297      401247.096
     1740810.618       401253.63
#Sta/Elev= 30
       0  818.09     7.9  814.33   14.61813.2329    55.6  813.51    63.5  811.36
   72.32810.7791   103.2  811.64  118.21811.0922  164.11810.3533  168.97810.3373
   214.4  809.87     258  807.65   313.6  806.49   334.2  801.76   341.4  801.37
   349.2  802.15   365.2  807.65     393  810.24   412.8  814.81   420.8  825.97
   424.7  829.61   440.6  838.56   456.5  849.47   480.3  858.66   500.1  868.56
     516  878.31   551.7  892.85   571.6  904.35   599.4  915.85   619.2  921.95
#Mann= 8 ,-1 , 0
       0     .06       0   14.61     .12       0   72.32    .016       0
  118.21     .12       0  164.11     .06       0  168.97     .12       0
   334.2    .045       0   349.2     .12       0
Bank Sta=334.2,349.2
XS Rating Curve= 0 ,0
Exp/Cntr=0.3,0.1

Type RM Length L Ch R = 1 ,20760.5 ,263.4,261.6,259.1
XS GIS Cut Line= 2
     1740059.623      401147.126     1740577.127      401510.334
#Sta/Elev= 30
       0  842.08    31.8  826.08   41.66825.4924    59.6  825.61    71.6   823.4
   103.4   821.2   111.3  819.36  113.83817.4625   119.3  813.33   123.3  812.06
  149.91811.2146     186809.7215  199.43809.6016  222.08 810.014  250.84809.7772
  302.25808.4689  353.67807.7294   402.5806.2462   416.5  800.48   429.4  799.85
     434 800.176   453.3  804.85   485.1  831.49     505  837.53   524.9  848.77
   556.7   861.6   576.6  872.41   592.5  884.51   612.4  891.93   632.2  901.98
#Mann= 13 ,-1 , 0
       0     .12       0   41.66     .06       0  113.83    .016       0
  149.91     .06       0     186     .12       0  199.43     .06       0
  222.08     .12       0  250.84     .06       0  302.25    .016       0
  353.67     .06       0   402.5     .12       0   416.5    .045       0
     434     .12       0
Bank Sta=416.5,434
XS Rating Curve= 0 ,0
Exp/Cntr=0.3,0.1

Type RM Length L Ch R = 1 ,20498.9 ,143.8,161.5,190.7
XS GIS Cut Line= 2
     1739895.778      401381.684     1740532.008      401769.484
#Sta/Elev= 30
       0  859.19      12  849.68    23.9   842.2    39.8  829.39   58.88818.0944
    83.7  806.19    87.7  805.07   93.47805.8138  128.06805.3588  162.65804.2944
  336.94805.6036  370.18803.8195  393.68803.4946   414.4  803.96   427.9  798.62
   442.3   798.2   446.3  798.62   482.1  802.31   498.1  810.35     506  816.71
     518  821.26   537.9  835.07   581.7  861.87   641.5  893.67   665.4   909.2
   681.4  914.08   701.3  932.32   709.2  929.62   713.2  930.12   745.1  946.06
#Mann= 10 ,-1 , 0
       0     .12       0   58.88     .06       0   93.47    .016       0
  128.06     .06       0  162.65     .08       0  336.94     .12       0
  370.18     .08       0  393.68     .12       0   427.9    .045       0
   446.3     .12       0
#XS Ineff= 2 , 0
       0     335  819.26               0
Permanent Ineff=
       F       F
Bank Sta=427.9,446.3
XS Rating Curve= 0 ,0
Exp/Cntr=0.3,0.1

Type RM Length L Ch R = 1 ,20337.4 ,58.4,53.5,53.3
XS GIS Cut Line= 5
     1739883.894      401464.582     1740127.091      401667.012
     1740134.922      401698.147     1740192.195      401893.792
     1740278.094      401907.678
#Sta/Elev= 30
       0   842.7    4.02840.1976    15.8  832.86    27.7  823.11    35.6  812.69
    39.6  808.71   42.45807.2411   126.6  803.84  234.59803.2792  236.87803.2967
  273.02802.9236   308.5  803.28   316.4   802.5   326.9  799.09   337.8  797.76
     345  798.04   348.5   799.4   352.5  801.78   360.5  803.48   388.5  805.54
  416.93 804.686   480.4  804.02  540.03812.6922   552.4  812.61  572.32815.0815
   591.9  819.59   603.8  823.75   615.7  831.79   631.5  839.65   639.4  845.33
#Mann= 11 ,-1 , 0
       0     .12       0    4.02     .06       0   42.45    .016       0
  234.59     .08       0  236.87    .016       0  273.02     .06       0
   326.9    .045       0   348.5     .06       0  416.93     .12       0
  540.03    .016       0  572.32     .12       0
#XS Ineff= 2 , 0
       0     180  807.22     392       0  807.37
Permanent Ineff=
       F       F
Bank Sta=326.9,348.5
XS Rating Curve= 0 ,0
Exp/Cntr=0.3,0.1

Type RM Length L Ch R = 1 ,20283.9 ,149,159.2,158.3
XS GIS Cut Line= 5
     1739856.909      401491.231     1740075.008      401691.969
     1740089.114      401718.011     1740123.799      401959.565
     1740094.539       402017.49
#Sta/Elev= 30
       0  850.59    9.97843.4103    23.7  833.24    27.7  828.94   40.87810.1616
    43.5  807.65    47.4  806.37    59.3  807.25   81.01805.9991   97.19804.4026
   138.3  803.44     170  805.11   233.2   802.9  271.64803.2326  281.72802.7768
   292.5  801.98   304.2  798.74   318.6  797.88  324.57 798.856   333.9  802.93
  358.54803.9574  402.13804.1998   461.8804.2541   507.1  803.37  521.48807.4898
   530.7  809.96  551.32811.5726  582.37814.6832  615.46813.6412     635  813.24
#Mann= 16 ,-1 , 0
       0     .12       0    9.97     .06       0   40.87    .016       0
   81.01     .06       0   97.19     .08       0  271.64     .12       0
  281.72    .016       0   304.2    .045       0  324.57     .12       0
  358.54    .016       0  402.13     .06       0   461.8    .016       0
  521.48     .08       0  551.32     .06       0  582.37     .08       0
  615.46     .12       0
#XS Ineff= 2 , 0
       0     170  806.43  371.12       0  806.43
Permanent Ineff=
       F       F
Bank Sta=304.2,324.57
XS Rating Curve= 0 ,0
Exp/Cntr=0.3,0.1

Type RM Length L Ch R = 1 ,20124.7 ,210.2,209.6,202.7
XS GIS Cut Line= 4
     1739770.149      401562.221     1739929.906      401739.729
     1739938.098      401776.595     1740053.524      402111.127
#Sta/Elev= 30
       0  861.22    15.9  850.22    27.9  842.88   32.79838.9123    42.2 828.348
    47.8  821.87    55.7  811.39    59.7  808.07    63.7  806.86   86.35808.1494
    95.5  807.84  112.26803.1146  191.73801.1374   226.9  800.82   246.4  796.68
   253.9  796.05   265.2   796.6   292.5  802.23  325.53 802.077   364.1  802.99
  419.26 802.489  450.51800.8546   463.5  803.88   523.1   804.7     535  806.27
   550.9  812.98   562.9   820.3   574.8  826.28   602.6  836.85   630.5  846.54
#Mann= 11 ,-1 , 0
       0     .12       0   32.79     .06       0    42.2    .016       0
   86.35     .06       0  112.26     .08       0  191.73     .12       0
   246.4    .045       0   265.2     .12       0  325.53     .06       0
  419.26    .016       0  450.51     .12       0
#XS Ineff= 2 , 0
       0                   364.1       0  805.61
Permanent Ineff=
       F       F
Bank Sta=246.4,265.2
XS Rating Curve= 0 ,0
Exp/Cntr=0.3,0.1

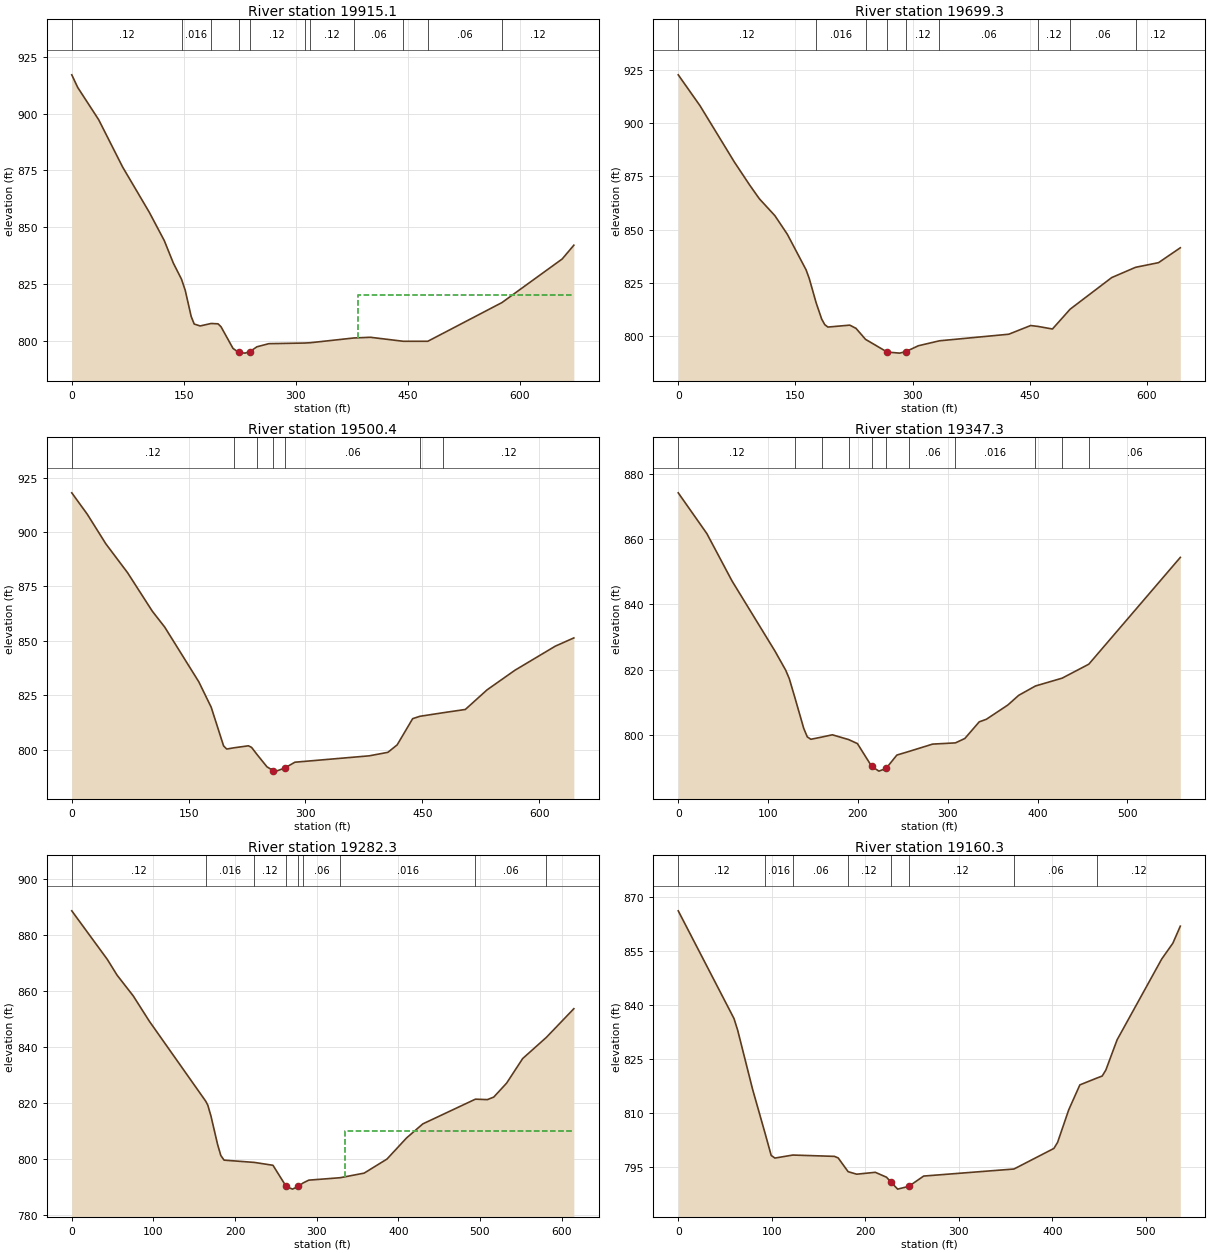
Type RM Length L Ch R = 1 ,19915.1 ,211,215.8,221.6
XS GIS Cut Line= 3
     1739626.942      401573.089     1739861.317      402045.746
     1739938.139      402168.141
#Sta/Elev= 30
       0  917.19       8   911.6      36  897.41      68  876.57   103.9  856.49
   123.9  844.03   135.9   834.2  146.94827.0052   151.9  822.13   159.9  810.55
   163.9  807.26   171.9  806.42  186.45807.5023   195.8  807.36   199.8  806.06
   215.8  796.54   223.2  794.75   231.8  794.43   238.2  795.03   247.8  797.22
   263.8   798.6  311.77798.8802  319.43799.0189  377.71801.1157   399.7  801.42
  443.64799.6628  476.61799.6566  575.87816.7313   656.5  835.96   672.1  842.04
#Mann= 11 ,-1 , 0
       0     .12       0  146.94    .016       0  186.45     .12       0
   223.2    .045       0   238.2     .12       0  311.77     .06       0
  319.43     .12       0  377.71     .06       0  443.64    .016       0
  476.61     .06       0  575.87     .12       0
#XS Ineff= 2 , 0
       0                   383.7       0     820
Permanent Ineff=
       F       F
Bank Sta=223.2,238.2
XS Rating Curve= 0 ,0
Exp/Cntr=0.3,0.1

Type RM Length L Ch R = 1 ,19699.3 ,190.5,199,206.9
XS GIS Cut Line= 2
      1739473.88      401657.568     1739700.443      402259.131
#Sta/Elev= 30
       0  922.58      28  908.04    71.9  881.71    91.8  870.77   103.8  864.55
   123.8  856.58   139.7  847.88   163.7  831.22   167.7   827.2  176.64815.7002
   183.7  808.13   187.6  805.56   191.6  804.42   219.6  805.32   227.6  803.82
  239.77798.6677   267.5  792.71   283.5  792.21   291.5  792.93   307.4  795.66
  334.45797.9864   423.2  801.07   451.2  805.14  460.69804.7128   479.1  803.51
   501.7 812.785     555  827.61  585.51832.4128   614.9  834.59   642.8  841.56
#Mann= 9 ,-1 , 0
       0     .12       0  176.64    .016       0  239.77     .12       0
   267.5    .045       0   291.5     .12       0  334.45     .06       0
  460.69     .12       0   501.7     .06       0  585.51     .12       0
Bank Sta=267.5,291.5
XS Rating Curve= 0 ,0
Exp/Cntr=0.3,0.1

Type RM Length L Ch R = 1 ,19500.4 ,151.7,153,154.4
XS GIS Cut Line= 2
     1739343.889      401705.311     1739435.035      402343.332
#Sta/Elev= 30
       0  917.97    19.9  908.16    43.8  894.54    71.6  881.34   103.4  863.66
   119.4  856.32   163.1  831.24     179  819.58   194.9  801.85   198.9  800.41
  208.27800.9891   226.8   801.9   230.8  801.18   238.1797.7855   250.6  792.25
   258.5  790.53   262.6  790.28   273.5  791.72   286.4  794.37   381.9   797.3
   405.8  798.91   417.7  802.32   437.6  814.36  446.95815.4439  476.78 817.082
   505.2  818.57   533.1  827.57   568.9  836.57   620.6   847.6   644.5   851.4
#Mann= 7 ,-1 , 0
       0     .12       0  208.27    .016       0   238.1     .12       0
   258.5    .045       0   273.5     .06       0  446.95    .016       0
  476.78     .12       0
Bank Sta=258.5,273.5
XS Rating Curve= 0 ,0
Exp/Cntr=0.3,0.1

Type RM Length L Ch R = 1 ,19347.3 ,66,65,63.7
XS GIS Cut Line= 4
     1739243.877      401783.419     1739221.742      401892.967
     1739259.068      402241.926     1739307.679      402325.086
#Sta/Elev= 30
       0  874.09    31.9   861.6    59.9  847.11   107.8   825.6   119.7  819.77
   123.7  817.16  130.39810.9207   139.7  802.01   143.7  799.38   147.7  798.65
  160.09799.3406   171.6  800.02   189.8 798.552   199.5  797.33   215.4  790.36
   223.4   788.9   231.4  789.72   243.4  793.81  257.22 794.954   283.2  797.17
  308.61797.5468   319.1  798.89   335.1  803.98   343.1  804.78     367  809.14
     379  812.09  397.72814.9642  427.43817.3588  457.13 821.636     559  854.32
#Mann= 11 ,-1 , 0
       0     .12       0  130.39    .016       0  160.09     .06       0
   189.8    .016       0   215.4    .045       0   231.4    .016       0
  257.22     .06       0  308.61    .016       0  397.72     .06       0
  427.43     .12       0  457.13     .06       0
Bank Sta=215.4,231.4
XS Rating Curve= 0 ,0
Exp/Cntr=0.3,0.1

Type RM Length L Ch R = 1 ,19282.3 ,117.7,122,125.7
XS GIS Cut Line= 4
     1739098.044      401758.679     1739151.429      401882.377
     1739197.002      402210.502     1739134.502      402345.919
#Sta/Elev= 30
       0  888.62    43.6  871.24    55.5  865.64    75.3  858.22    95.1  849.14
  164.12820.5784   166.7  819.14   170.6   815.2   178.6  805.18   182.6  801.19
   186.6  799.52  223.76798.7048   246.5  797.68   262.7  790.11   270.4  789.16
   277.7  790.17  283.39 791.368   290.4  792.37   328.9 793.239   358.2  794.88
   386.2  799.91   410.1  807.44   430.1  812.48   494.5  821.31   509.2  821.15
     517  822.06   532.7  827.03   552.4  835.82  581.48843.4078   615.1  853.64
#Mann= 9 ,-1 , 0
       0     .12       0  164.12    .016       0  223.76     .12       0
   262.7    .045       0   277.7     .12       0  283.39     .06       0
   328.9    .016       0   494.5     .06       0  581.48     .12       0
#XS Ineff= 2 , 0
       0                     335       0     810
Permanent Ineff=
       F       F
Bank Sta=262.7,277.7
XS Rating Curve= 0 ,0
Exp/Cntr=0.3,0.1

Type RM Length L Ch R = 1 ,19160.3 ,347.3,356.7,366
XS GIS Cut Line= 2
     1739047.263      401818.575     1739065.492      402355.033
#Sta/Elev= 30
       0  866.08    59.6  836.24    63.6  832.95    79.5  816.62   92.97804.3194
    99.4  798.28   103.4  797.56  122.52798.3947     167  798.03     171   797.6
  181.63 793.788   190.8  793.09   210.7  793.61   222.7  792.25     227  791.01
   234.6  788.95   246.5  789.72   262.4  792.57  358.94794.5239   401.6  800.22
   405.6  801.91   417.5  810.93   429.4  817.84   447.6819.7347   453.3   820.3
   457.2  821.96   469.2  830.32   516.9  852.72   528.8  857.09   536.8  861.83
#Mann= 8 ,-1 , 0
       0     .12       0   92.97    .016       0  122.52     .06       0
  181.63     .12       0     227    .045       0   246.5     .12       0
  358.94     .06       0   447.6     .12       0
Bank Sta=227,246.5
XS Rating Curve= 0 ,0
Exp/Cntr=0.3,0.1

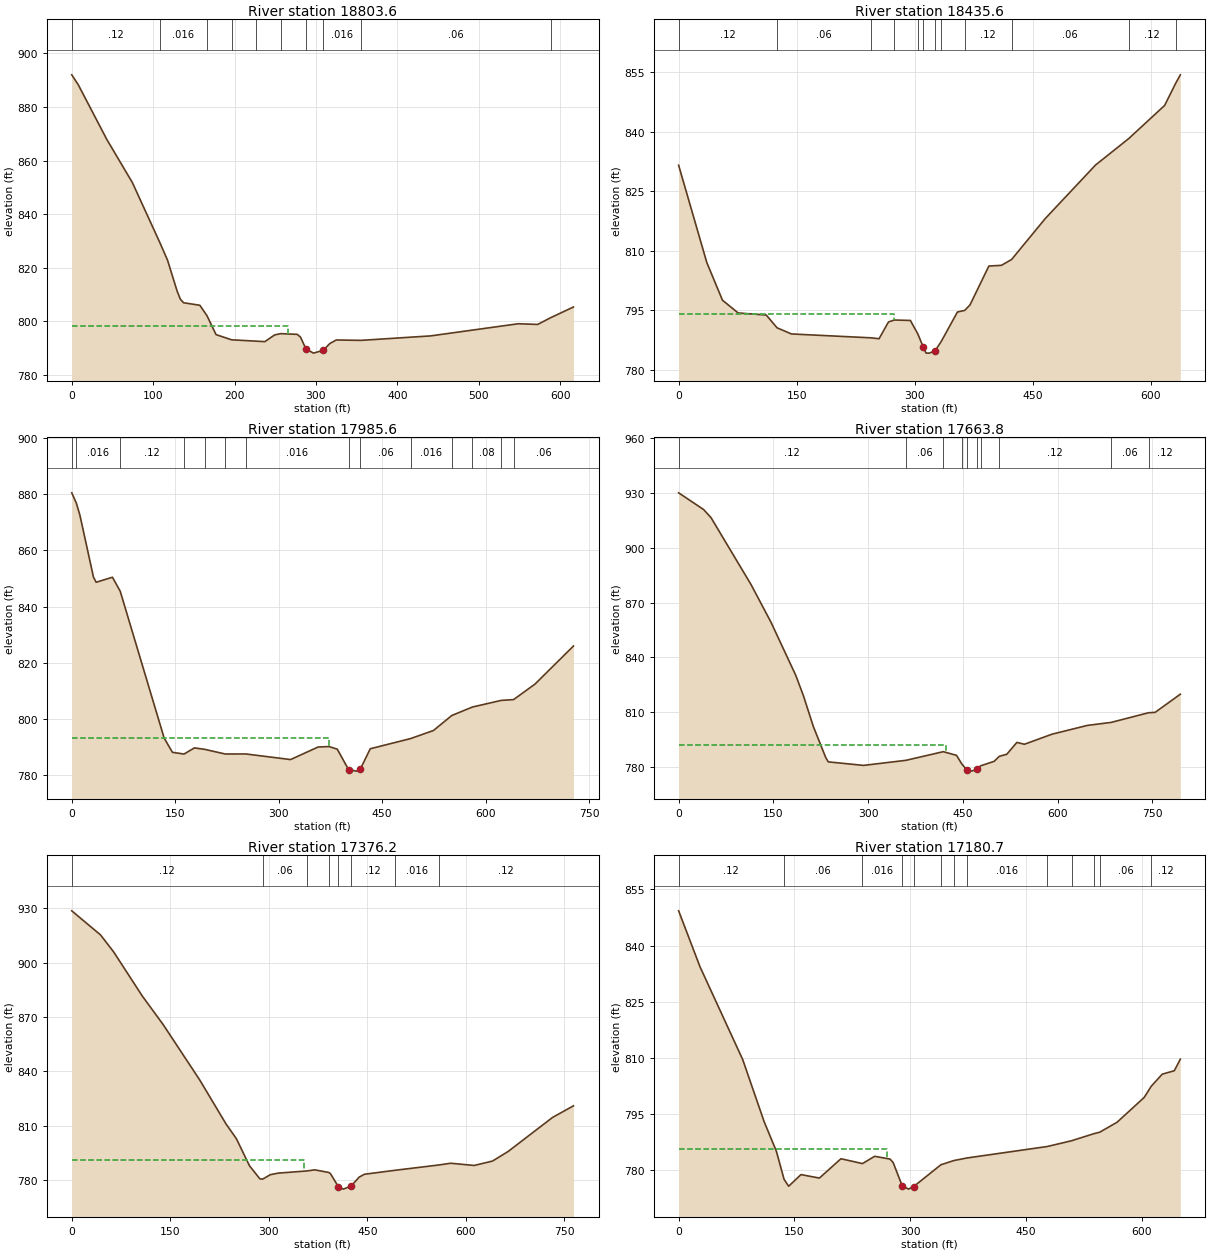
Type RM Length L Ch R = 1 ,18803.6 ,370.6,368,364.9
XS GIS Cut Line= 3
     1738858.461      401653.211     1738781.638      401757.377
     1738681.377       402233.94
#Sta/Elev= 30
       0  892.02     7.8  888.43    43.1  867.88    74.5  851.78  108.31829.3262
   117.7   822.8   129.4  811.32   133.4  808.27   137.4  806.91   157.4  805.97
   166.2 802.052   177.3  795.01  196.38793.0737  226.56792.5658   237.2  792.39
   249.2  794.88  256.74795.3727   277.1  795.11   281.1  794.06   287.8  789.62
   297.1   788.1   309.1  789.17     317  791.67     325  793.01  355.43792.8654
   440.8  794.53   548.6  799.07   572.5  798.82  588.74 801.377   616.4  805.32
#Mann= 10 ,-1 , 0
       0     .12       0  108.31    .016       0   166.2     .12       0
  196.38    .016       0  226.56     .12       0  256.74    .016       0
   287.8    .045       0   309.1    .016       0  355.43     .06       0
  588.74     .12       0
#XS Ineff= 2 , 0
          265.98  798.21
Permanent Ineff=
       F       F
Bank Sta=287.8,309.1
XS Rating Curve= 0 ,0
Exp/Cntr=0.3,0.1

Type RM Length L Ch R = 1 ,18435.6 ,449.5,450,450.9
XS GIS Cut Line= 3
     1738427.454      401551.317     1738384.244      401866.756
      1738344.54      402183.427
#Sta/Elev= 30
       0  831.51    35.8  807.01    55.7  797.52    75.6  794.31   111.4  793.78
  125.06790.5693   143.3  789.02   244.3788.0437   254.7  787.82   266.6  792.03
  274.11792.5276   294.5  792.42  303.93789.0317   310.9  785.69   314.4   784.2
   318.4  784.19   325.9  784.77  333.71787.1395   354.3  794.55  363.48794.9456
   370.2  796.32   394.2  806.12   410.1   806.3  423.01807.7543     466  818.11
   529.8  831.57  571.85838.2115   617.6  846.58  631.38852.0709   637.5  854.28
#Mann= 12 ,-1 , 0
       0     .12       0  125.06     .06       0   244.3     .08       0
  274.11    .016       0  303.93     .06       0   310.9    .045       0
   325.9     .06       0  333.71    .016       0  363.48     .12       0
  423.01     .06       0  571.85     .12       0  631.38     .06       0
#XS Ineff= 2 , 0
          274.07  793.98
Permanent Ineff=
       F       F
Bank Sta=310.9,325.9
XS Rating Curve= 0 ,0
Exp/Cntr=0.3,0.1

Type RM Length L Ch R = 1 ,17985.6 ,328.2,321.9,315.5
XS GIS Cut Line= 4
     1738026.429       401403.21     1737982.545      401512.836
     1737939.745      401800.521      1737892.64      402115.518
#Sta/Elev= 30
       0  880.52    6.67876.8665    11.8   872.6    31.5   850.5    35.4  848.67
      59  850.46    70.3845.4605     134  793.16     146  788.09  162.82787.4882
   177.8  789.67  192.68789.1644  222.47787.4993   252.4 787.515   317.3  785.52
   357.1  789.98   373.1  790.15     385  789.22   401.4  781.92   412.9   781.4
  418.32782.0816   432.8  789.37  491.29792.9952   524.4  795.86  551.02801.2108
  580.88804.2295  622.77806.5935  640.61806.8759   671.7  812.41   727.4  825.96
#Mann= 14 ,-1 , 0
       0     .12       0    6.67    .016       0    70.3     .12       0
  162.82     .06       0  192.68     .12       0  222.47     .06       0
   252.4    .016       0   401.4    .045       0  418.32     .06       0
  491.29    .016       0  551.02     .12       0  580.88     .08       0
  622.77    .016       0  640.61     .06       0
#XS Ineff= 2 , 0
          372.79  793.32
Permanent Ineff=
       F       F
Bank Sta=401.4,418.32
XS Rating Curve= 0 ,0
Exp/Cntr=0.3,0.1

Type RM Length L Ch R = 1 ,17663.8 ,305.3,287.5,269.8
XS GIS Cut Line= 3
     1737482.561      401355.919     1737615.223      401552.256
     1737626.942      402109.548
#Sta/Elev= 30
       0  930.15    39.5  921.02    51.3  916.55   114.5     880   146.1  859.37
   185.6  830.09   197.5  819.12   213.3  802.16     233  785.09     237  782.78
   292.7  780.85  359.96783.6279  419.04788.3665     440  786.36  448.58781.5494
   456.8  778.23   463.9  777.71   471.8  778.71  478.12780.6054   499.7  783.09
  507.67785.8078   519.6  786.95   535.6  793.44   547.5  792.43   591.3  797.95
     647  802.74  684.92 804.407     744809.6845   754.6  809.92   794.4  819.85
#Mann= 10 ,-1 , 0
       0     .12       0  359.96     .06       0  419.04    .016       0
  448.58     .12       0   456.8    .045       0   471.8     .12       0
  478.12     .06       0  507.67     .12       0  684.92     .06       0
     744     .12       0
#XS Ineff= 2 , 0
          424.13  791.91
Permanent Ineff=
       F       F
Bank Sta=456.8,471.8
XS Rating Curve= 0 ,0
Exp/Cntr=0.3,0.1

Type RM Length L Ch R = 1 ,17376.2 ,196.1,195.6,194.9
XS GIS Cut Line= 2
     1737146.623      401478.315     1737508.452      402151.214
#Sta/Elev= 30
       0  928.47    43.8  915.22    63.7   905.9   107.4  881.56   139.3  865.77
     195  835.24   234.8  811.15   250.7  802.96   270.6  788.08   286.5  780.83
  290.65  780.67   302.4  783.12   314.4  783.98  357.72785.1786   370.1  785.79
  391.26784.3625   393.9  783.76   405.9  776.57   413.8  775.17   425.8  777.01
   437.7  781.79   445.7  783.36  491.86785.5237  558.93788.4644     577  789.43
   612.8  788.21   640.7  790.62   664.5   795.9   732.2  814.66     764  821.05
#Mann= 8 ,-1 , 0
       0     .12       0  290.65     .06       0  357.72    .016       0
  391.26     .12       0   405.9    .045       0   425.8     .12       0
  491.86    .016       0  558.93     .12       0
#XS Ineff= 2 , 0
          353.27  791.45
Permanent Ineff=
       F       F
Bank Sta=405.9,425.8
XS Rating Curve= 0 ,0
Exp/Cntr=0.3,0.1

Type RM Length L Ch R = 1 ,17180.7 ,307.4,297.5,287.9
XS GIS Cut Line= 4
     1737085.023      401659.721     1737081.117      401774.304
     1737287.248      402142.377      1737376.69      402211.804
#Sta/Elev= 30
       0  849.26    27.7  834.32      83  809.56   110.7  793.01   126.6  785.09
  136.51777.6162   142.5  775.76   158.4  778.87   182.3  777.94   210.2   783.1
  238.07781.8075   253.9  783.75   273.8  783.01   277.8  782.09   289.4  775.94
   297.7  774.99   304.4  775.68  339.62781.4895  356.46782.6177  373.47783.3047
  477.36 786.362  508.88787.9021  537.31789.7557  545.36790.1868   567.8  792.84
   602.9  799.46  612.09802.4569   626.3  805.67   641.9  806.59   649.7  809.67
#Mann= 13 ,-1 , 0
       0     .12       0  136.51     .06       0  238.07    .016       0
   289.4    .045       0   304.4     .12       0  339.62    .016       0
  356.46     .06       0  373.47    .016       0  477.36     .06       0
  508.88    .016       0  537.31     .12       0  545.36     .06       0
  612.09     .12       0
#XS Ineff= 2 , 0
          269.58  785.82
Permanent Ineff=
       F       F
Bank Sta=289.4,304.4
XS Rating Curve= 0 ,0
Exp/Cntr=0.3,0.1

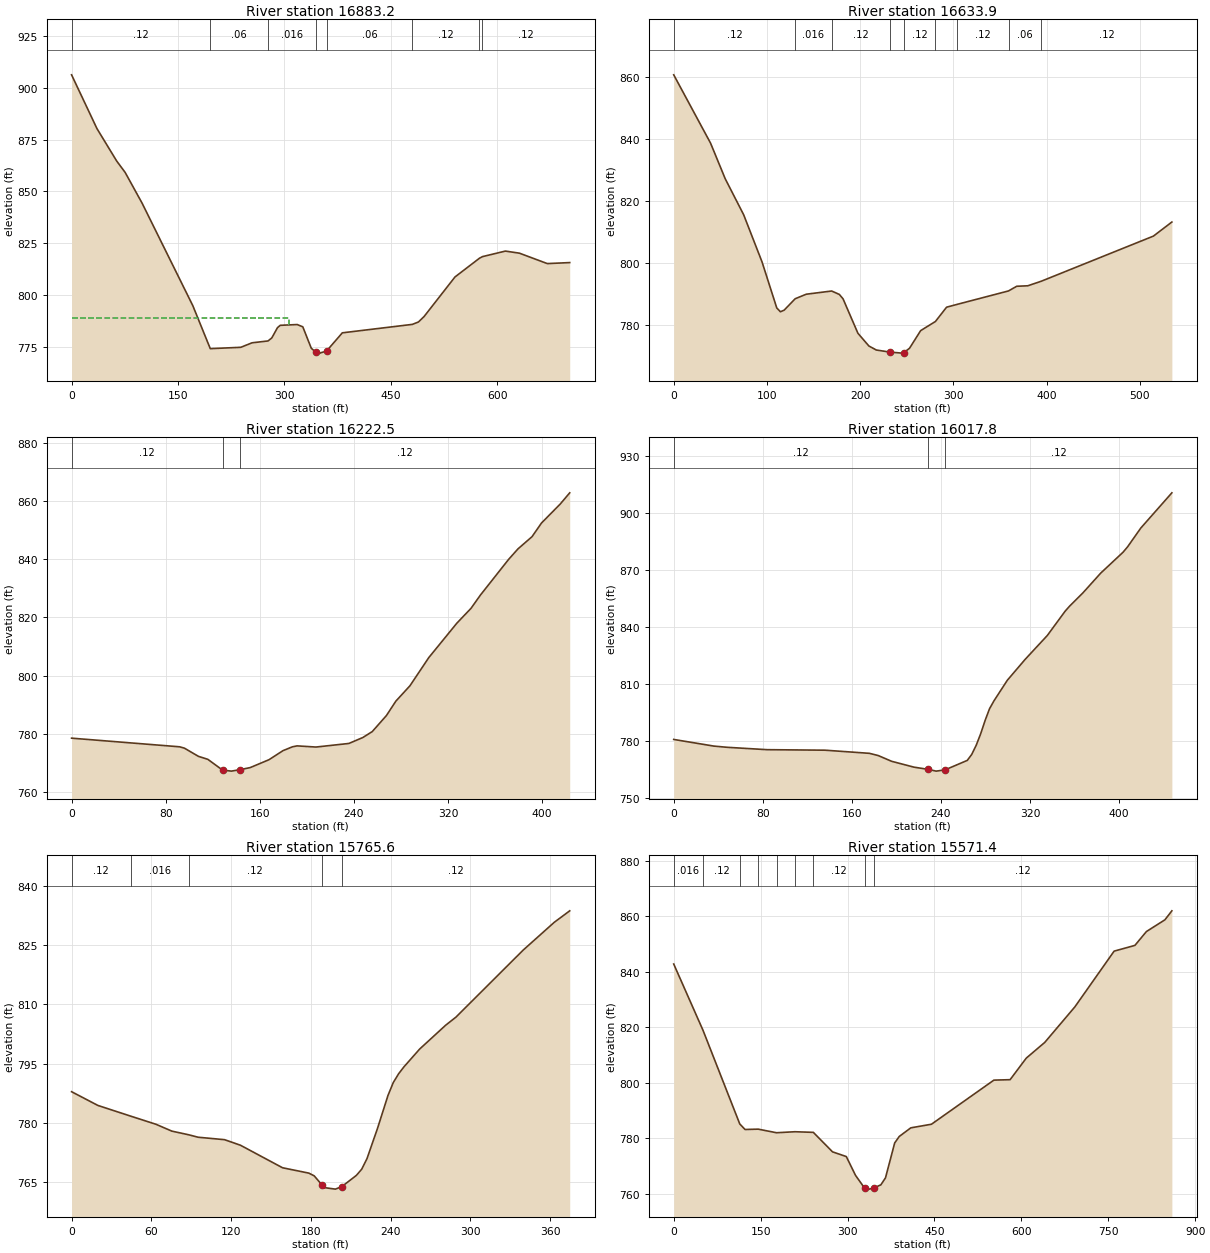
Type RM Length L Ch R = 1 ,16883.2 ,252.4,249.3,245.8
XS GIS Cut Line= 3
     1736692.046      401858.245     1737047.515      402233.245
     1737060.536      402418.141
#Sta/Elev= 30
       0  906.25    35.8   880.3    63.6  864.67    75.5  859.18    99.4  844.35
   170.9  794.89   195.5774.1652   238.5  774.82   254.4  776.99  276.89777.8835
   282.2  779.33   290.2  784.28   294.1  785.42     318   785.8   325.9   784.7
   337.8   774.4   344.5  772.36   349.8  772.01   359.5  773.07   381.6   781.8
  480.37785.8787   488.9  787.04   496.8  789.65   540.4  808.75  574.85817.7785
  579.09818.5516   611.4  821.23   631.1  820.23   670.5   815.2   702.1  815.68
#Mann= 8 ,-1 , 0
       0     .12       0   195.5     .06       0  276.89    .016       0
   344.5    .045       0   359.5     .06       0  480.37     .12       0
  574.85     .06       0  579.09     .12       0
#XS Ineff= 2 , 0
          307.06  789.18
Permanent Ineff=
       F       F
Bank Sta=344.5,359.5
XS Rating Curve= 0 ,0
Exp/Cntr=0.3,0.1

Type RM Length L Ch R = 1 ,16633.9 ,426.5,411.3,394.8
XS GIS Cut Line= 3
     1736549.867      402162.325     1736696.161      402231.431
      1736976.95      402476.127
#Sta/Elev= 30
       0   860.7    39.5  838.66    55.2  827.18      75  815.55    94.7  800.34
   110.5  785.48   114.4  784.25   118.4  784.76  130.25788.4475   142.1  789.91
  169.38790.9424   177.6  789.84   181.6  788.41   197.5  777.32   209.3   773.2
   217.3   771.9   231.9  771.23     245   770.9   246.9  771.08   252.9  772.49
   264.8  778.16  280.66781.1104   292.6  785.72  304.25786.6581  359.03790.9713
   367.8  792.47   379.7  792.63  394.16794.1016   514.4  808.66   534.2   813.2
#Mann= 9 ,-1 , 0
       0     .12       0  130.25    .016       0  169.38     .12       0
   231.9    .045       0   246.9     .12       0  280.66     .06       0
  304.25     .12       0  359.03     .06       0  394.16     .12       0
Bank Sta=231.9,246.9
XS Rating Curve= 0 ,0
Exp/Cntr=0.3,0.1

Type RM Length L Ch R = 1 ,16222.5 ,167.1,204.7,242.1
XS GIS Cut Line= 2
     1736452.462      402566.579     1736844.389      402726.735
#Sta/Elev= 30
       0  778.49    91.9  775.52    95.9  775.06   107.8  772.25   115.8  771.22
   128.3  767.54   135.8  767.17   143.3  767.68   151.8  768.38   167.8  771.09
   179.7   774.2   187.7  775.52   191.7  775.84   207.7  775.44   235.7  776.67
   247.6  778.72   255.6  780.76   267.6  786.25   275.6  791.19   287.6  796.48
   303.6  806.15   327.5  817.99   339.5  823.07   347.5  827.63   371.5   839.9
   379.4  843.48   391.4   847.7   399.4  852.37   415.4  858.92   423.4  862.74
#Mann= 3 ,-1 , 0
       0     .12       0   128.3    .045       0   143.3     .12       0
Bank Sta=128.3,143.3
XS Rating Curve= 0 ,0
Exp/Cntr=0.3,0.1

Type RM Length L Ch R = 1 ,16017.8 ,233.1,252.3,284.3
XS GIS Cut Line= 2
     1736413.694      402547.364     1736503.244       402985.85
#Sta/Elev= 30
       0  780.75      36  777.26      48  776.62    83.9  775.37   135.9   775.1
   175.8  773.45   183.8  772.26   195.8  769.25   215.8  766.18   228.7     765
   235.8  764.09   243.7  764.74   263.7  769.73   267.7  772.87   271.7  777.65
   275.7  783.67   279.7  790.69   283.7   796.9   287.7  801.07   299.7  811.88
   315.7  822.86   335.6  835.41   351.6  848.18   355.6  850.83   367.6  857.83
   383.6  868.23   403.6  879.18   407.6  881.94   419.6  891.93   447.5  910.44
#Mann= 3 ,-1 , 0
       0     .12       0   228.7    .045       0   243.7     .12       0
Bank Sta=228.7,243.7
XS Rating Curve= 0 ,0
Exp/Cntr=0.3,0.1

Type RM Length L Ch R = 1 ,15765.6 ,201.6,194.2,186.6
XS GIS Cut Line= 3
     1736361.065      402494.356     1736219.138      402714.408
     1736233.461      402826.387
#Sta/Elev= 30
       0  787.87    19.8  784.39   44.53781.6747    63.5  779.62    75.4  777.89
   88.27776.9481    95.2  776.34   115.1  775.72     127  774.32   158.7  768.61
   178.5  767.25   182.5  766.56   188.2  764.32   190.4  763.57   198.4   763.2
   203.2  763.82   214.2  766.67   218.2  768.23   222.2  770.92   230.1  778.56
     238  786.92     242   790.2     246  792.41     250  794.16   261.8  798.66
   281.3  804.68   289.1  806.75   339.7  823.73   363.1  830.77   374.7  833.67
#Mann= 5 ,-1 , 0
       0     .12       0   44.53    .016       0   88.27     .12       0
   188.2    .045       0   203.2     .12       0
Bank Sta=188.2,203.2
XS Rating Curve= 0 ,0
Exp/Cntr=0.3,0.1

Type RM Length L Ch R = 1 ,15571.4 ,110.9,101.6,89.6
XS GIS Cut Line= 3
     1736231.108      402218.922     1736068.348      402632.985
     1736221.994      403018.402
#Sta/Elev= 30
       0   842.8   50.54818.8962  114.01785.0931   123.1   783.1  145.75783.2225
  177.48781.9259  209.22782.2878  240.95 782.065   274.1  775.03   297.9  773.33
   313.8  766.54   329.7  761.88   337.6  761.58   346.3  762.08   357.5  763.13
   365.5  765.65   381.4  778.26   389.3  780.59   409.2  783.69   444.9     785
   552.6  800.91   580.6  801.07   608.5  808.85   640.4  814.52   692.3  827.32
   760.1  847.45     796  849.53   815.9  854.53   847.8  858.76   859.8     862
#Mann= 9 ,-1 , 0
       0    .016       0   50.54     .12       0  114.01     .06       0
  145.75     .12       0  177.48     .06       0  209.22    .016       0
  240.95     .12       0   329.7    .045       0   346.3     .12       0
Bank Sta=329.7,346.3
XS Rating Curve= 0 ,0
Exp/Cntr=0.3,0.1

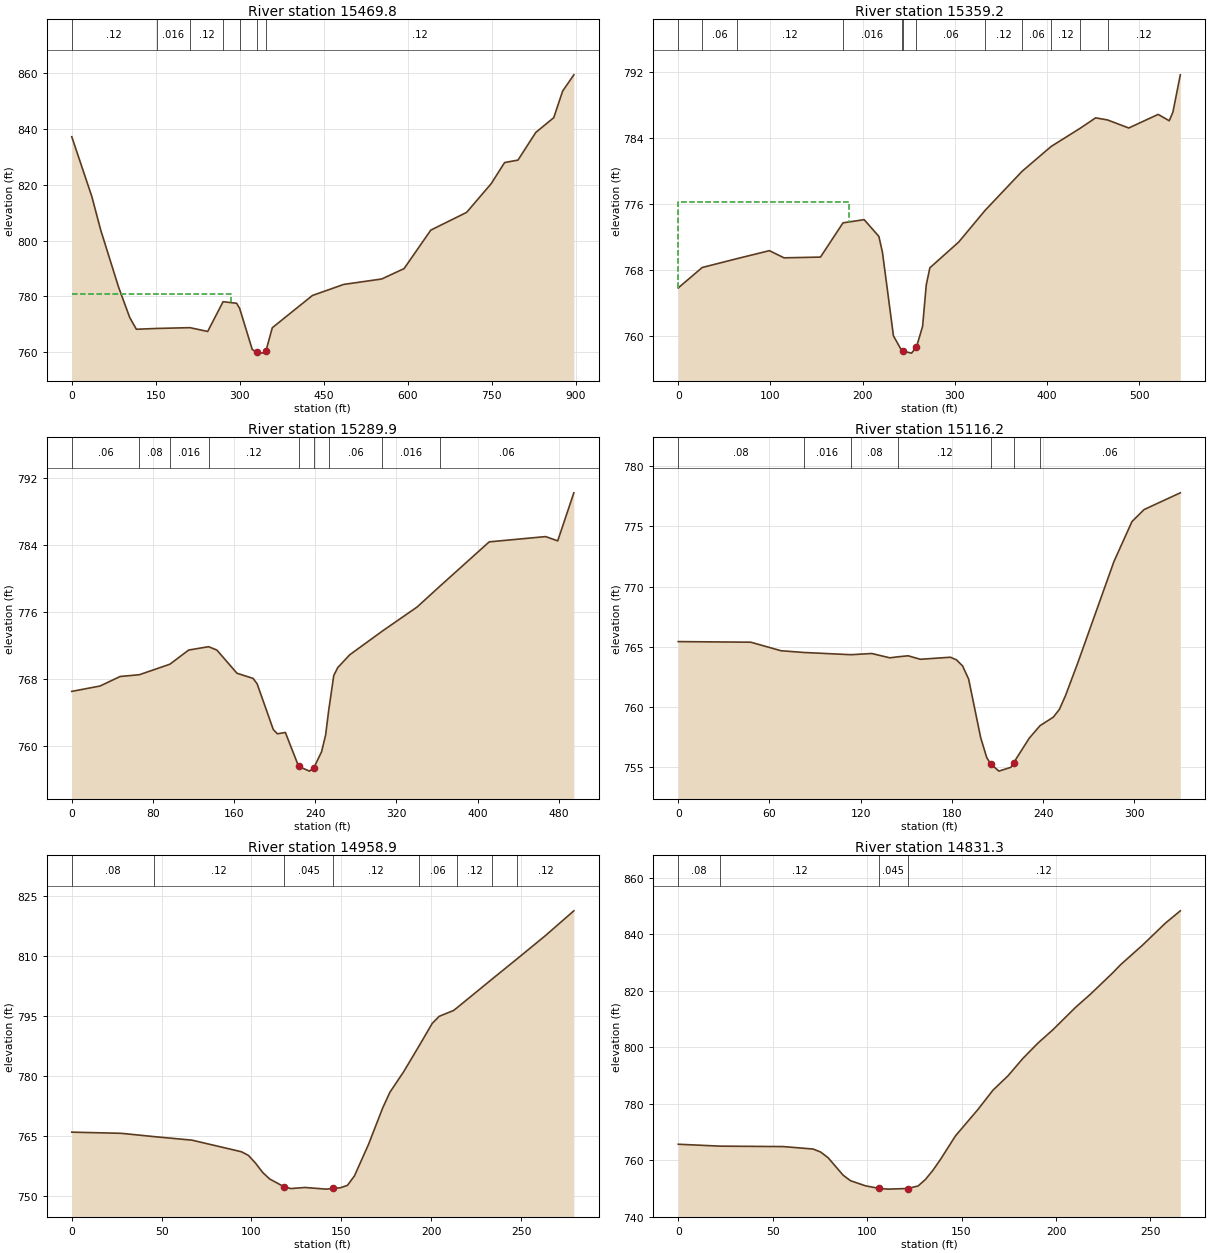
Type RM Length L Ch R = 1 ,15469.8 ,142.2,110.6,81.5
XS GIS Cut Line= 3
     1736037.248      402173.627     1736005.998      402586.388
     1736176.571      403038.211
#Sta/Elev= 30
       0  837.22    35.8  815.84    51.7   803.8    83.6  783.37   103.5  772.49
   115.4  768.26  151.84768.5504  211.08768.8306   242.8  767.47  270.32778.1334
   294.5  777.57  299.94775.7124   322.4  761.02   330.4     760   342.3  759.71
   346.8  760.45   358.2   768.8   429.9  780.36   485.8  784.32   553.6  786.26
   593.6  789.98   641.4  803.78   705.3  810.12   749.2   820.4   773.2  827.97
   797.1  828.86     829  838.78     861  844.05   876.9  853.59   896.9   859.4
#Mann= 7 ,-1 , 0
       0     .12       0  151.84    .016       0  211.08     .12       0
  270.32    .016       0  299.94     .12       0   330.4    .045       0
   346.8     .12       0
#XS Ineff= 2 , 0
           283.7  781.02
Permanent Ineff=
       F       F
Bank Sta=330.4,346.8
XS Rating Curve= 0 ,0
Exp/Cntr=0.3,0.1

Type RM Length L Ch R = 1 ,15359.2 ,69.2,69.3,69.5
XS GIS Cut Line= 4
     1735746.467      402334.448     1735934.233      402563.974
     1735983.461      402616.752     1736045.961      402780.815
#Sta/Elev= 30
       0  765.82      26 768.299   64.16769.3825    98.8  770.34   114.7  769.47
   154.2  769.56  178.63773.7137   201.6   774.1   217.5  772.07   221.4  770.14
   233.3  760.01  242.04 758.258   243.3  758.15     253  757.91   258.3  758.66
   264.9  761.16   268.9   766.2   272.8  768.26   304.1  771.39  332.56775.2151
  372.61779.9499  404.21782.9766  435.82785.1925   452.5  786.45  465.37786.1987
   488.4  785.22   520.3  786.87   532.3   786.1   536.3  787.15   544.3  791.67
#Mann= 12 ,-1 , 0
       0     .04       0      26     .06       0   64.16     .12       0
  178.63    .016       0  242.04     .06       0   243.3    .045       0
   258.3     .06       0  332.56     .12       0  372.61     .06       0
  404.21     .12       0  435.82     .06       0  465.37     .12       0
#XS Ineff= 2 , 0
          185.62  776.22
Permanent Ineff=
       F       F
Bank Sta=243.3,258.3
XS Rating Curve= 0 ,0
Exp/Cntr=0.3,0.1

Type RM Length L Ch R = 1 ,15289.9 ,219.4,173.7,128
XS GIS Cut Line= 4
     1735709.889      402397.874     1735880.848      402606.943
     1735933.981      402693.575     1735995.179      402800.346
#Sta/Elev= 30
       0  766.52    27.8  767.16    47.7   768.3    66.6768.5115   96.67769.7653
   115.2  771.46  134.83771.8626     143  771.46   162.8  768.69   178.7  768.07
   182.7  767.42   198.6  761.96   202.6  761.45   210.5  761.61   223.6  757.55
   234.3  756.99   238.6   757.4   246.2  759.31   250.2  761.32  253.23764.2742
   258.2  768.42   262.1  769.36     274   770.9  306.18773.7354   340.4  776.61
  362.67779.0759   411.4  784.39     467  785.02   478.9  784.51   494.8  790.25
#Mann= 9 ,-1 , 0
       0     .06       0    66.6     .08       0   96.67    .016       0
  134.83     .12       0   223.6    .045       0   238.6     .12       0
  253.23     .06       0  306.18    .016       0  362.67     .06       0
Bank Sta=223.6,238.6
XS Rating Curve= 0 ,0
Exp/Cntr=0.3,0.1

Type RM Length L Ch R = 1 ,15116.2 ,144.2,157.3,166.7
XS GIS Cut Line= 2
     1735585.023      402799.044     1735898.825      402696.179
#Sta/Elev= 30
       0  765.42    47.7  765.37    67.6  764.66   82.53764.5167  113.61764.3303
   127.3  764.43   139.2  764.07  144.69764.1584   151.2  764.24   159.2  763.95
     179  764.12     183   763.9     187   763.4     191   762.3   198.9  757.44
   202.9  755.77   205.6  755.23   210.9  754.65   218.8  754.97   220.6  755.35
   230.8  757.38  237.94758.4293   246.7  759.14   250.7  759.79   254.6   760.9
   262.6  763.59   286.5  772.06   298.4   775.4   306.4   776.4   330.2  777.79
#Mann= 7 ,-1 , 0
       0     .08       0   82.53    .016       0  113.61     .08       0
  144.69     .12       0   205.6    .045       0   220.6     .12       0
  237.94     .06       0
Bank Sta=205.6,220.6
XS Rating Curve= 0 ,0
Exp/Cntr=0.3,0.1

Type RM Length L Ch R = 1 ,14958.9 ,101.3,127.6,153.7
XS GIS Cut Line= 3
     1735736.065      402862.846     1735948.304      402855.033
     1735980.856      402913.627
#Sta/Elev= 30
       0  765.99    27.5   765.7   45.56764.8815    66.9  763.99    94.4   761.1
    98.3  760.19   102.3  758.24   106.2  755.95   110.1  754.31     118  752.39
   121.9  751.91   129.8  752.18   141.6  751.77   145.5  751.94   149.4   752.1
   153.4  752.71   157.3  755.06   165.2     763     173     772     177  775.91
   184.8  781.14  193.33787.5524   200.6  793.14   204.5   794.9   212.4  796.34
  214.26796.9838     234804.2172  248.04809.3228   263.6  815.04   279.4  821.22
#Mann= 8 ,-1 , 0
       0     .08       0   45.56     .12       0     118    .045       0
   145.5     .12       0  193.33     .06       0  214.26     .12       0
     234     .06       0  248.04     .12       0
Bank Sta=118,145.5
XS Rating Curve= 0 ,0
Exp/Cntr=0.3,0.1

Type RM Length L Ch R = 1 ,14831.3 ,177.4,203.1,228.2
XS GIS Cut Line= 2
     1735716.533       402903.21     1735935.284      403054.252
#Sta/Elev= 30
       0  765.61   22.06 764.933    55.6  764.78    71.4  763.91    75.4  762.85
    79.4   760.8    87.3  754.65    91.2   752.7    99.2  750.88   106.4  749.97
   111.1  749.72   121.4  749.94     127  750.84   130.9  753.16   134.9  756.45
   138.9   760.3   146.8  768.59   158.7  777.94   166.6  784.73   174.6  789.84
   182.5  796.01   190.4  801.39   198.4  806.16   210.3  814.03   218.2   818.7
   230.1  826.32   234.1   829.1     246   836.2   257.9  843.86   265.8  848.22
#Mann= 4 ,-1 , 0
       0     .08       0   22.06     .12       0   106.4    .045       0
   121.4     .12       0
Bank Sta=106.4,121.4
XS Rating Curve= 0 ,0
Exp/Cntr=0.3,0.1