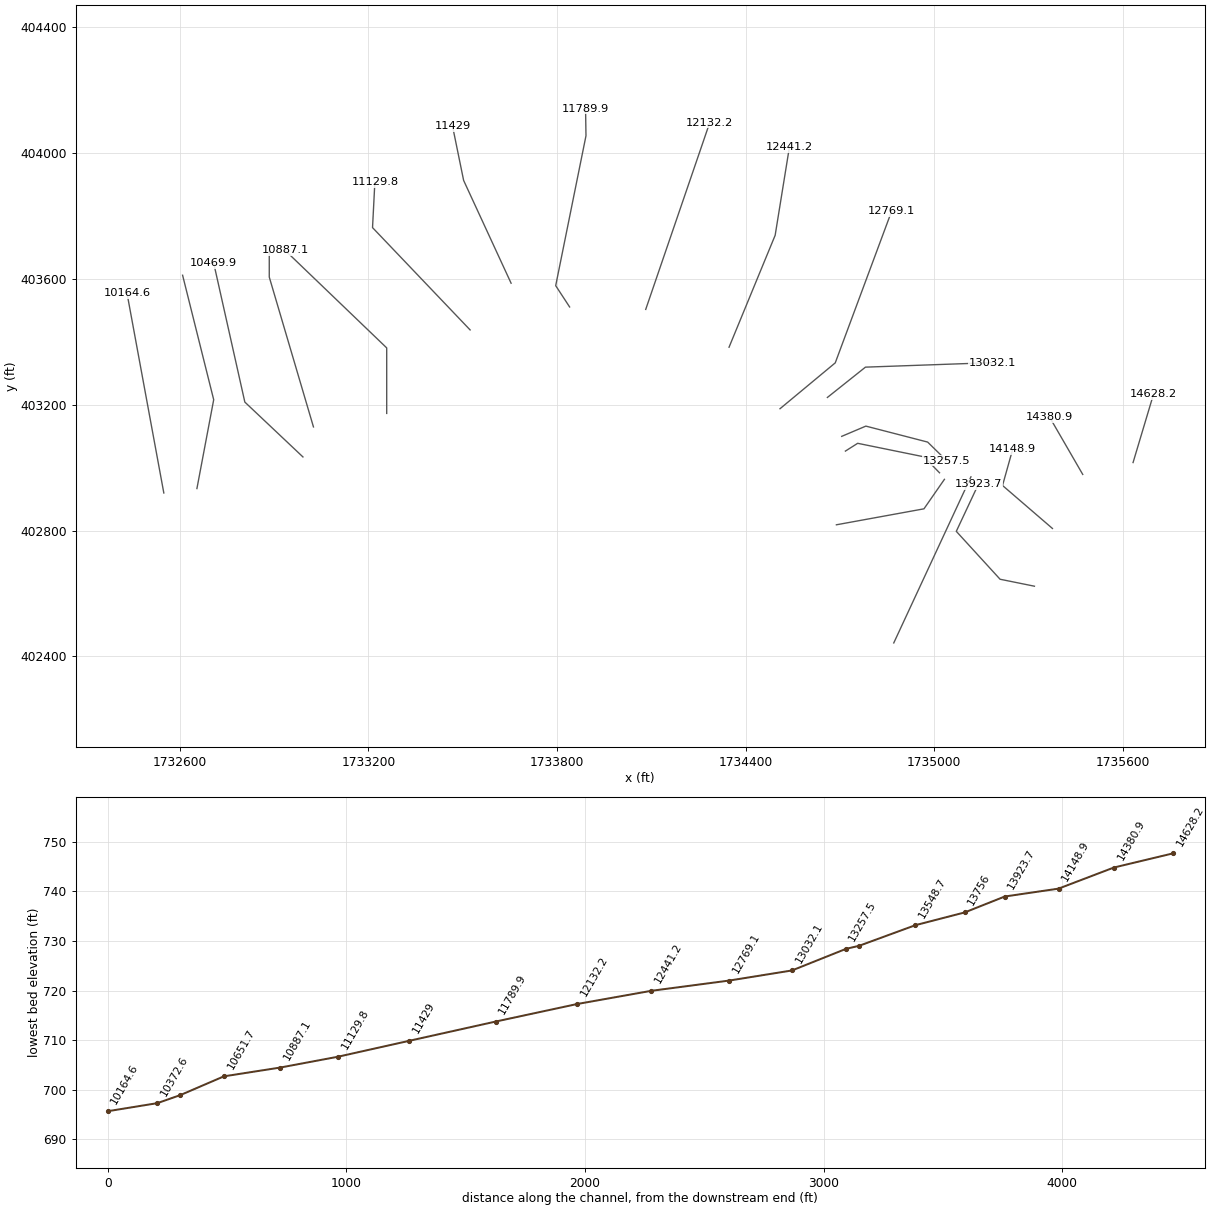
HEC-RAS study ROCKCK.prj: ROCKCK

--- ROCKCK.g01 (geometry) --- (continued)

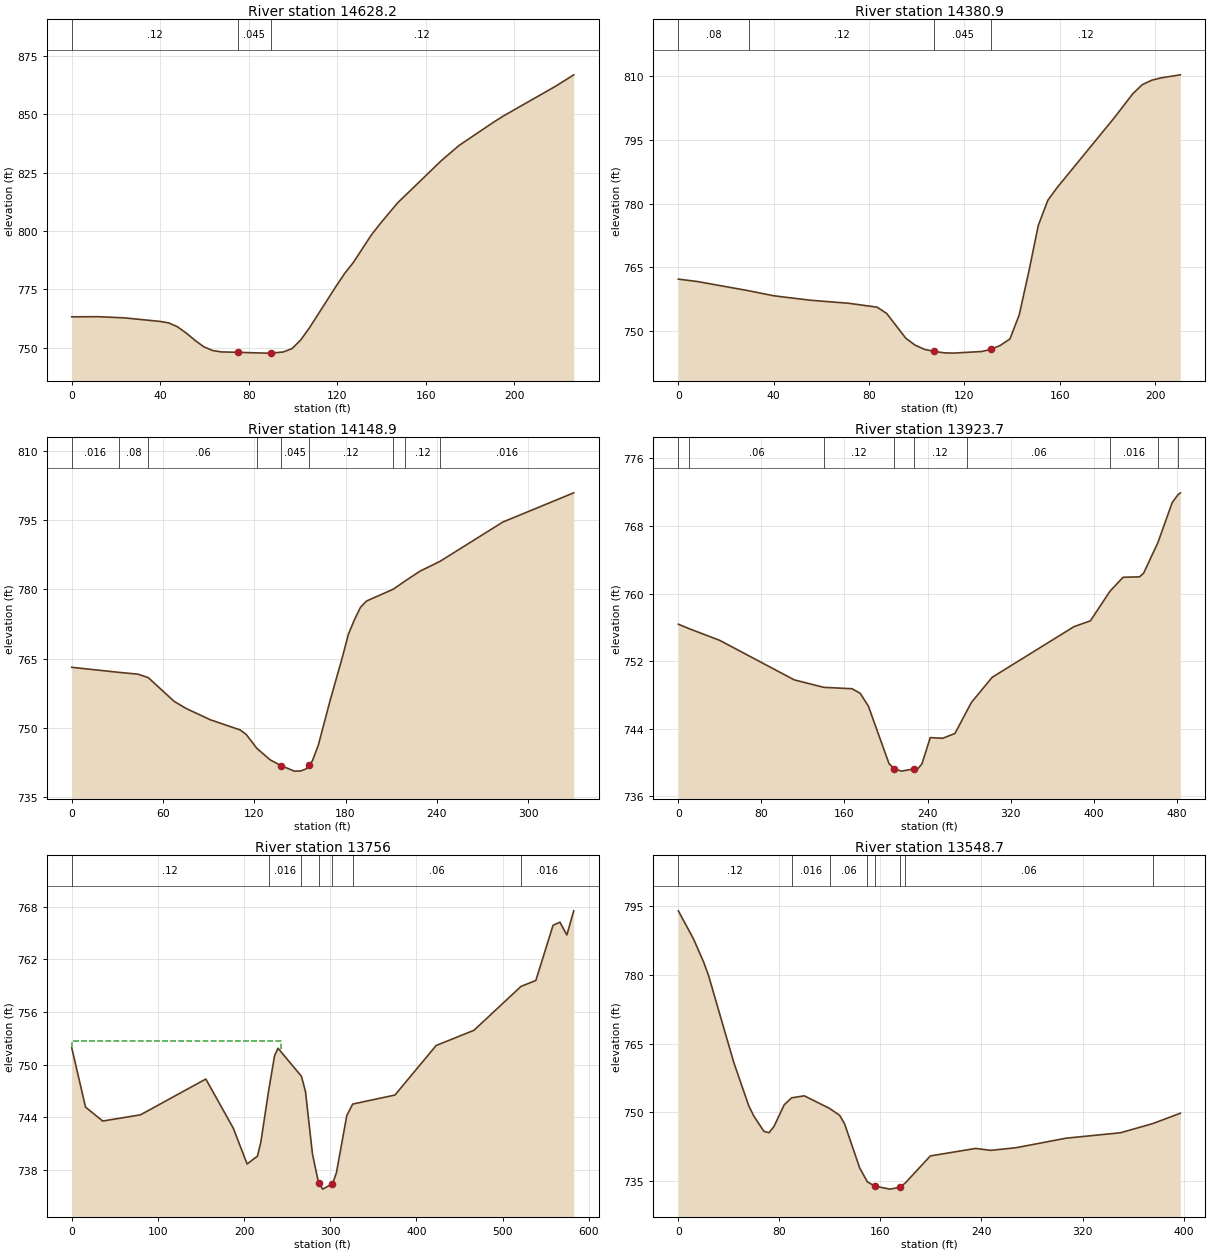
Type RM Length L Ch R = 1 ,14628.2 ,216.6,247.3,277.9
XS GIS Cut Line= 2
       1735633.2      403016.492     1735698.304       403233.94
#Sta/Elev= 30
       0  763.22      12  763.28    23.9  762.77    39.8  761.26    43.8  760.63
    47.8  758.96    51.8  756.25    55.8   753.1    59.7  750.39    63.7  748.78
    67.7  748.19      75  748.02    87.6  747.67      90  747.71    95.6  748.14
    99.6   749.6   103.5  753.26   107.5  758.53   119.5  776.28   123.4   781.8
   127.4  786.59   135.4  798.18   139.4  803.04   147.3  811.99   167.2   830.2
   175.2  836.68   191.2  846.88   195.1   849.2     219  862.12     227  866.89
#Mann= 3 ,-1 , 0
       0     .12       0      75    .045       0      90     .12       0
Bank Sta=75,90
XS Rating Curve= 0 ,0
Exp/Cntr=0.3,0.1

Type RM Length L Ch R = 1 ,14380.9 ,218.8,232,244.2
XS GIS Cut Line= 2
     1735473.044      402978.731     1735367.575      403161.023
#Sta/Elev= 30
       0  762.25       8  761.68    29.6 759.502    39.7  758.36    43.7  758.07
    55.6  757.27    71.5  756.56    83.4  755.64    87.4  754.17    95.4  748.35
    99.3   746.7   103.3   745.7   107.3  745.24   111.3   744.9   115.2  744.82
   127.2   745.2   131.1   745.7   135.1  746.65   139.1  748.15     143  753.79
     147  763.91     151  774.86     155   780.8     159  783.86   182.8  800.18
   190.7  805.93   194.7  808.06   198.7  809.11   202.7  809.66   210.6  810.36
#Mann= 4 ,-1 , 0
       0     .08       0    29.6     .12       0   107.3    .045       0
   131.1     .12       0
Bank Sta=107.3,131.1
XS Rating Curve= 0 ,0
Exp/Cntr=0.3,0.1

Type RM Length L Ch R = 1 ,14148.9 ,230.2,225.2,218.8
XS GIS Cut Line= 3
      1735376.69      402806.856     1735217.836      402943.575
     1735250.388       403059.46
#Sta/Elev= 30
       0  763.09    31.1761.9951    43.5   761.6   50.31760.8544    67.2  755.73
    75.1  754.17      91  751.72   110.7   749.5   114.7  748.52  121.66745.5137
   130.5  742.99   137.6  741.75   146.3  740.56   150.3  740.58   154.2  741.06
  155.91741.8038   158.2   742.8   162.1  746.21     170  756.08     178   765.4
   181.9  770.31   185.9  773.46   189.8  776.11   193.8  777.48  211.37780.0449
  219.14781.8221     229  783.97  242.04786.0811   283.4  794.62     330  800.96
#Mann= 9 ,-1 , 0
       0    .016       0    31.1     .08       0   50.31     .06       0
  121.66     .12       0   137.6    .045       0  155.91     .12       0
  211.37    .016       0  219.14     .12       0  242.04    .016       0
Bank Sta=137.6,155.91
XS Rating Curve= 0 ,0
Exp/Cntr=0.3,0.1

Type RM Length L Ch R = 1 ,13923.7 ,212.6,167.7,122.7
XS GIS Cut Line= 4
     1735319.398      402623.262     1735210.037       402645.41
       1735070.7      402797.742     1735141.013      402947.481
#Sta/Elev= 30
       0  756.37   10.59755.8329    39.8  754.46   111.6  749.78  139.97748.8954
   167.2  748.73   175.1  748.19     183  746.67   202.9  739.86   207.8  739.26
   214.8  738.97   226.7  739.23   230.7  739.26   234.6  739.84   242.6  742.94
   254.5  742.86   266.4  743.43  277.82746.0894   282.3  747.12   302.2  750.08
     381  756.08   396.8  756.77  415.77760.2922   428.3  761.93   444.1  761.98
     448   762.4  461.81766.0333   475.6  770.78  481.03 771.687   483.4  771.93
#Mann= 9 ,-1 , 0
       0     .08       0   10.59     .06       0  139.97     .12       0
   207.8    .045       0   226.7     .12       0  277.82     .06       0
  415.77    .016       0  461.81     .06       0  481.03    .016       0
Bank Sta=207.8,226.7
XS Rating Curve= 0 ,0
Exp/Cntr=0.3,0.1

Type RM Length L Ch R = 1 ,13756   ,244.1,207.2,170.3
XS GIS Cut Line= 2
     1734871.733      402442.881     1735117.333      402971.123
#Sta/Elev= 30
       0   751.9      16  745.13    35.9  743.54    79.8  744.25   155.6  748.34
   187.5  742.72   203.5  738.63   215.5  739.53   219.4   741.1  228.34 746.908
   235.4  751.02   239.4  751.86   266.6748.6533   271.3  746.89   279.3  739.81
  286.47 736.456   291.3  735.76   302.6  736.38   307.2  737.64   319.2  744.16
  326.06745.4803   375.1  746.51   422.9  752.17   466.8  753.91  521.48758.9301
   538.6   759.6   558.6  765.91   566.6  766.26   574.6   764.8   582.6  767.56
#Mann= 7 ,-1 , 0
       0     .12       0  228.34    .016       0   266.6     .12       0
  286.47    .045       0   302.6     .12       0  326.06     .06       0
  521.48    .016       0
#XS Ineff= 2 , 0
          242.62  752.63
Permanent Ineff=
       F       F
Bank Sta=286.47,302.6
XS Rating Curve= 0 ,0
Exp/Cntr=0.3,0.1

Type RM Length L Ch R = 1 ,13548.7 ,248.4,234.4,220.4
XS GIS Cut Line= 3
      1734689.19      402818.575     1734967.836      402869.356
      1735032.94      402963.106
#Sta/Elev= 30
       0  794.03      12  787.88      20  782.85    23.9  779.89    43.9  760.88
    55.8  751.36    59.8  749.14    67.8   745.8    71.8  745.52    75.8  746.92
    83.8  751.62   89.65753.1336    99.7  753.58  119.68750.8331   127.7  749.32
   131.6  747.47   143.6  737.79  149.69734.7487   155.9  733.81   167.6  733.18
   175.5  733.59  179.72734.5365   199.5  740.44   235.4  742.08   247.3  741.66
   267.3  742.23   306.8  744.31   350.1  745.51  375.68 747.515   397.4  749.77
#Mann= 8 ,-1 , 0
       0     .12       0   89.65    .016       0  119.68     .06       0
  149.69     .12       0   155.9    .045       0   175.5     .12       0
  179.72     .06       0  375.68    .016       0
Bank Sta=155.9,175.5
XS Rating Curve= 0 ,0
Exp/Cntr=0.3,0.1

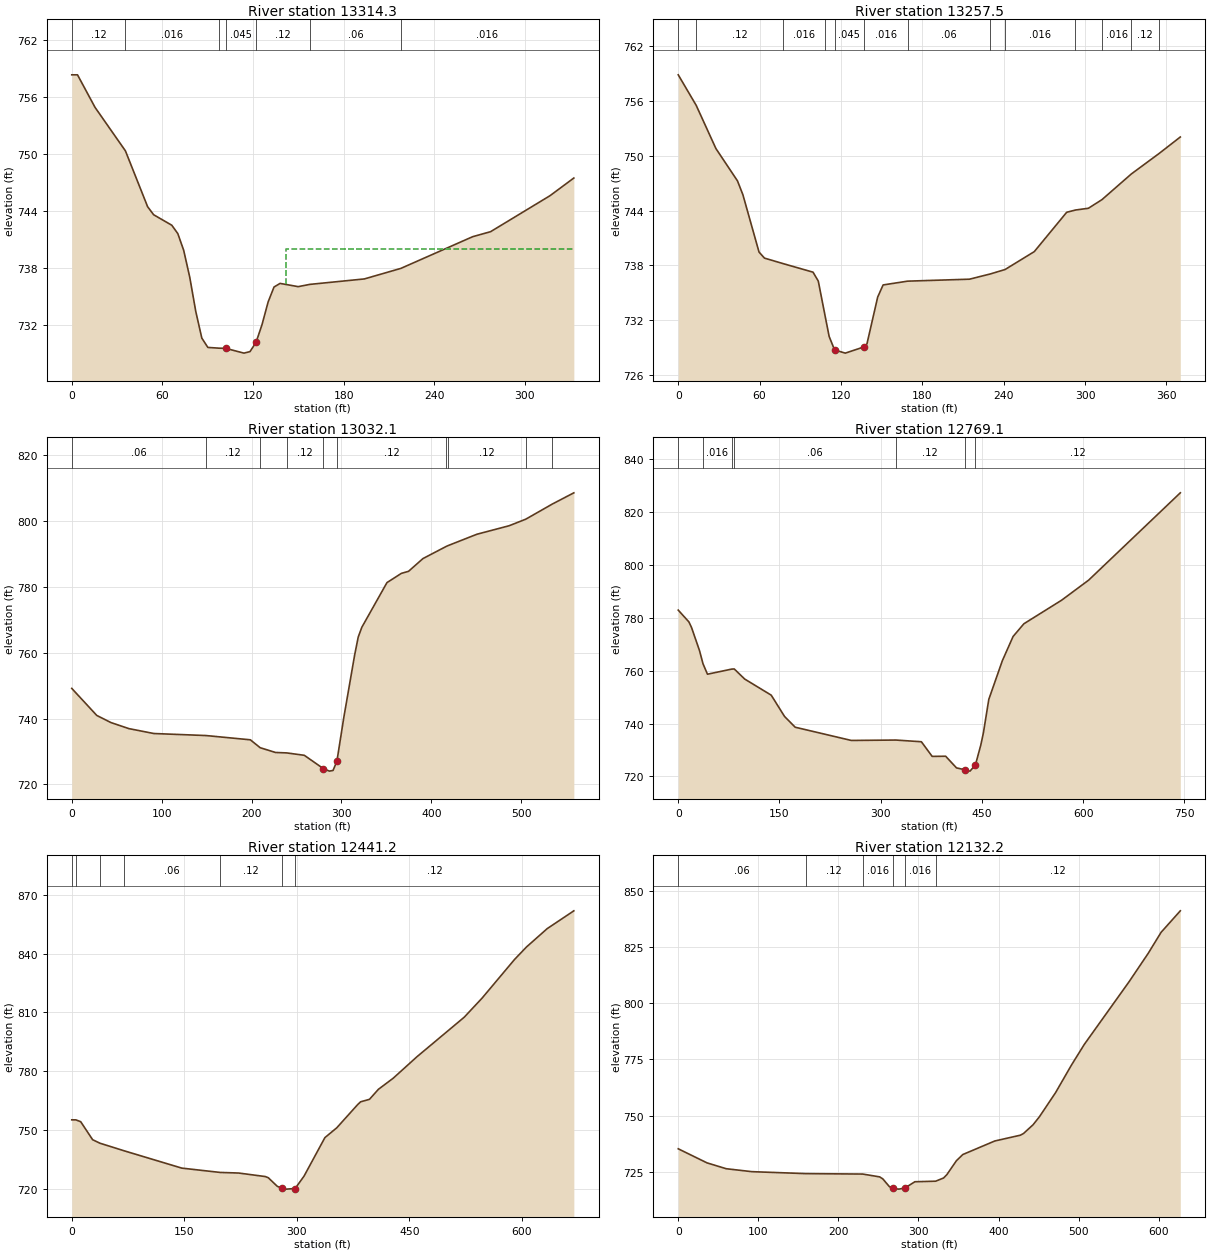
Type RM Length L Ch R = 1 ,13314.3 ,58.6,56.8,54.9
XS GIS Cut Line= 4
     1734717.836       403052.95     1734756.898       403077.69
     1734967.836      403034.721     1735017.315       402983.94
#Sta/Elev= 30
       0   758.3     3.8   758.3    15.4  754.88   35.53750.3035    50.2  744.44
    54.2  743.59    66.2  742.49    70.2  741.61    74.1  739.85    78.1  737.03
    82.1  733.42    86.1  730.62    90.1  729.64   97.29729.5627     102  729.54
     114  729.04     118   729.2     122  730.17     126  732.06     130  734.42
   133.9  735.99   137.9  736.37   149.9  736.03  157.58736.2664   193.7  736.84
  217.86737.9478   265.4  741.28   277.3  741.81   316.6  745.59   332.4  747.45
#Mann= 7 ,-1 , 0
       0     .12       0   35.53    .016       0   97.29     .12       0
     102    .045       0     122     .12       0  157.58     .06       0
  217.86    .016       0
#XS Ineff= 2 , 0
       0                   141.9       0     740
Permanent Ineff=
       F       F
Bank Sta=102,122
XS Rating Curve= 0 ,0
Exp/Cntr=0.3,0.1

Type RM Length L Ch R = 1 ,13257.5 ,214.5,225.4,236.1
XS GIS Cut Line= 4
     1734706.117      403099.825      1734782.94      403132.377
     1734979.554      403081.596      1735039.45      403023.002
#Sta/Elev= 30
       0  758.88   13.26 755.532    27.8   750.8    43.7  747.26    47.7  745.74
    59.6  739.46    63.6   738.8   77.41738.1945    99.4  737.26   103.3  736.28
  108.21732.5529   111.3  730.22   115.3  728.74   123.2  728.39   137.2  729.08
   139.2  729.41   147.1  734.53   151.1  735.86  169.22736.2756   214.8  736.49
  230.23737.0658  241.03737.5474   262.6  739.51   286.5  743.82  292.92744.0663
   302.5  744.26  312.48745.2016  334.23748.0247  354.71750.2681   370.3  752.07
#Mann= 13 ,-1 , 0
       0     .06       0   13.26     .12       0   77.41    .016       0
  108.21     .12       0   115.3    .045       0   137.2    .016       0
  169.22     .06       0  230.23     .12       0  241.03    .016       0
  292.92     .12       0  312.48    .016       0  334.23     .12       0
  354.71    .016       0
Bank Sta=115.3,137.2
XS Rating Curve= 0 ,0
Exp/Cntr=0.3,0.1

Type RM Length L Ch R = 1 ,13032.1 ,216.6,263,306.8
XS GIS Cut Line= 3
     1734660.544      403223.523     1734781.638      403319.877
     1735185.283        403334.2
#Sta/Elev= 30
       0  749.15    27.8  740.95    43.6  738.78    63.5  736.95    91.3  735.46
  149.33734.8437   198.7  733.55  209.61731.1535   226.7  729.71  239.17729.5753
   258.7  728.85     280   724.8   286.7  724.05   290.7  724.26     295  727.07
   302.7  740.37   314.7  759.24   318.7  764.72   322.7  767.68   350.7  781.25
   366.7  784.04   374.7  784.67   390.7  788.53  416.49792.1992  419.02 792.506
   450.7  795.91   486.7   798.5  505.15800.4885  534.71805.0817   558.6  808.48
#Mann= 10 ,-1 , 0
       0     .06       0  149.33     .12       0  209.61    .016       0
  239.17     .12       0     280    .045       0     295     .12       0
  416.49     .06       0  419.02     .12       0  505.15     .06       0
  534.71     .12       0
Bank Sta=280,295
XS Rating Curve= 0 ,0
Exp/Cntr=0.3,0.1

Type RM Length L Ch R = 1 ,12769.1 ,331.5,327.8,325.8
XS GIS Cut Line= 3
     1734509.754      403187.673     1734685.535      403333.506
     1734865.223      403816.579
#Sta/Elev= 30
       0   782.9    15.8  778.44    19.7  776.34    31.5   767.6   36.71 762.612
    43.3  758.66   79.12760.5874   82.97760.6443    98.4  756.84   137.8  750.73
   157.5  742.68   173.3  738.61   256.4  733.61  322.46733.7606   360.2  733.12
   376.2  727.58   396.2  727.64   412.2  723.24   424.2  722.54   432.2  722.01
   440.2   724.3   448.2  731.83   452.1   736.5   460.1  749.15   480.1  763.73
   496.1  772.94   512.1  777.74     568  786.65     608  794.23   743.8  827.25
#Mann= 7 ,-1 , 0
       0     .12       0   36.71    .016       0   79.12     .12       0
   82.97     .06       0  322.46     .12       0   424.2    .045       0
   440.2     .12       0
Bank Sta=424.2,440.2
XS Rating Curve= 0 ,0
Exp/Cntr=0.3,0.1

Type RM Length L Ch R = 1 ,12441.2 ,306.6,309.1,311.2
XS GIS Cut Line= 3
     1734347.556      403383.223     1734494.304      403739.147
     1734539.702      404019.704
#Sta/Elev= 30
       0  755.26    5.52755.2387    11.9  754.31    27.8  745.13   37.47743.3541
   69.42739.5135   146.8  730.63  197.86728.4349   222.3  728.14     258  726.34
     262  725.72   273.9  721.38   280.4  720.29   285.8  719.93   297.7  720.24
   309.6  726.56   337.4  746.19   353.2  751.19     381     763     385  764.45
   396.8  765.71   408.7  770.81   428.4  776.46     460  787.39   523.1  807.58
   546.8  817.26   590.2  837.03     606  843.35   633.7  852.74   669.2  861.81
#Mann= 7 ,-1 , 0
       0    .016       0    5.52     .06       0   37.47    .016       0
   69.42     .06       0  197.86     .12       0   280.4    .045       0
   297.7     .12       0
Bank Sta=280.4,297.7
XS Rating Curve= 0 ,0
Exp/Cntr=0.3,0.1

Type RM Length L Ch R = 1 ,12132.2 ,336.5,342.3,346.7
XS GIS Cut Line= 2
     1734082.419      403503.471     1734285.796      404096.527
#Sta/Elev= 30
       0  735.21    35.9  728.96    59.9  726.35    91.8  725.05  159.29  724.17
  230.41723.9792   251.6  722.72   255.6  721.79   263.6  718.43     268  717.63
   275.5  717.28     283  717.76   295.5  720.56  321.46720.8025   331.4  722.24
   335.4   723.7   347.4  729.91   355.4  732.66   395.3  738.68   427.3  741.26
   431.3  742.04   443.3  745.96   451.2  749.53   471.2  760.16   491.2  772.51
   507.2  781.67   563.1  809.52     587  822.15     603  831.44     627     841
#Mann= 6 ,-1 , 0
       0     .06       0  159.29     .12       0  230.41    .016       0
     268    .045       0     283    .016       0  321.46     .12       0
Bank Sta=268,283
XS Rating Curve= 0 ,0
Exp/Cntr=0.3,0.1

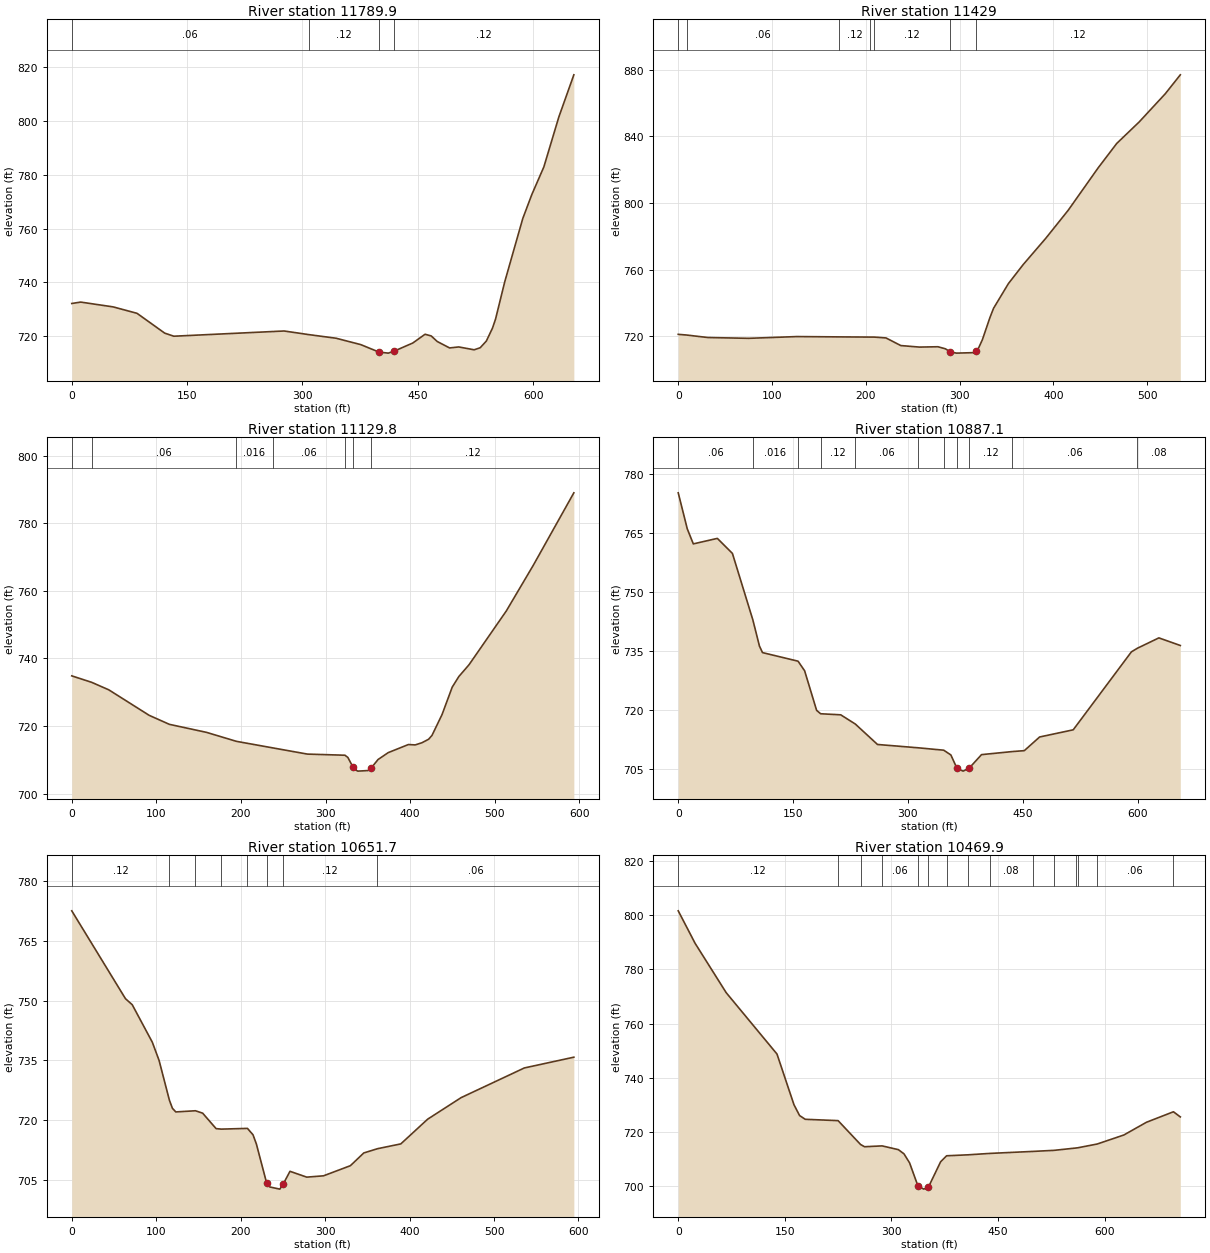
Type RM Length L Ch R = 1 ,11789.9 ,337.4,360.9,382.2
XS GIS Cut Line= 4
     1733840.231      403511.283      1733795.96      403578.992
     1733892.315      404055.554     1733891.013      404141.492
#Sta/Elev= 30
       0  732.19    11.6  732.71    53.9  730.92    84.9  728.53   120.8  721.18
   132.7  720.02   276.2  721.96  308.25720.6166   343.9  719.26   375.8   716.9
   399.7  714.11   411.7  713.73   419.6  714.51   443.6   717.5   459.5  720.75
   467.5  720.12   475.4  718.04   491.4  715.66   503.3  716.03   523.3  714.97
   531.2  715.73   539.2  718.22   547.2  723.04   551.2  726.42   563.1  740.23
   586.6   763.8   598.4  772.74     614  782.97   633.5  801.55     653  817.22
#Mann= 4 ,-1 , 0
       0     .06       0  308.25     .12       0   399.7    .045       0
   419.6     .12       0
Bank Sta=399.7,419.6
XS Rating Curve= 0 ,0
Exp/Cntr=0.3,0.1

Type RM Length L Ch R = 1 ,11429   ,286.3,299.1,313.2
XS GIS Cut Line= 3
     1733654.034      403586.804     1733502.992      403913.627
     1733467.835      404085.502
#Sta/Elev= 30
       0  721.15    9.12720.7115    31.6  719.23    75.2  718.75   126.6   719.8
  171.81719.6114  204.35 719.493  208.76   719.5   221.6  718.98   237.4   714.4
   257.2  713.49     277  713.69   284.9  712.46   290.3  710.64   296.7  709.86
   316.5  710.17  317.87711.1804   320.5  713.12   324.4  717.92   332.3  730.99
   336.3  736.77   352.1  751.57     368  763.09   391.9  778.75   415.9  795.64
   447.8  821.07   467.7  835.79   491.6  848.68   519.5  865.65   535.5     877
#Mann= 7 ,-1 , 0
       0    .016       0    9.12     .06       0  171.81     .12       0
  204.35     .06       0  208.76     .12       0   290.3    .045       0
  317.87     .12       0
Bank Sta=290.3,317.87
XS Rating Curve= 0 ,0
Exp/Cntr=0.3,0.1

Type RM Length L Ch R = 1 ,11129.8 ,241,242.7,244.4
XS GIS Cut Line= 3
     1733523.608       403438.24     1733213.105      403763.604
      1733220.51      403907.262
#Sta/Elev= 30
       0  734.84   23.51732.9285    43.8   730.7    91.5  723.16   115.4  720.49
   159.2  718.12  194.63715.4596   237.4 713.529   278.6  711.68  322.96 711.345
   326.4   710.7   332.4  707.87   334.3  707.11   338.3  706.64   350.2  706.81
   354.2  707.64   362.2  710.09   374.1  712.11     398  714.51     406   714.4
   413.9  715.03   421.9  716.08   425.9  717.22   437.8   723.4   449.8   731.5
   457.7  734.66   469.7  738.14   513.7  754.03   545.6  767.55   593.6  789.02
#Mann= 7 ,-1 , 0
       0     .12       0   23.51     .06       0  194.63    .016       0
   237.4     .06       0  322.96     .12       0   332.4    .045       0
   354.2     .12       0
Bank Sta=332.4,354.2
XS Rating Curve= 0 ,0
Exp/Cntr=0.3,0.1

Type RM Length L Ch R = 1 ,10887.1 ,254.9,235.5,215.9
XS GIS Cut Line= 3
       1733258.2      403172.742       1733258.2      403381.075
     1732935.283      403690.971
#Sta/Elev= 30
       0  775.13    11.8  765.99    19.7  762.16    51.1  763.56    70.8  759.74
   97.46742.8722   106.1  736.21   110.1  734.55  156.53 732.373   165.1  729.94
   180.8  719.87  186.07719.0214   212.3  718.75  231.39716.4011   260.3  711.22
  313.26710.3774   346.8709.7685   356.2  708.55   364.2  705.13   372.2  704.45
   380.2  705.23   396.2  708.64  436.07709.4109   452.1  709.65   472.1  713.12
     516  714.94     592  734.74  599.81735.6572   627.9  738.29   655.9  736.36
#Mann= 11 ,-1 , 0
       0     .06       0   97.46    .016       0  156.53     .06       0
  186.07     .12       0  231.39     .06       0  313.26    .016       0
   346.8     .12       0   364.2    .045       0   380.2     .12       0
  436.07     .06       0  599.81     .08       0
Bank Sta=364.2,380.2
XS Rating Curve= 0 ,0
Exp/Cntr=0.3,0.1

Type RM Length L Ch R = 1 ,10651.7 ,184.4,181.8,179.2
XS GIS Cut Line= 3
     1733025.127      403129.773     1732884.502      403606.335
     1732884.502      403703.992
#Sta/Elev= 30
       0  772.52    63.6  750.47    71.6  748.96    95.4  739.54   103.4  734.97
  115.63 724.983   119.2  722.96   123.2  722.05  146.42 722.347     155  721.74
   170.9  717.86  177.22717.7384  208.01717.9224   214.6  716.32   218.6     714
   230.6  704.33   234.5  703.22   246.4  702.68   250.4  703.97   258.4  707.15
   278.2  705.69   298.1  706.02   329.9  708.56   345.8  711.76  361.98712.8219
   389.6  714.03   421.4  720.23   461.1  725.65   535.9  733.09   594.5  735.79
#Mann= 8 ,-1 , 0
       0     .12       0  115.63    .016       0  146.42     .06       0
  177.22    .016       0  208.01     .12       0   230.6    .045       0
   250.4     .12       0  361.98     .06       0
Bank Sta=230.6,250.4
XS Rating Curve= 0 ,0
Exp/Cntr=0.3,0.1

Type RM Length L Ch R = 1 ,10469.9 ,96.1,97.2,98.1
XS GIS Cut Line= 3
     1732991.675      403034.305      1732806.78      403208.784
     1732707.821       403650.19
#Sta/Elev= 30
       0  801.66    23.8  789.64    67.5  771.44     139  748.78   162.9  730.06
   170.8  726.07   178.8  724.69  224.96724.1996  256.64 715.379   262.2  714.56
  286.91 714.874   309.8  713.49   317.7  711.94   325.6   708.6   337.2   700.2
   345.5  698.91   352.2   699.7   369.3  709.02  377.71 711.223  407.98711.5765
  438.25712.0914  498.79712.8292  529.06713.2286  559.32714.0792  561.94714.1559
  589.59715.5606   627.2   718.9     659   723.6  696.94727.4715   706.6  725.57
#Mann= 15 ,-1 , 0
       0     .12       0  224.96     .06       0  256.64    .016       0
  286.91     .06       0   337.2    .045       0   352.2     .06       0
  377.71     .08       0  407.98    .016       0  438.25     .08       0
  498.79     .06       0  529.06     .12       0  559.32     .06       0
  561.94     .12       0  589.59     .06       0  696.94     .12       0
Bank Sta=337.2,352.2
XS Rating Curve= 0 ,0
Exp/Cntr=0.3,0.1

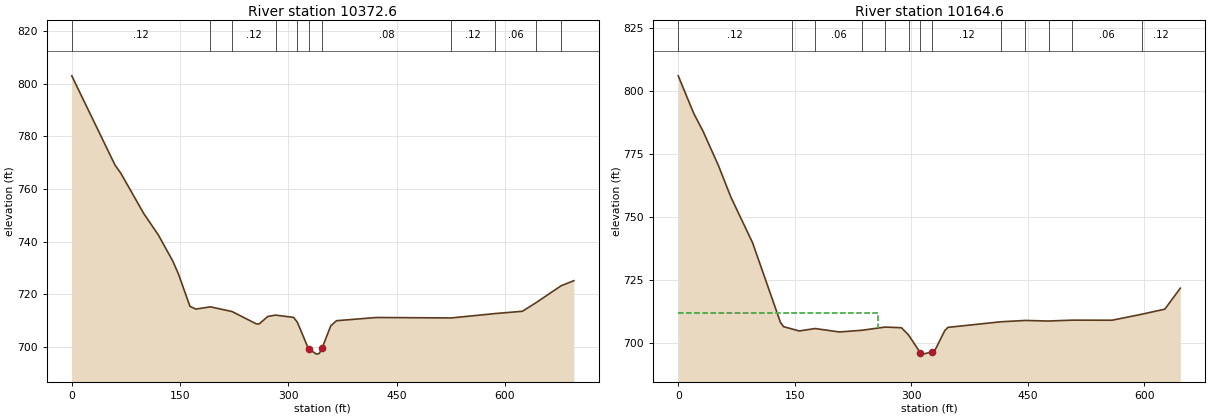
Type RM Length L Ch R = 1 ,10372.6 ,210.4,208.1,205.7
XS GIS Cut Line= 3
     1732654.285      402933.766     1732707.671      403216.318
     1732608.713      403612.151
#Sta/Elev= 30
       0  803.01    59.9  769.11    67.9  766.03    99.8  750.66   119.8  742.62
   139.8  732.72   147.8  727.73   163.7  715.46   171.7  714.38  192.11715.2357
  222.17 713.445   255.6  708.77   259.6  708.74   271.6  711.58  282.28712.0967
   307.4  711.23  312.66709.3292     328  699.26     339  697.27     343  697.51
     347   699.7   358.8  708.01   366.8  709.97   422.2  711.19  525.77711.0186
  586.66712.6803   624.3  713.55  643.57716.8835  677.99723.2494   695.6  725.17
#Mann= 11 ,-1 , 0
       0     .12       0  192.11     .06       0  222.17     .12       0
  282.28    .016       0  312.66     .12       0     328    .045       0
     347     .08       0  525.77     .12       0  586.66     .06       0
  643.57     .12       0  677.99     .06       0
Bank Sta=328,347
XS Rating Curve= 0 ,0
Exp/Cntr=0.3,0.1

Type RM Length L Ch R = 1 ,10164.6 ,305.4,298.3,291.3
XS GIS Cut Line= 2
     1732548.967      402919.721     1732431.779      403555.138
#Sta/Elev= 30
       0  806.03    19.9  791.16    31.9  784.07    51.8   770.4    67.8  757.89
    95.7   739.8   131.6   708.2   135.6  706.53  146.17705.6373   155.6  704.83
  176.21705.7882   207.4  704.43  236.27705.1052  266.31706.3721   287.2  706.11
  296.34703.2723   311.6  696.13   315.1  695.64   326.6  696.55     331  697.56
     343  704.97     347  706.25  415.31708.4749  446.51708.9962  476.54708.7673
  506.57709.1182   558.4  709.09  596.67711.4733   626.2  713.48   646.1   721.8
#Mann= 13 ,-1 , 0
       0     .12       0  146.17     .08       0  176.21     .06       0
  236.27     .08       0  266.31    .016       0  296.34     .12       0
   311.6    .045       0   326.6     .12       0  415.31    .016       0
  446.51     .06       0  476.54     .12       0  506.57     .06       0
  596.67     .12       0
#XS Ineff= 2 , 0
             257  711.79
Permanent Ineff=
       F       F
Bank Sta=311.6,326.6
XS Rating Curve= 0 ,0
Exp/Cntr=0.3,0.1