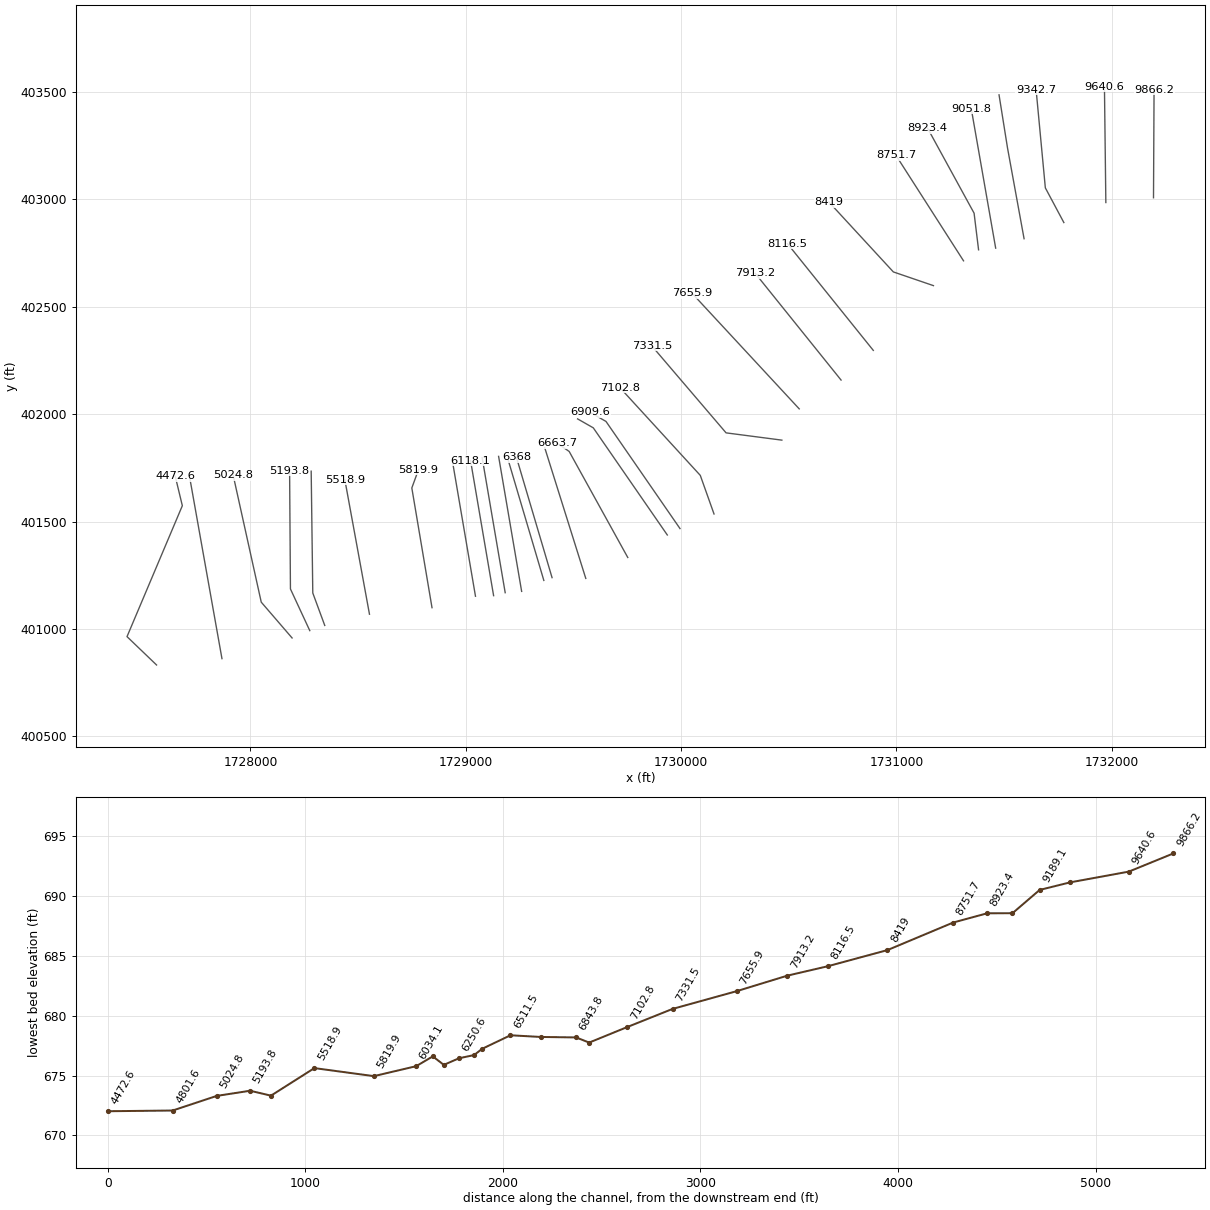
HEC-RAS study ROCKCK.prj: ROCKCK

--- ROCKCK.g01 (geometry) --- (continued)

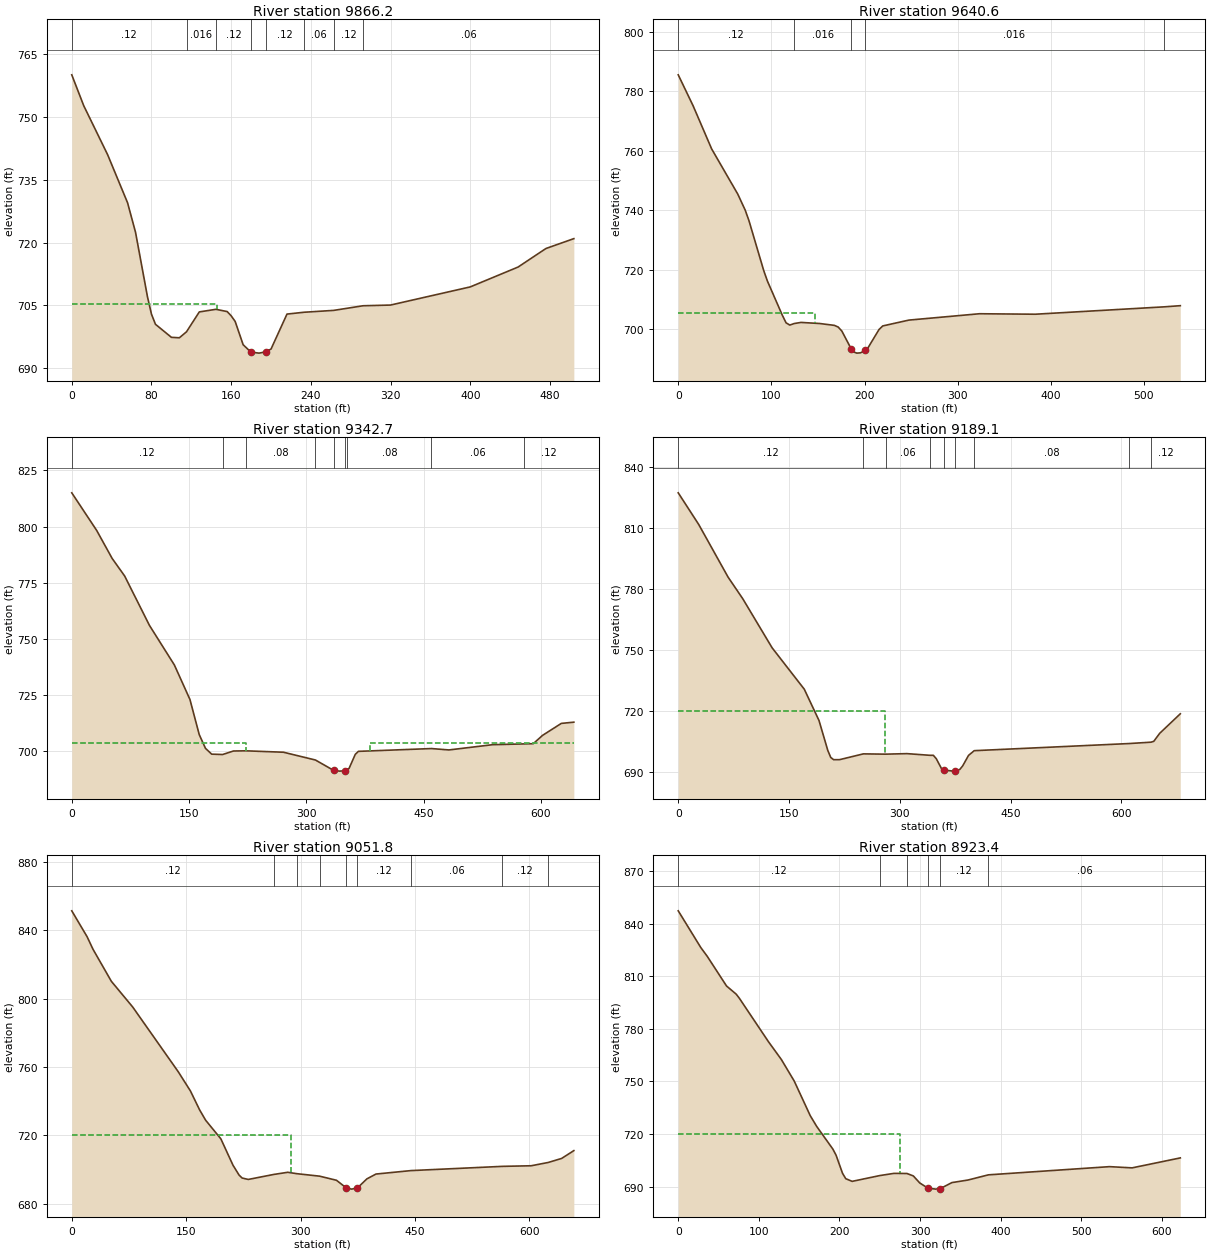
Type RM Length L Ch R = 1 ,9866.2  ,224.9,225.7,226.2
XS GIS Cut Line= 2
     1732194.398      403007.377     1732197.002      403511.283
#Sta/Elev= 30
       0  760.12      12  752.74      36  741.01      56  729.51      64  722.45
      76     707      80  702.86      84  700.44     100  697.32     108  697.21
  115.17698.6521     128   703.4  144.71704.0218     156  703.48     160  702.46
     164  701.12     172  695.55   179.8  693.78     188  693.54   194.8  693.85
     200  694.52     216  702.88  233.31703.3233  262.85703.7639  292.38704.8719
   319.9  705.04   399.9  709.38   447.9  714.13   475.9  718.57   503.9  720.93
#Mann= 8 ,-1 , 0
       0     .12       0  115.17    .016       0  144.71     .12       0
   179.8    .045       0   194.8     .12       0  233.31     .06       0
  262.85     .12       0  292.38     .06       0
#XS Ineff= 2 , 0
          145.57   705.2
Permanent Ineff=
       F       F
Bank Sta=179.8,194.8
XS Rating Curve= 0 ,0
Exp/Cntr=0.3,0.1

Type RM Length L Ch R = 1 ,9640.6  ,294.7,297.9,300.9
XS GIS Cut Line= 2
     1731973.044      402985.242     1731966.533      403524.304
#Sta/Elev= 30
       0  785.58      16  775.15    35.9  760.66    63.9   745.5    71.9   740.1
    75.9   736.6    91.8  719.77    95.8  716.22   111.8  704.74   115.8  702.21
   119.8  701.45  124.49701.9669   131.8  702.34   151.8  701.98   167.7  701.35
   171.7   700.8   175.7  699.43   185.8   693.4   187.7  692.52   191.7  692.02
   195.7  692.12   200.8  692.93   203.7  693.78   215.6  699.96   219.6  701.16
   247.6  703.12   323.5  705.26   383.4   705.1   521.3707.5705   539.1  707.97
#Mann= 5 ,-1 , 0
       0     .12       0  124.49    .016       0   185.8    .045       0
   200.8    .016       0   521.3     .08       0
#XS Ineff= 2 , 0
          147.11  705.41
Permanent Ineff=
       F       F
Bank Sta=185.8,200.8
XS Rating Curve= 0 ,0
Exp/Cntr=0.3,0.1

Type RM Length L Ch R = 1 ,9342.7  ,150.3,153.6,156.8
XS GIS Cut Line= 3
     1731777.983      402892.099     1731692.046      403053.558
     1731649.077      403510.589
#Sta/Elev= 30
       0  815.01    31.8   798.3    51.7  785.77    67.6     778    99.4  755.96
   131.2  738.38   151.1  723.03     163  707.38     171  701.25   178.9  698.68
  192.87698.5172   206.8  700.08  222.54700.1606   270.7  699.53  311.54696.0696
   334.7  691.48   342.6  691.12   349.7  691.34   352.3691.7922   354.6  692.35
   362.5  698.57   366.5  699.92  459.86701.1673   482.3  700.55   538.2  702.89
  578.53703.2365   590.1  703.33     602  707.04     626  712.37     642  712.92
#Mann= 9 ,-1 , 0
       0     .12       0  192.87    .016       0  222.54     .08       0
  311.54     .12       0   334.7    .045       0   349.7     .12       0
   352.3     .08       0  459.86     .06       0  578.53     .12       0
#XS Ineff= 2 , 0
       0  222.54  703.75   381.9       0  703.75
Permanent Ineff=
       F       F
Bank Sta=334.7,349.7
XS Rating Curve= 0 ,0
Exp/Cntr=0.3,0.1

Type RM Length L Ch R = 1 ,9189.1  ,138.5,137.3,136.6
XS GIS Cut Line= 3
     1731593.238      402816.857     1731516.415      403238.732
      1731476.95      403486.544
#Sta/Elev= 30
       0  827.48    27.8  811.87    67.5  785.98    87.4  775.33   127.1   751.2
   170.7   730.8   190.6  715.41   202.5  700.69   206.5  697.22   210.4  696.13
   218.4  696.13  250.68698.9818  280.71698.8438   309.7   699.1  340.75698.2775
   345.4  698.28   349.4   696.6   357.3  691.15   359.2     691   373.2  690.49
   374.2  690.55   381.2   691.3   385.1  693.04   393.1  698.25  400.79 700.558
  610.25  704.06  640.16704.7393   643.9  705.16   651.9   709.1   679.8  718.71
#Mann= 9 ,-1 , 0
       0     .12       0  250.68    .016       0  280.71     .06       0
  340.75     .12       0   359.2    .045       0   374.2     .06       0
  400.79     .08       0  610.25     .06       0  640.16     .12       0
#XS Ineff= 2 , 0
       0     280     720               0
Permanent Ineff=
       F       F
Bank Sta=359.2,374.2
XS Rating Curve= 0 ,0
Exp/Cntr=0.3,0.1

Type RM Length L Ch R = 1 ,9051.8  ,115.1,128.4,141.2
XS GIS Cut Line= 2
     1731461.325      402773.002     1731348.044       403421.44
#Sta/Elev= 30
       0   851.5      20  836.42    27.9  828.95    51.9  810.24    79.8  795.24
   139.6  757.29   155.6  746.02   167.6  734.98   175.5  728.91   195.5  717.98
   211.4  702.55   219.4  696.76   223.4  695.05   231.4  694.22   264.9  697.15
   283.2  698.41  294.88697.5984  324.87 696.145   347.1  693.73   359.6  689.37
     367  688.55   374.6  689.28     387  694.57   398.9  697.38   444.8   699.4
  564.73701.8821   602.4  702.23  624.69704.1577   642.3  706.52   658.3   711.1
#Mann= 9 ,-1 , 0
       0     .12       0   264.9    .016       0  294.88     .06       0
  324.87     .12       0   359.6    .045       0   374.6     .12       0
   444.8     .06       0  564.73     .12       0  624.69     .06       0
#XS Ineff= 2 , 0
       0   287.2     720               0
Permanent Ineff=
       F       F
Bank Sta=359.6,374.6
XS Rating Curve= 0 ,0
Exp/Cntr=0.3,0.1

Type RM Length L Ch R = 1 ,8923.4  ,169,171.7,174.3
XS GIS Cut Line= 3
     1731381.898       402765.19     1731361.065      402935.762
     1731144.919      403331.596
#Sta/Elev= 30
       0  847.37      28  826.41      36   821.4    59.9  804.48    71.9  799.81
    75.9  797.42   111.9  772.69   127.9  762.53   143.9  750.21   163.8  730.42
   171.8   724.3   191.8   711.4   195.8  707.91   203.8  697.58   207.8  694.51
   215.7  692.97  250.06696.2827   267.6  697.53  283.72697.4625   291.6  696.08
   299.6  692.06   309.7  689.09   319.5  688.54   324.7  688.76   339.5  692.27
   359.4  693.73  384.67696.6857     535  701.37     563  700.67   622.8  706.36
#Mann= 6 ,-1 , 0
       0     .12       0  250.06    .016       0  283.72     .12       0
   309.7    .045       0   324.7     .12       0  384.67     .06       0
#XS Ineff= 2 , 0
       0   275.6     720               0
Permanent Ineff=
       F       F
Bank Sta=309.7,324.7
XS Rating Curve= 0 ,0
Exp/Cntr=0.3,0.1

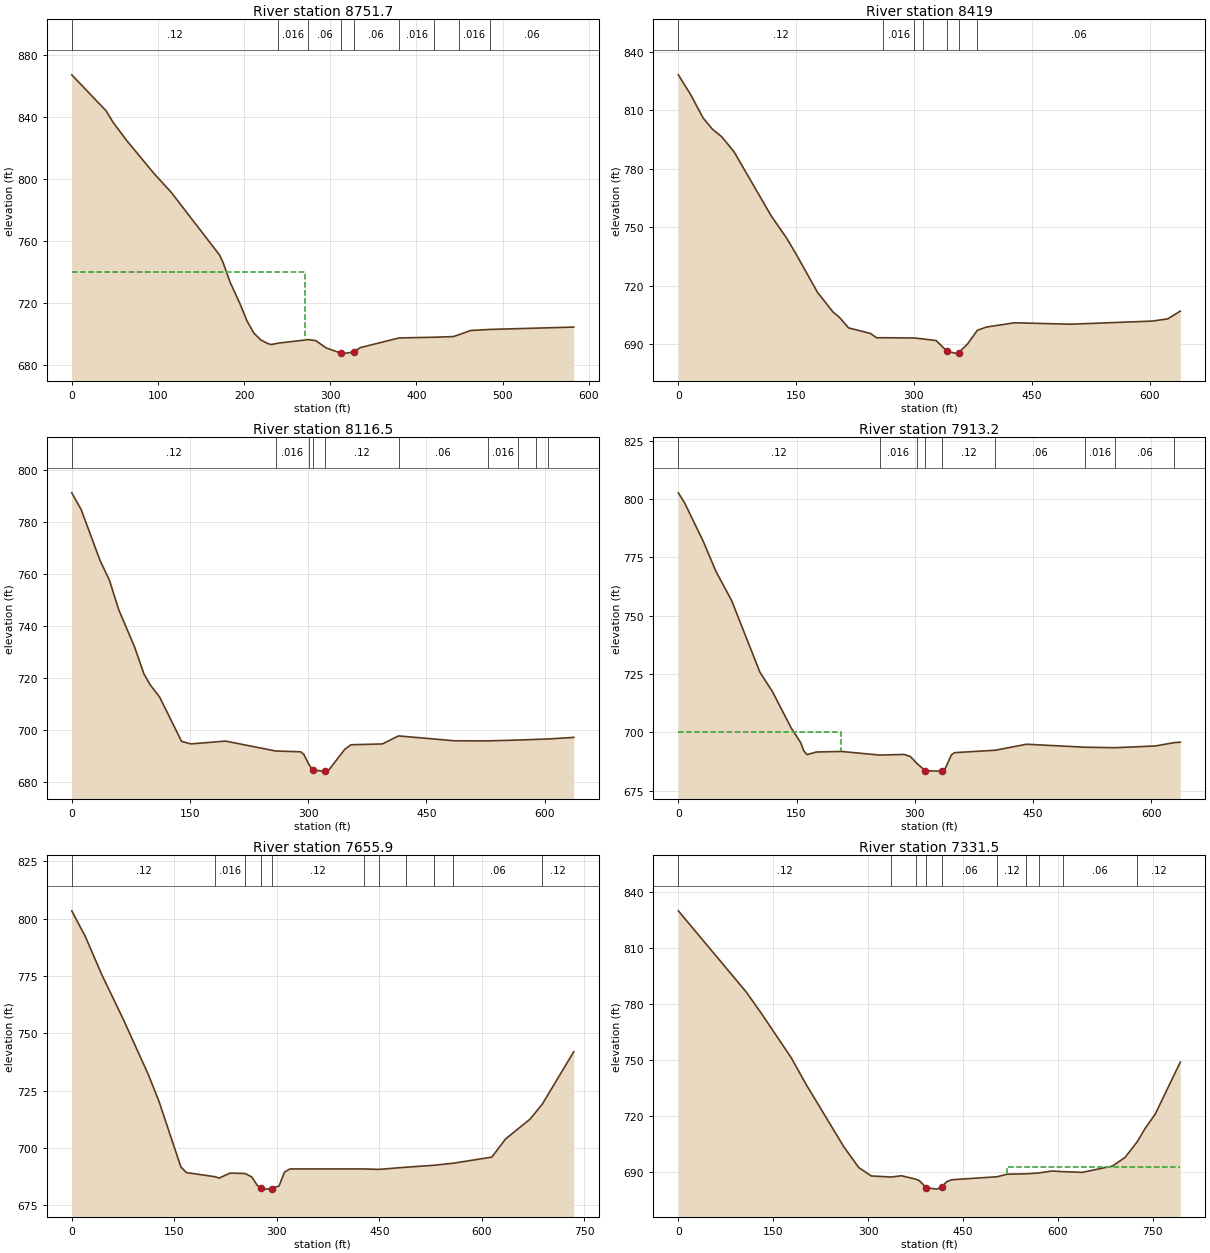
Type RM Length L Ch R = 1 ,8751.7  ,326.1,332.7,339.2
XS GIS Cut Line= 2
     1731311.988      402713.992     1730998.186      403204.877
#Sta/Elev= 30
       0  867.09    39.9  843.88    47.9  836.54    63.8  824.74    95.8  803.28
   115.7  791.21   171.6  750.93   175.6  746.16   183.6  733.68   195.5   719.3
   203.5  708.39   211.5   700.6   219.5  696.21   227.5  693.96   231.4  693.28
  239.54694.1854  274.59696.4801   283.3   695.8   295.3  691.12     312  687.83
   319.2  687.77     327  688.63   335.2  691.36  379.75 697.557  420.54698.0054
     443  698.45  449.86699.7348   462.9  702.34  484.92703.0377   582.6  704.55
#Mann= 9 ,-1 , 0
       0     .12       0  239.54    .016       0  274.59     .06       0
     312    .045       0     327     .06       0  379.75    .016       0
  420.54     .06       0  449.86    .016       0  484.92     .06       0
#XS Ineff= 2 , 0
       0  270.18     740               0
Permanent Ineff=
       F       F
Bank Sta=312,327
XS Rating Curve= 0 ,0
Exp/Cntr=0.3,0.1

Type RM Length L Ch R = 1 ,8419    ,304.9,302.5,299.7
XS GIS Cut Line= 3
     1731172.263      402598.523     1730986.065      402662.325
     1730686.585      402987.846
#Sta/Elev= 30
       0  828.29    15.8  818.06    31.5  806.18    43.3  800.42    55.1  796.57
    70.9  788.82   118.1  756.01   137.8  744.54   149.6  736.54   177.1  716.74
   196.8  706.63   204.8  703.96   216.8  698.42   244.6  695.58   252.6  693.32
  260.35693.3813  300.48 693.228  311.73692.7452   328.3  691.93   342.2  686.42
   352.2  685.47   357.2  685.79   368.2  690.14  380.75697.1625   392.1  698.84
     428  701.05   499.7  700.31   603.3  701.91   623.2  703.04   639.2  707.05
#Mann= 7 ,-1 , 0
       0     .12       0  260.35    .016       0  300.48     .06       0
  311.73     .12       0   342.2    .045       0   357.2     .12       0
  380.75     .06       0
Bank Sta=342.2,357.2
XS Rating Curve= 0 ,0
Exp/Cntr=0.3,0.1

Type RM Length L Ch R = 1 ,8116.5  ,203.4,203.4,203.4
XS GIS Cut Line= 3
      1730892.92      402297.085     1730693.564       402545.48
     1730494.209      402793.874
#Sta/Elev= 30
       0  791.19    11.9  784.77    35.8  765.24    47.8  757.56    59.7  746.15
    79.6  731.98    91.6  721.53    99.5  717.33   111.5  712.63   139.3  695.58
   151.3  694.59   195.1  695.68  258.61691.8738   290.6  691.55   294.6  690.49
  301.04686.6384   305.8  684.57   318.5  684.12   320.8  684.14   326.5  684.67
   346.4   692.5   354.3  694.26   394.1  694.58  414.66697.6697   485.7  695.79
  528.27  695.76  566.14696.0726  588.91696.3235  604.01696.4811     637   697.1
#Mann= 10 ,-1 , 0
       0     .12       0  258.61    .016       0  301.04     .12       0
   305.8    .045       0   320.8     .12       0  414.66     .06       0
  528.27    .016       0  566.14     .06       0  588.91     .08       0
  604.01     .06       0
Bank Sta=305.8,320.8
XS Rating Curve= 0 ,0
Exp/Cntr=0.3,0.1

Type RM Length L Ch R = 1 ,7913.2  ,254.6,257.3,259.8
XS GIS Cut Line= 3
      1730743.18      402159.065     1730543.825      402407.459
      1730344.47      402655.853
#Sta/Elev= 30
       0   802.7       8  798.37    31.8  781.75    47.8  768.96    67.7  756.43
   103.5  725.77   119.4  717.47   143.3  701.78   155.3  695.54   159.2  692.03
   163.2  690.43   175.2  691.54     207  691.78  255.32690.2287   286.6   690.5
   294.6  689.58   302.5686.7067   313.4  683.51   330.4  683.34  335.06683.4968
   338.4  684.24   346.4  690.25   350.4  691.26  402.28692.3027   441.9  694.87
  515.89693.5971  553.76693.3909   605.2  694.12  629.51695.5902     637  695.75
#Mann= 9 ,-1 , 0
       0     .12       0  255.32    .016       0   302.5     .12       0
   313.4    .045       0  335.06     .12       0  402.28     .06       0
  515.89    .016       0  553.76     .06       0  629.51     .08       0
#XS Ineff= 2 , 0
       0     207     700               0
Permanent Ineff=
       F       F
Bank Sta=313.4,335.06
XS Rating Curve= 0 ,0
Exp/Cntr=0.3,0.1

Type RM Length L Ch R = 1 ,7655.9  ,325.2,324.4,322.6
XS GIS Cut Line= 2
     1730548.817      402024.912     1730050.119      402563.974
#Sta/Elev= 30
       0  803.42      20  792.12    43.9  775.61    75.8  755.85   111.8  732.16
   127.7  720.25   159.6  691.77   167.6  689.27  210.07687.4294   215.5  686.85
   231.5  689.03  253.57688.8527   263.4  687.34   271.4   683.7   277.3  682.39
   283.4  682.04   292.3  682.26   303.3  683.43   311.3  689.47   319.3  690.85
  427.53 690.846  449.21690.6492  489.45691.6091  529.69692.4333  558.01693.3303
   614.6     696   634.6  703.92   670.5  712.56  688.48719.1356   734.4  741.96
#Mann= 11 ,-1 , 0
       0     .12       0  210.07    .016       0  253.57     .12       0
   277.3    .045       0   292.3     .12       0  427.53     .06       0
  449.21    .016       0  489.45     .06       0  529.69     .08       0
  558.01     .06       0  688.48     .12       0
Bank Sta=277.3,292.3
XS Rating Curve= 0 ,0
Exp/Cntr=0.3,0.1

Type RM Length L Ch R = 1 ,7331.5  ,227.3,228.7,230
XS GIS Cut Line= 3
     1730468.238      401879.356     1730209.123      401913.211
     1729864.071      402318.159
#Sta/Elev= 30
       0  829.79   106.9  786.43   130.7  775.06   178.2  751.12   201.9  736.73
   261.3  703.39   285.1  692.12     305  687.62  336.85 687.055   352.6  687.74
  375.65685.8523   380.4  685.22     392  681.35   408.2  680.56   416.2  681.58
   424.1  684.54     432  685.59  503.99687.2027   519.4  688.55  549.53688.7633
  569.67689.2301   590.8  690.27  608.48689.9266   638.5  689.55   686.1  692.93
     706  697.57  724.89 705.805   737.8  713.17   753.6  720.75   793.3   748.7
#Mann= 10 ,-1 , 0
       0     .12       0  336.85    .016       0  375.65     .12       0
     392    .045       0   416.2     .06       0  503.99     .12       0
  549.53     .06       0  569.67     .12       0  608.48     .06       0
  724.89     .12       0
#XS Ineff= 2 , 0
                          518.61          692.24
Permanent Ineff=
       F       F
Bank Sta=392,416.2
XS Rating Curve= 0 ,0
Exp/Cntr=0.3,0.1

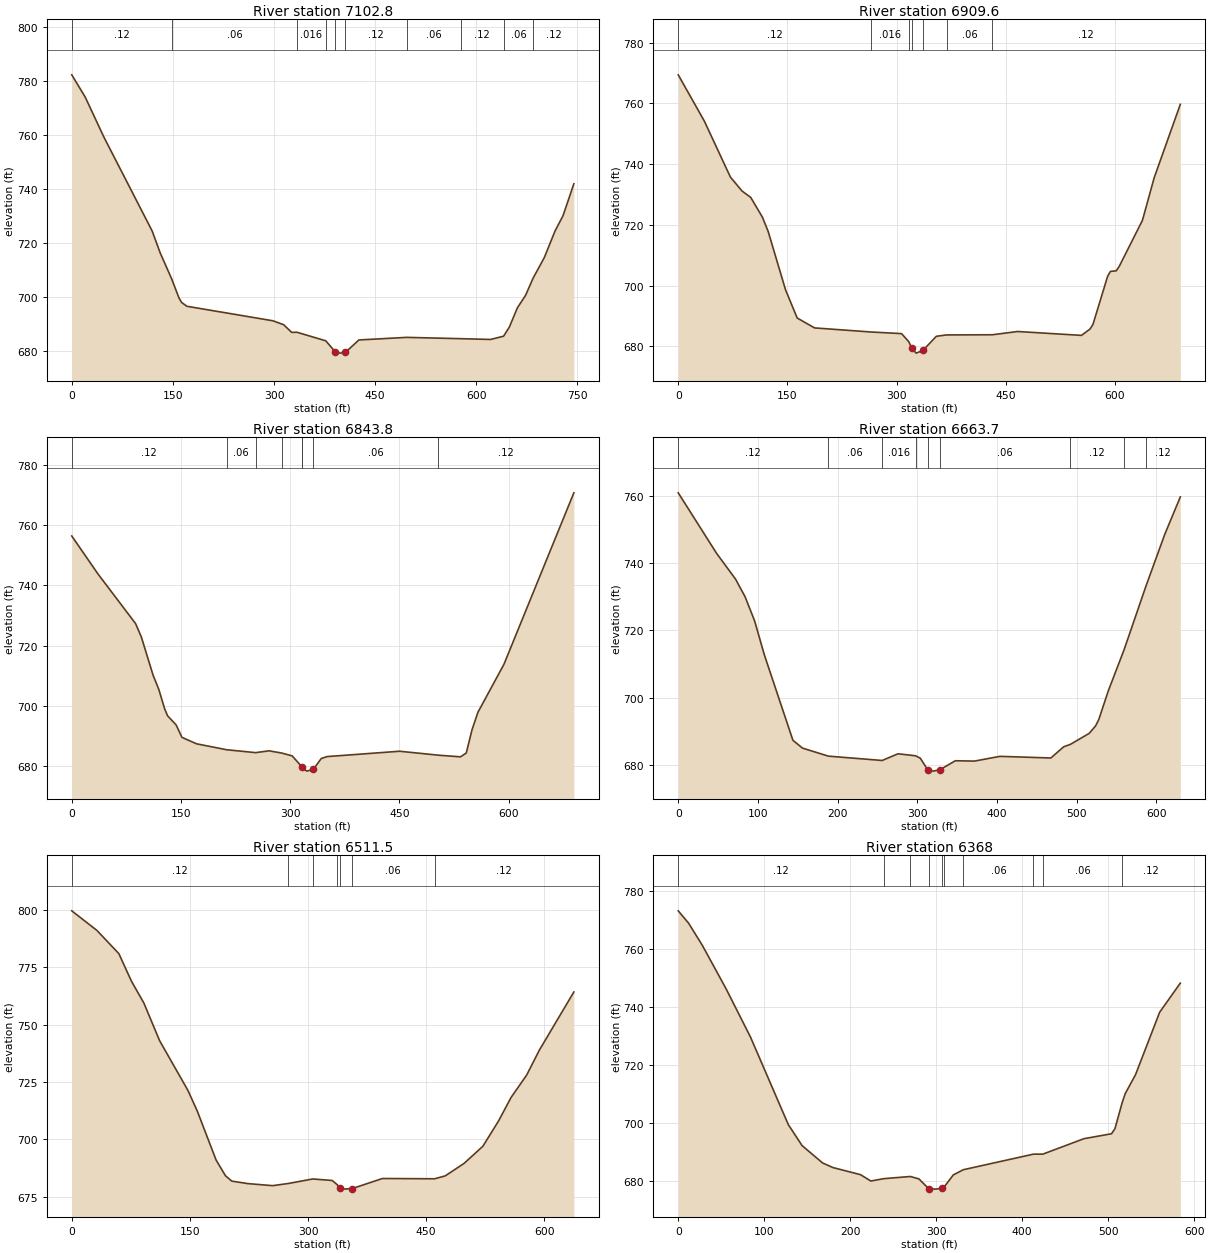
Type RM Length L Ch R = 1 ,7102.8  ,198.3,193.2,187.8
XS GIS Cut Line= 3
     1730153.134      401535.606     1730089.332      401715.294
     1729715.634      402124.148
#Sta/Elev= 30
       0   782.2    19.9  773.97    47.7   759.1   119.2  724.33   131.1  716.22
  148.29706.5009   158.9  699.56   162.9  697.83   170.8  696.41   298.3  691.04
   314.2  689.58   326.2  686.74  333.97686.7883  376.65683.6196   390.8  679.53
   397.9  679.05   405.8  679.31   425.8  683.93  496.69684.8895  576.72684.4056
     621  684.12  640.41685.3235     649  688.74   660.9  695.85   672.9  700.41
  684.19706.8375   700.8  714.46   716.7  724.31   728.6  730.01   744.6  741.81
#Mann= 10 ,-1 , 0
       0     .12       0  148.29     .06       0  333.97    .016       0
  376.65     .12       0   390.8    .045       0   405.8     .12       0
  496.69     .06       0  576.72     .12       0  640.41     .06       0
  684.19     .12       0
Bank Sta=390.8,405.8
XS Rating Curve= 0 ,0
Exp/Cntr=0.3,0.1

Type RM Length L Ch R = 1 ,6909.6  ,65.8,65.8,65.8
XS GIS Cut Line= 3
     1729995.061      401467.724     1729651.311      401966.423
     1729578.394      402008.089
#Sta/Elev= 30
       0  769.36    35.9  754.11    71.7  735.69    87.7   731.1    99.6     729
   115.6  722.52   123.5  717.84   147.4   698.6   163.4  689.31   187.3  686.05
  264.44 684.714   306.8  684.17  316.48  681.58     321  679.37   326.8  677.75
     336  678.62   354.6  683.29  368.52683.7356  431.54683.7943   466.2  684.87
   553.9  683.59   565.8   685.7   569.8  687.26   589.8     703   593.7  704.65
   601.7  704.84   605.7  706.26   637.7  721.47   653.7   735.4   689.7  759.64
#Mann= 7 ,-1 , 0
       0     .12       0  264.44    .016       0  316.48     .12       0
     321    .045       0     336     .12       0  368.52     .06       0
  431.54     .12       0
Bank Sta=321,336
XS Rating Curve= 0 ,0
Exp/Cntr=0.3,0.1

Type RM Length L Ch R = 1 ,6843.8  ,184,180.1,176.5
XS GIS Cut Line= 3
      1729936.12      401437.864      1729592.37      401936.562
     1729519.453      401978.228
#Sta/Elev= 30
       0  756.48    35.9  743.87    87.7   727.3    95.6  722.84   111.6   710.2
   119.5  705.44   127.5  699.01   131.5  696.64   143.4  693.55   151.4  689.42
   171.4  687.28  212.63685.3043  252.57684.3336     271  684.94  288.45684.1974
   302.8  683.25  316.71679.4537   316.8  679.42   322.8  678.18   331.8  678.77
   342.7  682.37   350.7  683.02   450.3   684.8  503.68683.4863     534  682.94
   541.9   684.2   549.9  692.01   557.9  697.75   593.7  713.76   689.7  770.85
#Mann= 8 ,-1 , 0
       0     .12       0  212.63     .06       0  252.57    .016       0
  288.45     .08       0  316.71     .06       0   316.8    .045       0
   331.8     .06       0  503.68     .12       0
Bank Sta=316.8,331.8
XS Rating Curve= 0 ,0
Exp/Cntr=0.3,0.1

Type RM Length L Ch R = 1 ,6663.7  ,158.9,152.2,143.8
XS GIS Cut Line= 3
     1729752.471      401333.158     1729480.336      401826.648
     1729425.648      401864.408
#Sta/Elev= 30
       0  760.88      48  742.95    71.9  735.25    83.9  730.01    95.9  722.81
   107.9  712.87   143.9  687.38   155.9  685.06  188.41682.6708  255.87681.3807
   275.8  683.37  297.73 682.779   303.8  682.05   313.1  678.58   319.8  678.22
   328.1   678.6   347.7   681.3   371.7   681.2   403.7  682.61   467.6  682.12
   483.6  685.44  491.97686.1579   515.6  689.42   523.6  691.62   527.6  693.47
   539.6  702.02  559.43714.2648  587.02733.2559   610.5  748.55     630  759.66
#Mann= 9 ,-1 , 0
       0     .12       0  188.41     .06       0  255.87    .016       0
  297.73     .12       0   313.1    .045       0   328.1     .06       0
  491.97     .12       0  559.43     .06       0  587.02     .12       0
Bank Sta=313.1,328.1
XS Rating Curve= 0 ,0
Exp/Cntr=0.3,0.1

Type RM Length L Ch R = 1 ,6511.5  ,144.2,143.5,142.9
XS GIS Cut Line= 2
     1729557.442      401235.774     1729366.825      401844.003
#Sta/Elev= 30
       0  799.64    31.9  791.11    59.8  780.98    75.7  769.02    91.6  759.41
   111.5  743.06   147.4  721.43   159.4  712.33   183.2  691.07   195.2  684.15
   203.2  681.85   223.1  680.78     255  679.87  274.96680.8195  305.91682.7856
   330.6  682.13  336.86680.3279   340.4  678.94   342.6  678.36   355.4  678.53
   394.4  682.99  460.67 682.865   474.1  684.13     498  689.56   521.9  697.04
   541.8  708.05   557.7   718.3   577.6  728.12   593.6  738.92   637.4  764.26
#Mann= 7 ,-1 , 0
       0     .12       0  274.96     .08       0  305.91    .016       0
  336.86     .06       0   340.4    .045       0   355.4     .06       0
  460.67     .12       0
Bank Sta=340.4,355.4
XS Rating Curve= 0 ,0
Exp/Cntr=0.3,0.1

Type RM Length L Ch R = 1 ,6368    ,40.5,40.4,40.5
XS GIS Cut Line= 2
     1729400.813      401239.322     1729235.449      401799.218
#Sta/Elev= 30
       0  773.14      12  768.91      28  761.26      56  746.07      84  729.64
     128  699.47     144  692.23   167.9  686.24   179.9  684.66   211.9  682.22
   223.9  680.03  239.09 680.841  269.88681.5857   279.9  680.75   291.4  677.34
   299.9  677.23   306.4  677.57   308.8677.8445   319.9  682.13  331.48683.9143
  413.07689.2853  423.86689.2798   471.8  694.62   503.8  696.31   507.8  698.06
  516.26707.0902   519.8  710.17   531.8  716.72   559.8   738.2   583.8  748.22
#Mann= 10 ,-1 , 0
       0     .12       0  239.09    .016       0  269.88     .06       0
   291.4    .045       0   306.4     .06       0   308.8    .016       0
  331.48     .06       0  413.07    .016       0  423.86     .06       0
  516.26     .12       0
Bank Sta=291.4,306.4
XS Rating Curve= 0 ,0
Exp/Cntr=0.3,0.1

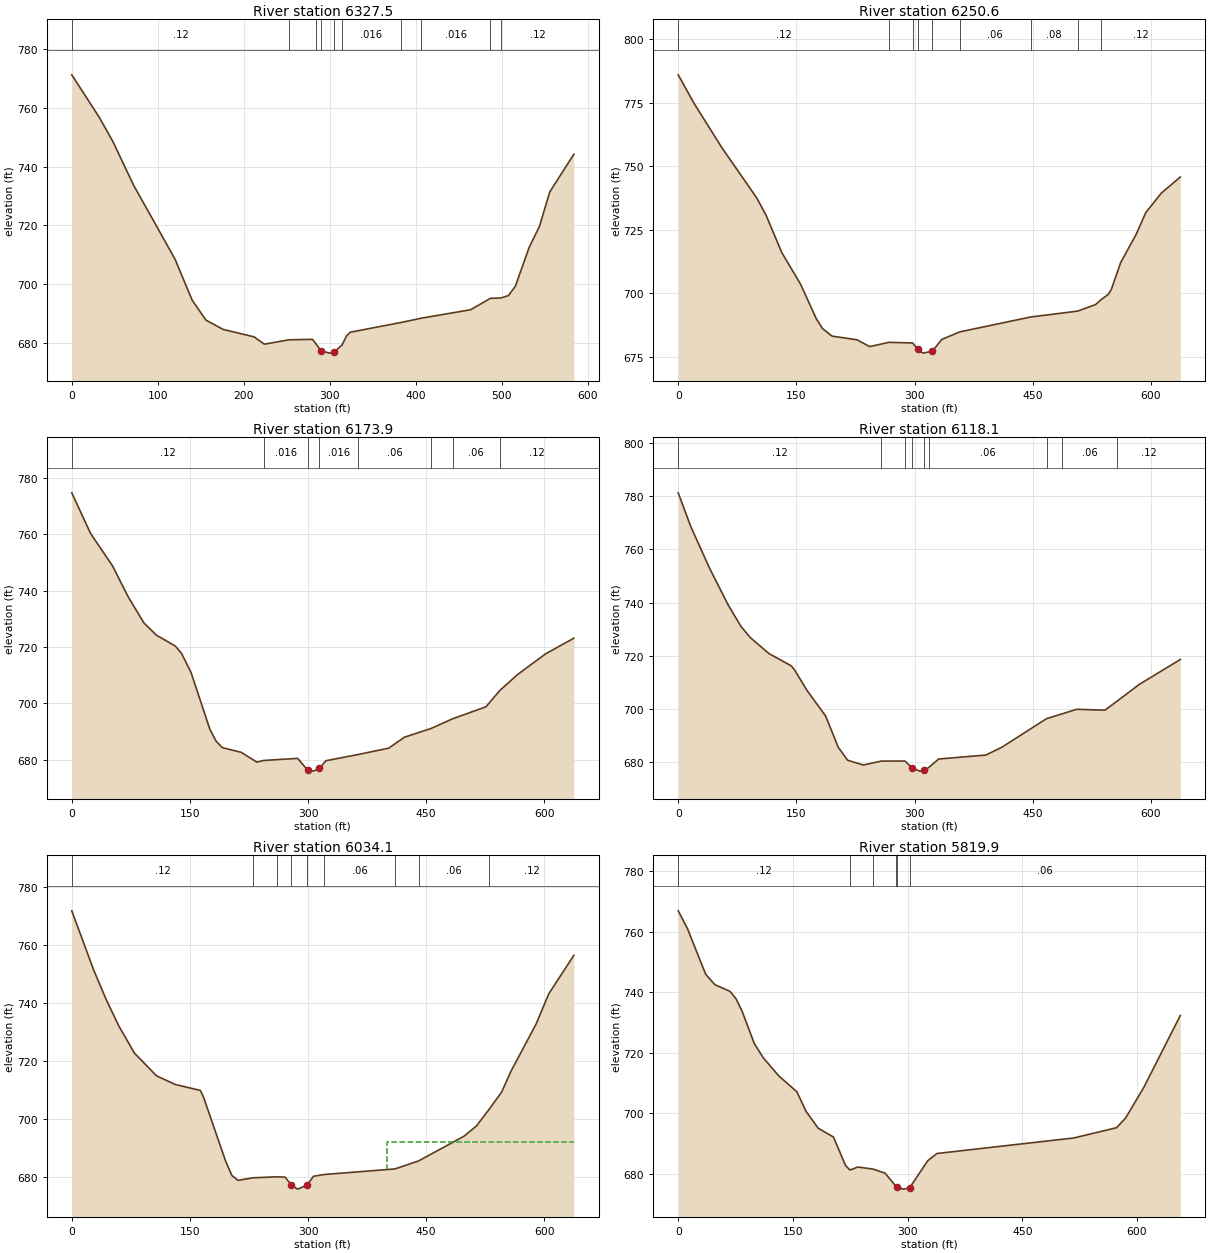
Type RM Length L Ch R = 1 ,6327.5  ,81.2,76.9,72.3
XS GIS Cut Line= 2
     1729362.619      401226.301     1729197.254      401786.197
#Sta/Elev= 30
       0   771.1      32  756.68      48  748.37      72   733.6     120  708.63
     140  694.66     156  687.91   175.9  684.76   211.9  682.24   223.9  679.75
  252.67681.2281   279.9  681.38  283.46680.0539   289.8  677.51   299.9  676.71
   304.8  677.01  314.26679.4741   319.9  682.73   323.9  683.81   382.5 687.078
  406.65688.5662   463.8  691.43  486.77695.2915  499.04695.4167   507.8  696.25
   515.8   699.4   531.8  712.54   543.8   719.7   555.8  731.38   583.8  744.17
#Mann= 10 ,-1 , 0
       0     .12       0  252.67    .016       0  283.46     .06       0
   289.8    .045       0   304.8     .06       0  314.26    .016       0
   382.5     .06       0  406.65    .016       0  486.77     .08       0
  499.04     .12       0
Bank Sta=289.8,304.8
XS Rating Curve= 0 ,0
Exp/Cntr=0.3,0.1

Type RM Length L Ch R = 1 ,6250.6  ,76.7,76.7,76.7
XS GIS Cut Line= 2
     1729259.554      401175.364      1729152.56      401803.719
#Sta/Elev= 30
       0  785.99    19.9  774.85    55.8  757.13    99.6  737.56   111.5  730.73
   131.5  716.01   155.4  703.54   175.3  689.97   183.2   686.1   195.2  683.15
   227.1  681.68     243  679.01  267.52680.6866  297.48 680.448   304.3  677.88
   310.7  676.44   322.7  677.23   334.6  681.83   357.4684.7954  447.28690.6559
   507.2692.9888   529.8  695.55  537.16697.5632   545.8  699.53   549.8   701.5
   561.7  712.09   581.6  723.34   593.6  731.78   613.5  739.48   637.4  745.76
#Mann= 9 ,-1 , 0
       0     .12       0  267.52    .016       0  297.48     .12       0
   304.3    .045       0   322.7     .12       0   357.4     .06       0
  447.28     .08       0   507.2     .06       0  537.16     .12       0
Bank Sta=304.3,322.7
XS Rating Curve= 0 ,0
Exp/Cntr=0.3,0.1

Type RM Length L Ch R = 1 ,6173.9  ,55.8,55.8,55.8
XS GIS Cut Line= 2
     1729183.165      401169.287     1729076.171      401797.642
#Sta/Elev= 30
       0  774.77    23.9  760.32    51.8   748.8    71.7  737.78    91.6  728.54
   107.6  724.18   131.5  720.32   139.4  717.69   151.4  710.95   175.3  690.79
   183.2  686.54   191.2  684.24   215.1  682.57     235  679.08  243.72 679.684
   286.8  680.42   299.3  676.28   306.8  675.89   314.3  676.85   322.7  679.59
  363.56681.7921   402.4  684.06   422.3  687.94  456.13691.0437   483.4694.4695
   525.8  698.75  543.32704.5086   565.7  710.16   601.6  717.57   637.4  723.12
#Mann= 8 ,-1 , 0
       0     .12       0  243.72    .016       0   299.3    .045       0
   314.3    .016       0  363.56     .06       0  456.13    .016       0
   483.4     .06       0  543.32     .12       0
Bank Sta=299.3,314.3
XS Rating Curve= 0 ,0
Exp/Cntr=0.3,0.1

Type RM Length L Ch R = 1 ,6118.1  ,84,84,84
XS GIS Cut Line= 2
     1729129.346      401155.399     1729022.352      401783.754
#Sta/Elev= 30
       0  781.29    15.9  768.61    39.8   752.9    63.7  738.96    79.7  731.02
    91.6  726.79   115.5  720.76   143.4  716.23   147.4   714.8   163.3  707.04
   187.2   697.3   203.2  685.55   215.1  680.69     235   678.9  257.81680.3781
  287.77 680.393   297.4   677.7   306.8   676.6   312.4  676.91  317.73677.9029
   330.6  681.16   390.4  682.64   410.3  685.48  467.53696.3223  487.41  698.15
   505.9  699.86   541.8  699.53  557.41702.9891   585.6  709.28   637.4  718.59
#Mann= 9 ,-1 , 0
       0     .12       0  257.81    .016       0  287.77     .12       0
   297.4    .045       0   312.4     .12       0  317.73     .06       0
  467.53    .016       0  487.41     .06       0  557.41     .12       0
Bank Sta=297.4,312.4
XS Rating Curve= 0 ,0
Exp/Cntr=0.3,0.1

Type RM Length L Ch R = 1 ,6034.1  ,214.8,214.2,213.3
XS GIS Cut Line= 2
     1729045.144      401152.794      1728938.15      401781.149
#Sta/Elev= 30
       0  771.63    27.9  751.19    43.8  741.02    59.8  731.94    79.7  722.58
   107.6   714.8   131.5  711.81   163.3  709.77   167.3  707.45   195.2  685.53
   203.2   680.5   211.1   678.8  230.49679.6888  260.45680.0222   270.9  679.91
   278.9  677.15   286.8  675.78   298.8  677.16   306.8   680.2  320.37680.8176
  410.26682.7378  440.22685.4822     498     694   513.9  697.58   530.1703.3545
   545.8  709.23   557.7  716.45   589.6  732.69   605.5     743   637.4  756.31
#Mann= 9 ,-1 , 0
       0     .12       0  230.49    .016       0  260.45     .12       0
   278.9    .045       0   298.8     .12       0  320.37     .06       0
  410.26     .12       0  440.22     .06       0   530.1     .12       0
#XS Ineff= 2 , 0
                          399.87          691.99
Permanent Ineff=
       F       F
Bank Sta=278.9,298.8
XS Rating Curve= 0 ,0
Exp/Cntr=0.3,0.1

Type RM Length L Ch R = 1 ,5819.9  ,299.1,300.9,302.1
XS GIS Cut Line= 3
     1728843.238      401099.408     1728749.488        401656.7
     1728780.738      401742.638
#Sta/Elev= 30
       0  766.93    11.9  761.14    35.8  746.03    47.8  742.54    67.7  740.31
    75.6  737.87    83.6   733.7    99.5  723.04   111.4   718.3   131.3  712.43
   155.2   707.1   167.2  700.64   183.1  695.06     203  692.18   218.9  682.72
  224.65681.2604   234.8  682.25  254.61 681.585   270.6  680.21  284.56675.9186
   286.5  675.55   294.5  674.95   302.5  675.34   326.3  684.34   338.3  686.72
   517.4  691.86   573.1  695.24     585  698.42   608.9  708.58   656.6  732.35
#Mann= 6 ,-1 , 0
       0     .12       0  224.65    .016       0  254.61     .12       0
  284.56     .06       0   286.5    .045       0   302.5     .06       0
Bank Sta=286.5,302.5
XS Rating Curve= 0 ,0
Exp/Cntr=0.3,0.1

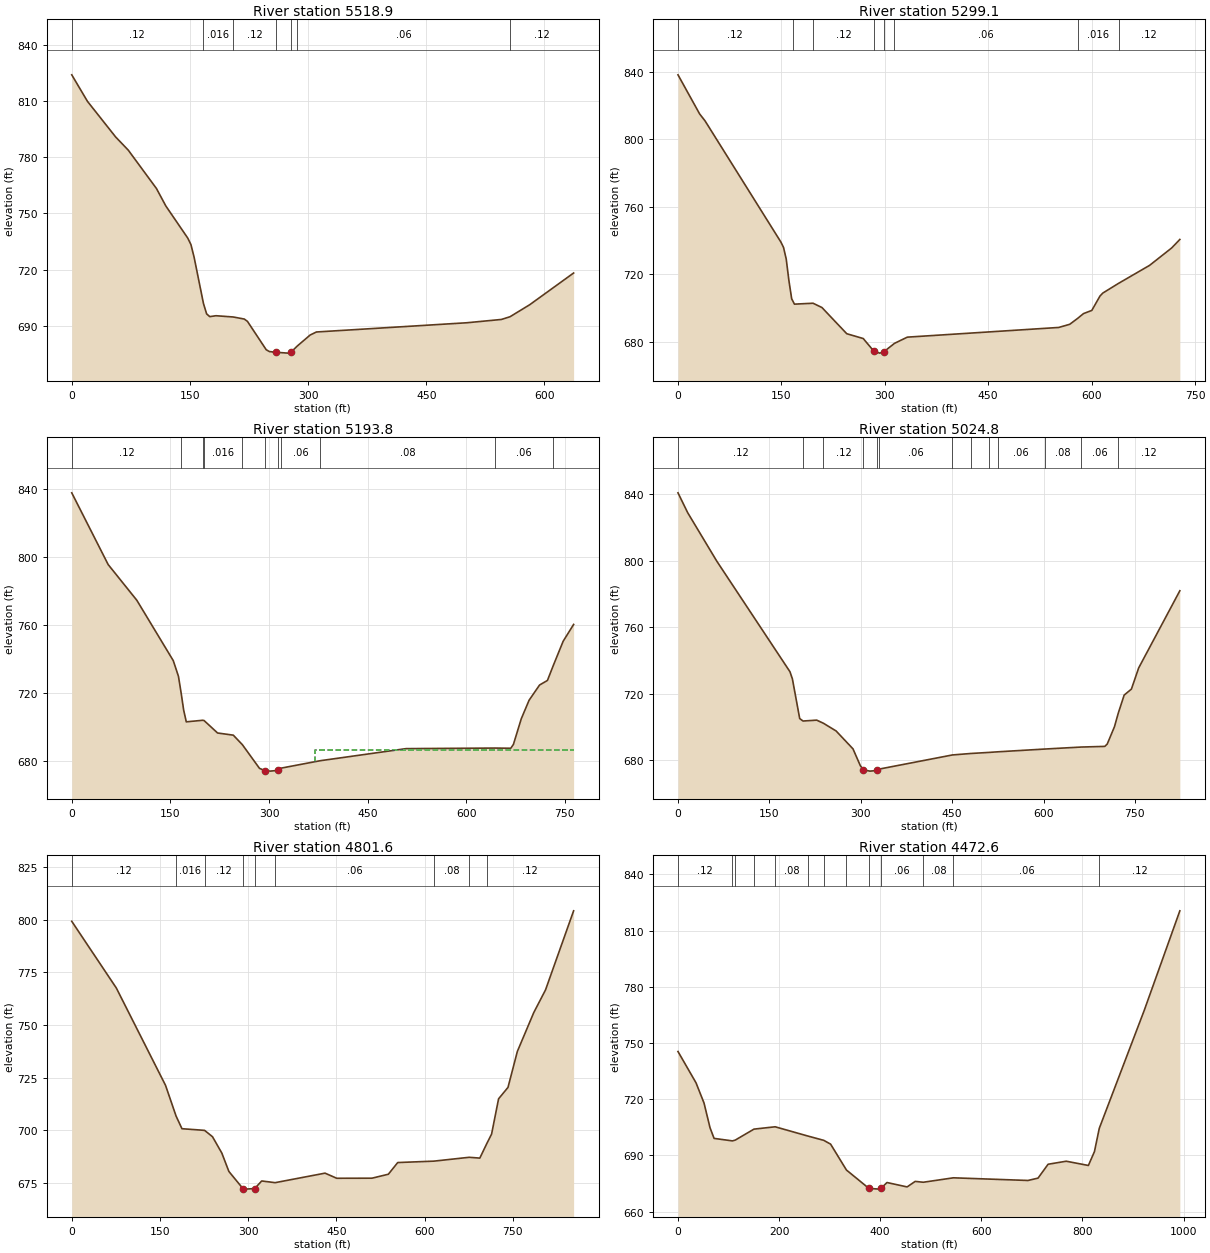
Type RM Length L Ch R = 1 ,5518.9  ,225.9,219.8,213.3
XS GIS Cut Line= 3
     1728552.751      401069.069     1728495.521      401382.385
     1728438.249      401695.693
#Sta/Elev= 30
       0  823.87    19.9  809.76    55.7  790.77    71.7  783.76   107.5  763.32
   119.4  754.02   147.3  736.86   151.3   733.4   155.3  726.71  165.98704.5118
   167.2  702.02   171.2  696.51   175.2  695.06   183.1  695.54  205.15 694.861
     219  693.77     223  692.54   246.8  677.45   250.8  676.46   259.5  676.06
   274.5  675.62   278.7  676.29  286.08 679.346   302.6  685.27   310.5  686.88
   501.6   691.8   545.4  693.56   556.3695.0107   581.3  701.41     637   718.3
#Mann= 7 ,-1 , 0
       0     .12       0  165.98    .016       0  205.15     .12       0
   259.5    .045       0   278.7     .12       0  286.08     .06       0
   556.3     .12       0
Bank Sta=259.5,278.7
XS Rating Curve= 0 ,0
Exp/Cntr=0.3,0.1

Type RM Length L Ch R = 1 ,5299.1  ,106.9,105.3,104.8
XS GIS Cut Line= 3
     1728345.035      401016.839     1728289.479       401167.88
      1728282.04      401734.825
#Sta/Elev= 30
       0  838.11    31.4  814.96    39.2  810.88   149.2  739.14   153.1   735.9
     157  729.02   160.9  716.24   164.9  705.51  166.34704.3616   168.9  702.32
  195.88702.8633   208.8  700.32   244.8  684.81   268.7  681.96   283.9  674.55
   292.7  673.32   298.9  674.23  314.03 679.106   332.6  682.78   552.2  688.52
   568.2  690.39  579.87693.9543   588.2  696.74   600.2   698.6   612.1  707.14
   616.1  708.86  638.94 714.617     684  725.28     716  735.58   727.9  740.63
#Mann= 8 ,-1 , 0
       0     .12       0  166.34    .016       0  195.88     .12       0
   283.9    .045       0   298.9     .12       0  314.03     .06       0
  579.87    .016       0  638.94     .12       0
Bank Sta=283.9,298.9
XS Rating Curve= 0 ,0
Exp/Cntr=0.3,0.1

Type RM Length L Ch R = 1 ,5193.8  ,159.7,169,177
XS GIS Cut Line= 3
      1728275.53      400992.638     1728185.686      401186.648
     1728181.779      401736.127
#Sta/Elev= 30
       0  837.94    55.4   795.6      99  774.53   154.4  738.92   162.3  729.65
  166.53719.4144   170.2  709.75   174.2  702.81  199.08703.7335  201.16703.6055
   221.8  696.23   245.7  694.95  259.51689.3265   285.5  675.38   293.4  674.09
   301.4  673.73   313.5  674.14  318.58 675.508  377.66679.8616   508.5     687
  643.48687.3359   667.7  687.23   671.7  689.46   683.7  704.64   695.6  715.57
   711.5  724.53   723.5  727.24  732.09735.7673   747.4  750.37   763.3  760.28
#Mann= 11 ,-1 , 0
       0     .12       0  166.53    .016       0  199.08     .12       0
  201.16    .016       0  259.51     .12       0   293.4    .045       0
   313.5     .12       0  318.58     .06       0  377.66     .08       0
  643.48     .06       0  732.09     .12       0
#XS Ineff= 2 , 0
                           369.7          685.94
Permanent Ineff=
       F       F
Bank Sta=293.4,313.5
XS Rating Curve= 0 ,0
Exp/Cntr=0.3,0.1

Type RM Length L Ch R = 1 ,5024.8  ,225,223.2,221.4
XS GIS Cut Line= 3
     1728193.348      400958.506     1728050.119      401125.173
      1727919.91      401715.016
#Sta/Elev= 30
       0  840.75      16  828.75    63.9  799.52   183.8  733.11   187.8  728.82
   199.8  704.93  205.31703.4443   227.7  703.98  238.78702.0963   259.5  697.48
   287.3  686.68   299.2  676.66   304.4  674.09   315.1   673.3     327  673.69
  329.52674.4712  450.51683.0309  480.75683.9175     511684.5654  525.29684.9271
  601.74  686.58   662.3687.7966   700.6  688.18   704.6   689.6   716.5  700.03
  722.72708.1783   732.4  719.05   744.3  722.66   756.2  735.38   823.8  781.83
#Mann= 13 ,-1 , 0
       0     .12       0  205.31    .016       0  238.78     .12       0
   304.4    .045       0     327     .12       0  329.52     .06       0
  450.51     .08       0  480.75     .06       0     511     .08       0
  525.29     .06       0  601.74     .08       0   662.3     .06       0
  722.72     .12       0
Bank Sta=304.4,327
XS Rating Curve= 0 ,0
Exp/Cntr=0.3,0.1

Type RM Length L Ch R = 1 ,4801.6  ,348.7,329,308.1
XS GIS Cut Line= 2
     1727867.604      400862.325     1727718.298      401702.603
#Sta/Elev= 30
       0  799.16    75.8   767.5   159.5   721.3  177.36 706.776   187.4  700.75
  225.84699.9612   239.3  696.96   255.2  689.18   267.2  680.46   291.4  672.24
   295.1  672.08   311.1  672.35     323  675.95  345.83675.1451   430.7  679.66
   450.6  677.23   510.5  677.27   538.4  679.15   554.3  684.69  615.82685.3581
  675.81687.1833   693.9   686.8  705.81 693.717   713.9  698.18   725.8  714.93
   741.8  720.34   757.7  737.39   785.6  755.83   805.6  766.59   853.4  804.13
#Mann= 9 ,-1 , 0
       0     .12       0  177.36    .016       0  225.84     .12       0
   291.4    .045       0   311.1     .12       0  345.83     .06       0
  615.82     .08       0  675.81     .06       0  705.81     .12       0
Bank Sta=291.4,311.1
XS Rating Curve= 0 ,0
Exp/Cntr=0.3,0.1

Type RM Length L Ch R = 1 ,4472.6  ,319.3,295.8,278.3
XS GIS Cut Line= 4
     1727563.785      400832.811     1727426.632      400964.756
     1727683.576      401574.131      1727650.59      401711.283
#Sta/Elev= 30
       0  745.49    35.7  728.76    51.5  717.99    63.4  704.78    71.4   699.1
   107.7697.7703  113.28698.1937   150.3 704.054  192.26705.2997  256.37700.3992
  288.42698.0576   301.9  696.04  333.22682.2206   377.6  672.43   397.5  672.02
   401.5  672.42   413.4  675.55   453.2   673.2   469.2  676.14  485.26675.6952
  544.85678.0607   692.3  676.64   712.2   677.9   732.1   685.3     768  686.92
   811.8  684.65   823.8  692.07  833.33704.4611   922.2   767.4   992.7   820.6
#Mann= 13 ,-1 , 0
       0     .12       0   107.7     .08       0  113.28     .06       0
   150.3    .016       0  192.26     .08       0  256.37    .016       0
  288.42     .12       0  333.22    .016       0   377.6    .045       0
   401.5     .06       0  485.26     .08       0  544.85     .06       0
  833.33     .12       0
Bank Sta=377.6,401.5
XS Rating Curve= 0 ,0
Exp/Cntr=0.3,0.1