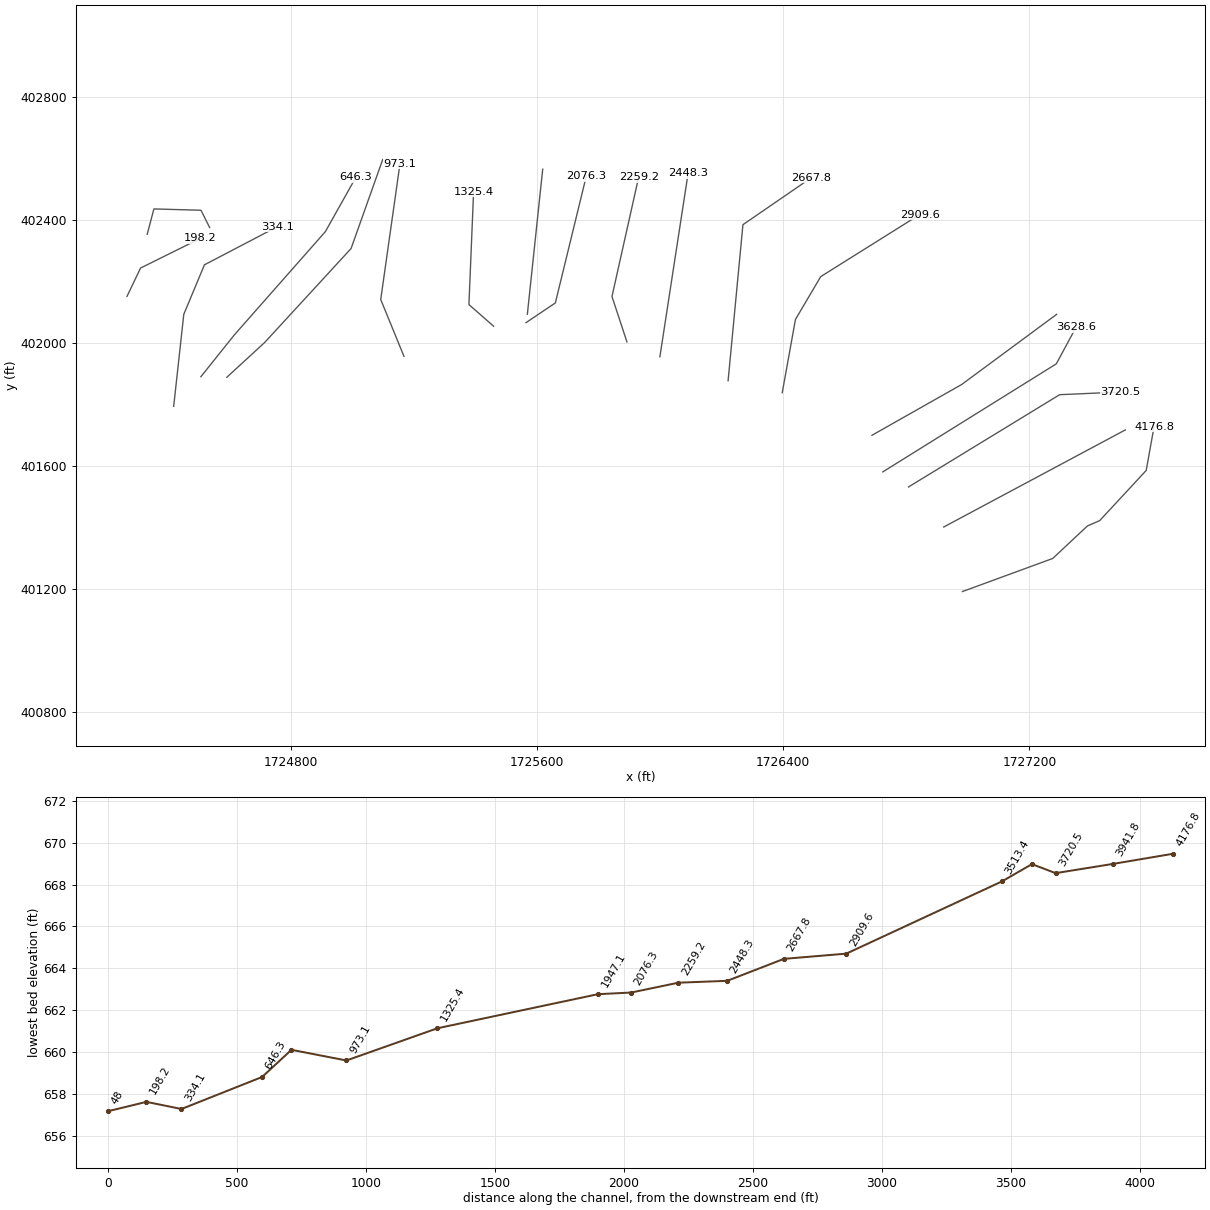
HEC-RAS study ROCKCK.prj: ROCKCK

--- ROCKCK.g01 (geometry) --- (continued)

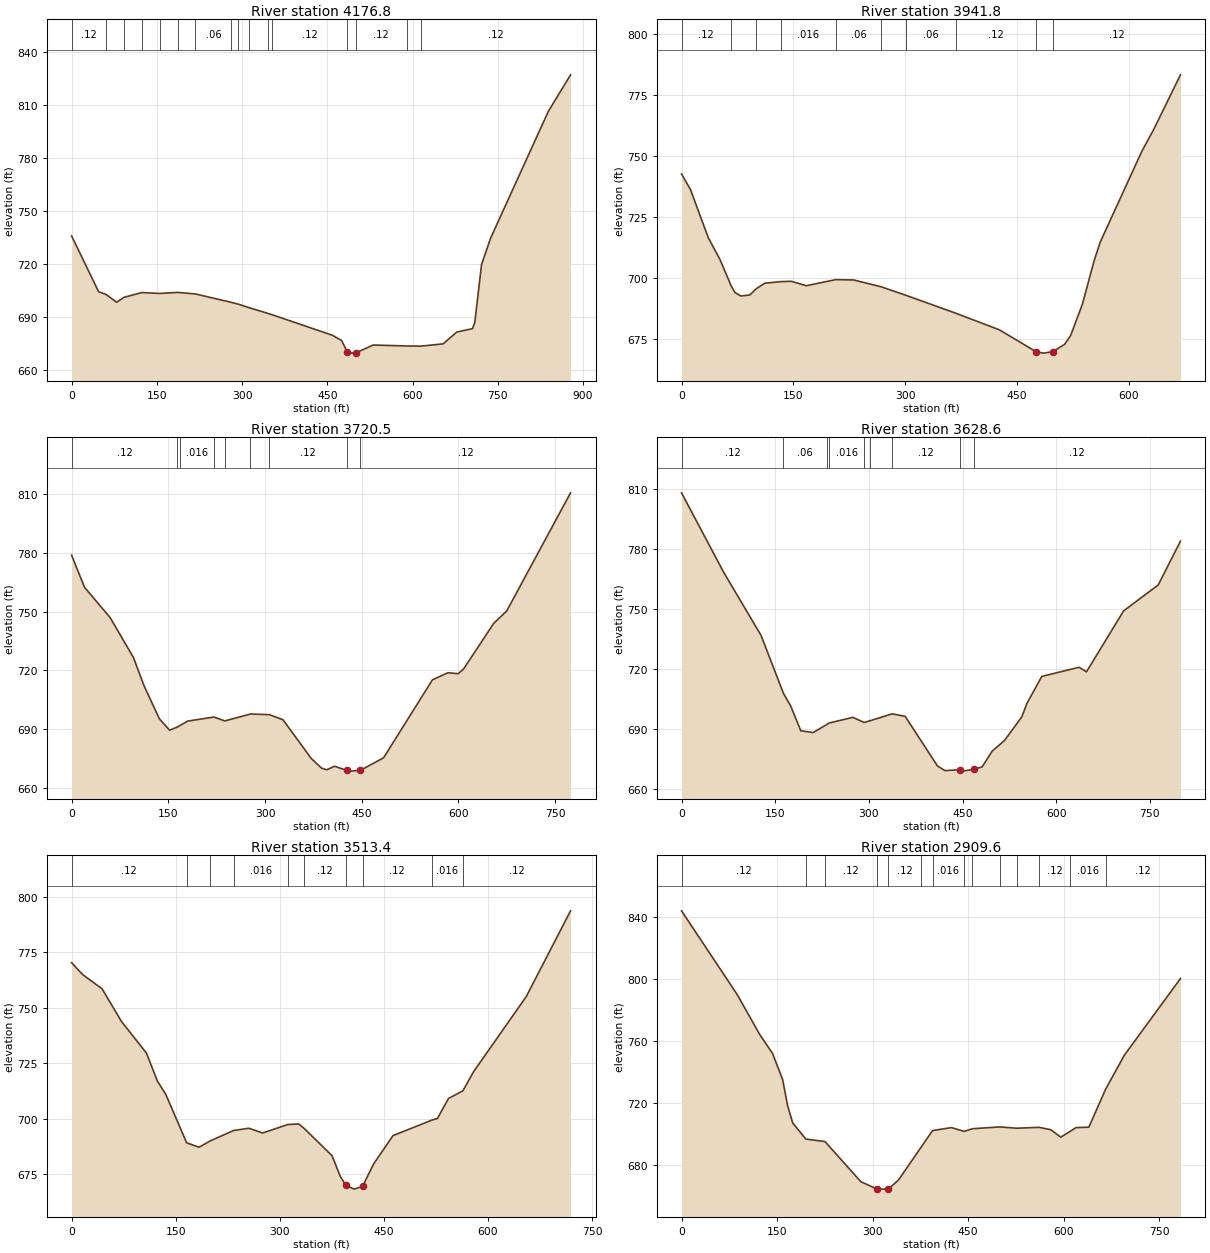
Type RM Length L Ch R = 1 ,4176.8  ,238.4,235.1,224.6
XS GIS Cut Line= 6
     1726982.187       401190.45      1727275.59      401298.089
     1727388.438      401403.992     1727428.368      401421.353
      1727579.41      401584.547     1727604.957      401727.013
#Sta/Elev= 30
       0  735.96    47.5   704.3   60.65702.7648    79.1  698.34   92.11701.1146
  123.57703.8348  155.03703.3277  186.49703.9282  217.95 703.031  280.88698.2812
  293.22697.2549  312.33695.2631  345.97691.9473  352.78691.2762   459.4  679.54
   475.2  676.59   484.8  670.26   487.1  669.48   499.8  669.59   530.7  674.08
  590.02673.5349  615.51673.4655   653.8  674.75   677.6  681.41   705.4  683.38
   709.4  686.91   721.3  719.68   737.1   734.6   838.8  806.58   877.9  827.32
#Mann= 16 ,-1 , 0
       0     .12       0   60.65     .06       0   92.11     .08       0
  123.57    .016       0  155.03     .08       0  186.49    .016       0
  217.95     .06       0  280.88     .12       0  293.22     .06       0
  312.33     .12       0  345.97     .06       0  352.78     .12       0
   484.8    .045       0   499.8     .12       0  590.02     .06       0
  615.51     .12       0
Bank Sta=484.8,499.8
XS Rating Curve= 0 ,0
Exp/Cntr=0.3,0.1

Type RM Length L Ch R = 1 ,3941.8  ,217.3,221.3,223.6
XS GIS Cut Line= 2
     1726921.424      401400.519     1727511.701      401716.492
#Sta/Elev= 30
       0  742.61      12  736.21    35.9  716.43    51.8  707.34   66.51 696.703
    71.7  693.89    79.7  692.46    91.7  692.89  100.01695.3917   111.6   697.7
  133.51 698.385   147.5  698.49   167.4  696.68  206.96699.1904   231.2  699.04
  267.51696.2814  301.02692.7598  368.02685.3854   426.4  678.58   476.2   669.5
   486.2  668.99   498.2  669.61   514.1   672.6   522.1  676.18     538  689.19
     554  707.34   561.9  714.64   617.7  751.94   633.7  760.95   669.5  783.34
#Mann= 10 ,-1 , 0
       0     .12       0   66.51     .06       0  100.01     .08       0
  133.51    .016       0  206.96     .06       0  267.51     .12       0
  301.02     .06       0  368.02     .12       0   476.2    .045       0
   498.2     .12       0
Bank Sta=476.2,498.2
XS Rating Curve= 0 ,0
Exp/Cntr=0.3,0.1

Type RM Length L Ch R = 1 ,3720.5  ,91.7,91.9,92
XS GIS Cut Line= 3
      1726806.84      401530.728      1727298.16      401831.075
     1727496.076      401839.755
#Sta/Elev= 30
       0  778.82      20  762.49      60  746.86      96  726.53     112  712.43
     136  695.36     152  689.43  164.13691.1031  168.41691.8822     180   694.1
  220.76696.1754  237.64694.1917  277.38697.7118  306.88697.3951   327.9  694.78
   371.9  674.95   387.9  670.03   395.9  669.25   407.9  671.05     427  668.88
   431.9  668.55   447.9  668.95   483.9  675.34   559.8   715.2   583.8  718.81
   599.6  718.32   607.6  720.52   655.1  744.17   674.9  750.33     774   810.7
#Mann= 9 ,-1 , 0
       0     .12       0  164.13     .06       0  168.41    .016       0
  220.76     .06       0  237.64    .016       0  277.38     .06       0
  306.88     .12       0     427    .045       0   447.9     .12       0
Bank Sta=427,447.9
XS Rating Curve= 0 ,0
Exp/Cntr=0.3,0.1

Type RM Length L Ch R = 1 ,3628.6  ,114.2,115.2,117.2
XS GIS Cut Line= 3
     1726723.446      401579.877     1727287.248       401931.44
      1727351.05       402049.93
#Sta/Elev= 30
       0  808.31    67.6  768.47   127.3  736.97  163.19707.9443   175.1  701.41
     191  689.19   210.9  688.29  232.81692.3538  236.36693.0764   274.5   695.9
  292.18693.3509  302.42694.2432  337.23697.6472   358.1  696.42   409.8   671.6
   421.7  669.24   445.6  669.67   449.6  668.98     468  669.88   481.4   671.1
   497.3  678.92   517.2  684.32   545.1  696.24     553  702.78   576.9  716.39
   636.6  720.97   648.5  718.69     708  749.22   763.4  762.18     799  784.11
#Mann= 9 ,-1 , 0
       0     .12       0  163.19     .06       0  232.81     .08       0
  236.36    .016       0  292.18     .06       0  302.42    .016       0
  337.23     .12       0   445.6    .045       0     468     .12       0
Bank Sta=445.6,468
XS Rating Curve= 0 ,0
Exp/Cntr=0.3,0.1

Type RM Length L Ch R = 1 ,3513.4  ,586.6,603.8,620.2
XS GIS Cut Line= 3
     1726688.195      401698.961     1726979.861      401864.326
     1727288.368      402092.538
#Sta/Elev= 30
       0  770.35      16  764.98    43.9  758.58    71.8  743.86   107.8  729.59
   123.7  716.88   135.7  710.94  165.76 689.078   183.6  687.07  199.71689.9139
  233.66694.6482   255.4  695.63   275.4   693.5  311.54697.3144   327.3  697.59
  335.54695.4326   375.3  683.25   387.2  673.87   395.2  669.82   407.2  668.16
   419.2  669.39   435.2  679.53   463.2  692.33  519.23699.3229   527.2  700.06
   543.1  709.07   563.9 712.546   579.1  721.09   655.1  755.05     719  793.77
#Mann= 10 ,-1 , 0
       0     .12       0  165.76     .06       0  199.71     .08       0
  233.66    .016       0  311.54     .06       0  335.54     .12       0
   395.2    .045       0   419.2     .12       0  519.23    .016       0
   563.9     .12       0
Bank Sta=395.2,419.2
XS Rating Curve= 0 ,0
Exp/Cntr=0.3,0.1

Type RM Length L Ch R = 1 ,2909.6  ,224.2,241.8,259.1
XS GIS Cut Line= 4
     1726396.623       401837.69     1726439.592      402075.971
     1726521.623      402215.294     1726843.238      402417.117
#Sta/Elev= 30
       0  843.65    87.3  789.91     123     764   142.9  751.97   158.8  735.18
   166.7  718.18   174.6  707.28  195.24696.8737  225.25695.3112   281.6  669.47
     307  664.77     321   664.7   324.9  664.79   340.7  670.55  375.99691.5364
  394.23702.3505   423.8  704.27  443.84701.8407  456.88703.5412  499.41704.6973
  526.62703.8591  561.49704.4297   579.7  702.92   595.6  698.13  610.54701.9163
   619.6  704.28   639.6  704.52   666.1  729.06   695.6  750.95   783.5  800.11
#Mann= 14 ,-1 , 0
       0     .12       0  195.24    .016       0  225.25     .12       0
     307    .045       0   324.9     .12       0  375.99     .08       0
  394.23    .016       0  443.84     .08       0  456.88    .016       0
  499.41     .06       0  526.62    .016       0  561.49     .12       0
  610.54    .016       0   666.1     .12       0
Bank Sta=307,324.9
XS Rating Curve= 0 ,0
Exp/Cntr=0.3,0.1

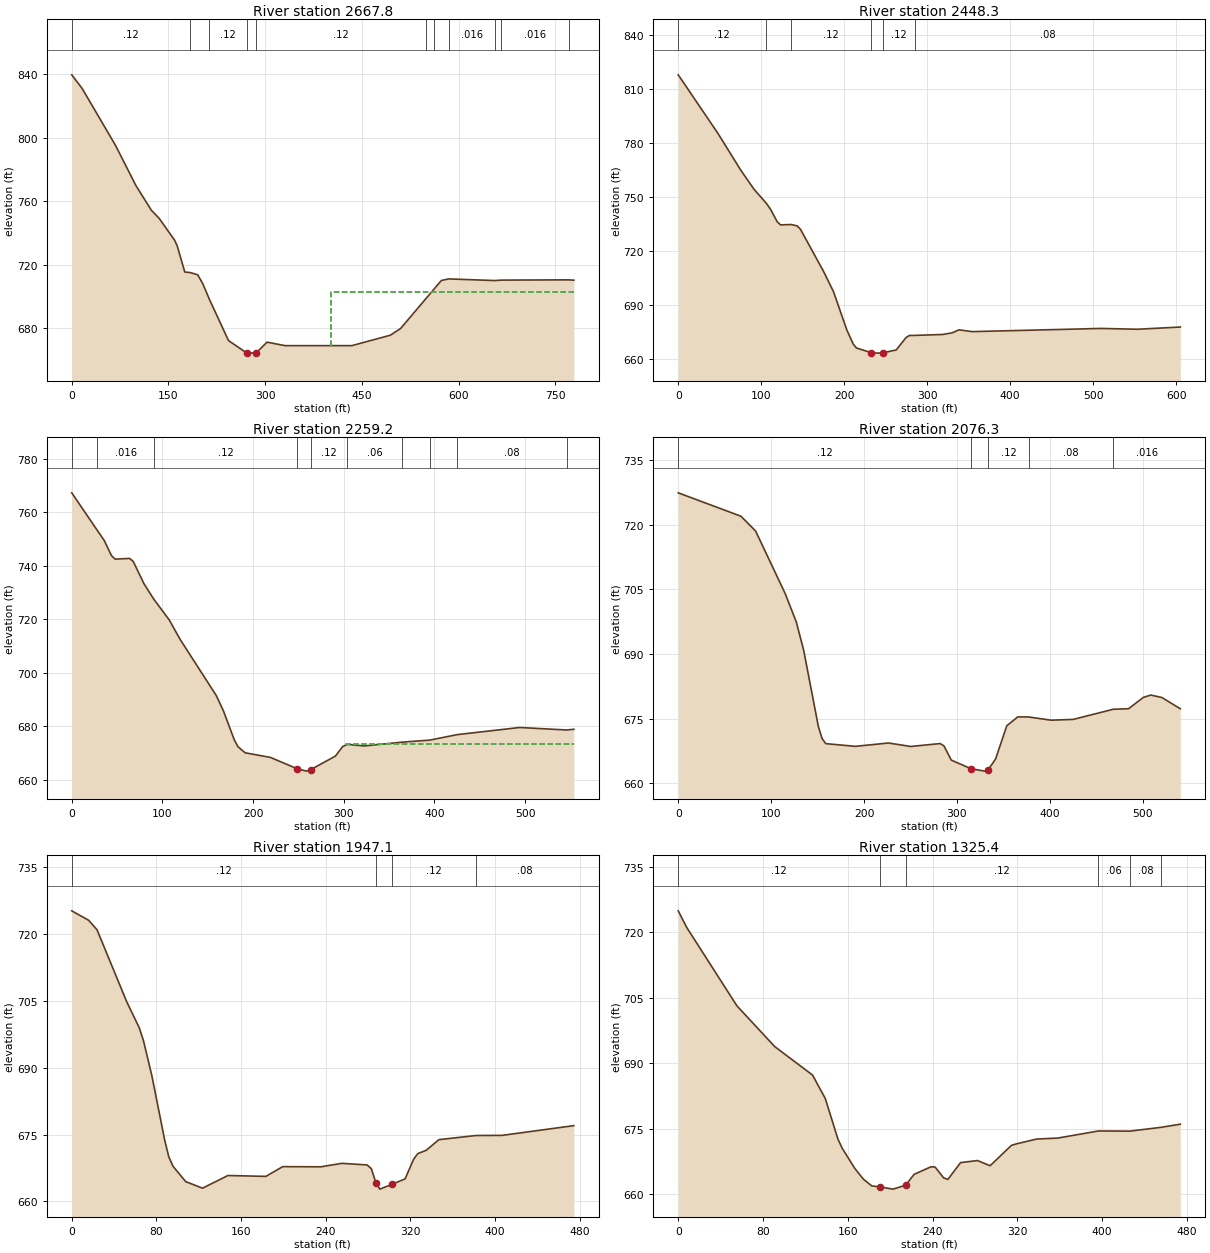
Type RM Length L Ch R = 1 ,2667.8  ,221.8,219.5,216.8
XS GIS Cut Line= 3
     1726220.692      401876.475     1726268.869      402384.287
     1726490.223      402536.631
#Sta/Elev= 30
       0  839.63    15.9  831.17    67.8  795.26    99.6  769.84   123.5  754.39
   135.5  749.32   159.4   735.6   163.4  732.16   175.3  715.52  183.72715.1647
   195.3  713.77   203.2  708.18  213.39698.4094   243.1  672.36   271.2   664.6
     275  664.45   286.2  664.66   302.9  671.36   330.8  669.16   434.4  669.15
   494.2  675.73   510.1  679.96  548.82 698.514  562.14704.8394   573.3  710.18
  584.67711.1642  656.38710.1226  666.33710.4099  770.52710.5739   778.8  710.37
#Mann= 11 ,-1 , 0
       0     .12       0  183.72    .016       0  213.39     .12       0
   271.2    .045       0   286.2     .12       0  548.82     .06       0
  562.14     .08       0  584.67    .016       0  656.38     .08       0
  666.33    .016       0  770.52     .06       0
#XS Ineff= 2 , 0
                          402.57          702.81
Permanent Ineff=
       F       F
Bank Sta=271.2,286.2
XS Rating Curve= 0 ,0
Exp/Cntr=0.3,0.1

Type RM Length L Ch R = 1 ,2448.3  ,190.4,189.1,185.1
XS GIS Cut Line= 2
     1725998.993      401954.454     1726090.828      402552.402
#Sta/Elev= 30
       0  817.68    47.8  785.24    75.6  764.66    91.5  754.14  106.15 746.482
   111.4  743.02   119.4  736.13   123.4  734.49  136.03734.6873   143.3  733.95
   147.3  732.05   175.1  708.72   187.1  697.47     203  676.44   210.9  668.36
   214.9   666.2   232.2  663.74   238.8   663.4   247.2  663.62   262.7  665.17
   274.6  672.08   278.6  673.19  285.44673.2316   318.4  673.73   330.3  674.66
   338.3  676.31   354.2  675.32   509.4  677.09   553.2  676.64     605  677.86
#Mann= 6 ,-1 , 0
       0     .12       0  106.15    .016       0  136.03     .12       0
   232.2    .045       0   247.2     .12       0  285.44     .08       0
Bank Sta=232.2,247.2
XS Rating Curve= 0 ,0
Exp/Cntr=0.3,0.1

Type RM Length L Ch R = 1 ,2259.2  ,182.8,182.9,183.4
XS GIS Cut Line= 3
      1725891.91       402002.95     1725843.299      402150.519
     1725930.104      402539.408
#Sta/Elev= 30
       0  767.19   28.31753.0993    35.8  749.41    43.8  743.76    47.8  742.44
    63.7  742.71    67.7  741.64    79.7  733.23   90.51727.4769   107.6  719.71
   119.5   712.5   159.4  691.52   167.3  685.79   179.3  674.95   183.3  672.44
   191.2  670.16   219.1  668.43   248.7   664.2     259  663.31   263.7  663.89
   290.8  668.92   298.8  672.49  304.08 673.292   322.7  672.71  364.61 674.135
  394.87674.8817  425.13676.9308   494.1   679.6  546.18678.6586   553.8  678.93
#Mann= 10 ,-1 , 0
       0     .12       0   28.31    .016       0   90.51     .12       0
   248.7    .045       0   263.7     .12       0  304.08     .06       0
  364.61     .08       0  394.87     .06       0  425.13     .08       0
  546.18    .016       0
#XS Ineff= 2 , 0
       0                   302.8       0  673.34
Permanent Ineff=
       F       F
Bank Sta=248.7,263.7
XS Rating Curve= 0 ,0
Exp/Cntr=0.3,0.1

Type RM Length L Ch R = 1 ,2076.3  ,124.3,129.2,134.1
XS GIS Cut Line= 3
     1725563.785       402065.45     1725659.271      402129.686
     1725759.965      402542.881
#Sta/Elev= 30
       0  727.42    67.5  721.99    83.3  718.55   115.1  704.05     127   697.5
     135  690.91   150.8  673.22   154.8  670.41   158.8  669.22   190.6  668.59
   226.4  669.37   250.2  668.56     282  669.24     286  668.69   293.9   665.4
     315  663.41   329.7  662.84   333.7  663.18   341.6  665.67   353.6  673.35
   365.5  675.43  377.11675.4066   401.3  674.66   425.1  674.84  468.31677.1996
   484.7  677.32   500.6  679.95   508.6  680.49   520.5  679.93   540.4  677.31
#Mann= 5 ,-1 , 0
       0     .12       0     315    .045       0   333.7     .12       0
  377.11     .08       0  468.31    .016       0
Bank Sta=315,333.7
XS Rating Curve= 0 ,0
Exp/Cntr=0.3,0.1

Type RM Length L Ch R = 1 ,1947.1  ,615.8,621.7,237.2
XS GIS Cut Line= 2
     1725568.298      402092.909     1725618.212      402564.915
#Sta/Elev= 30
       0  725.26      16  723.13    23.9  720.99    51.8  704.92    63.8  698.99
    67.8  696.08    75.8  688.14    87.8  673.82    91.7  670.03    95.7  667.89
   107.7  664.45   123.6  662.97   147.6  665.82   183.5  665.62   199.4  667.81
   235.3  667.77   255.3  668.55   279.2  668.19   283.2  667.35   287.5  664.17
   291.2  662.76   302.5  663.82   315.1  665.06   323.1  669.45   327.1  670.74
     335  671.47     347  673.87  382.08674.8026   406.8  674.83   474.6  677.02
#Mann= 4 ,-1 , 0
       0     .12       0   287.5    .045       0   302.5     .12       0
  382.08     .08       0
Bank Sta=287.5,302.5
XS Rating Curve= 0 ,0
Exp/Cntr=0.3,0.1

Type RM Length L Ch R = 1 ,1325.4  ,352.6,352.3,427.2
XS GIS Cut Line= 3
     1725458.706      402053.847     1725378.411      402124.377
     1725393.602       402491.13
#Sta/Elev= 30
       0  724.92     7.9  721.15    55.4  703.14      91  693.82   126.8  687.27
   138.8   681.9   150.8  672.55   154.8  670.49   166.7  665.87   174.7  663.43
   182.7  661.86   190.4  661.65   202.6  661.13   214.6  662.01   222.6  664.51
   238.5  666.25   242.5  666.18   250.5  663.71   254.5  663.36   266.5  667.21
   282.4  667.68   294.4   666.5   314.4  671.14   318.3  671.45   338.3  672.61
   358.2  672.83  396.55674.4561  426.11674.4199  455.67 675.291   473.9  676.02
#Mann= 6 ,-1 , 0
       0     .12       0   190.4    .045       0   214.6     .12       0
  396.55     .06       0  426.11     .08       0  455.67     .06       0
Bank Sta=190.4,214.6
XS Rating Curve= 0 ,0
Exp/Cntr=0.3,0.1

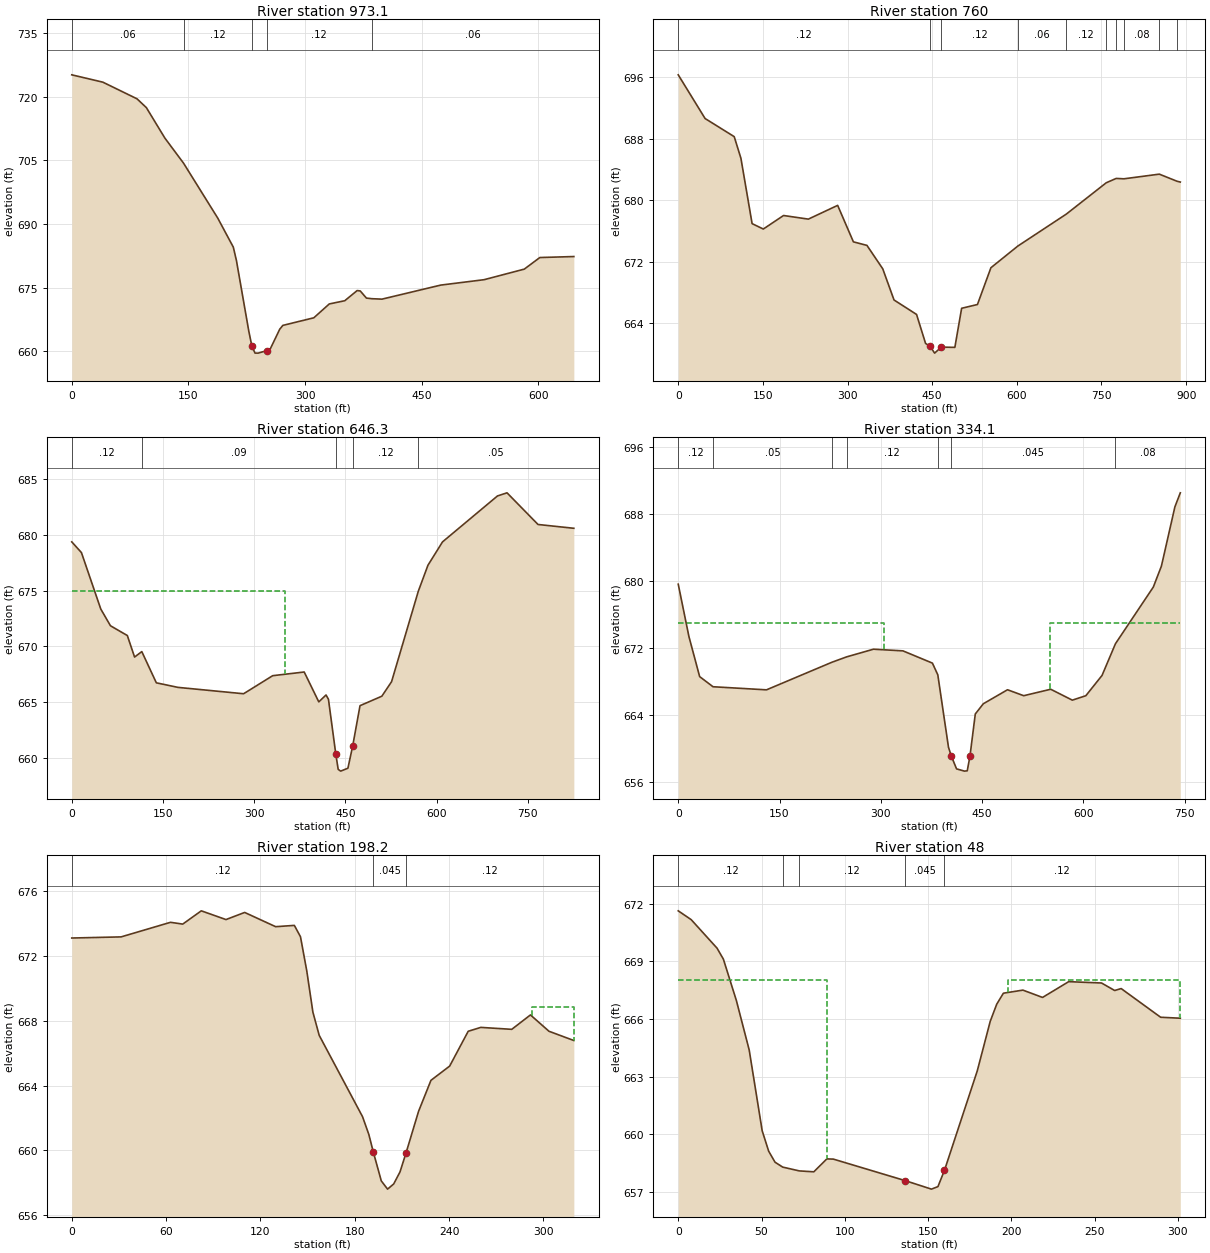
Type RM Length L Ch R = 1 ,973.1   ,231.4,213.1,180.5
XS GIS Cut Line= 3
     1725167.306      401955.902     1725091.785      402140.797
     1725154.285      402582.204
#Sta/Elev= 30
       0  725.12      40  723.39    83.9  719.47    95.9   717.4   119.8   710.2
  143.69704.3249   187.7  691.38   207.7  684.54   211.7   681.4   227.6  664.77
   231.6   661.2   235.6   659.6   239.5  659.59   250.7  660.17   255.4  660.66
   267.4  665.23   271.4  666.12   311.2  667.91   331.1  671.17     351  671.93
   366.9  674.32   370.9  674.23   378.8  672.55  385.97672.4037   398.8   672.3
   474.4  675.61   530.1  676.88   581.8  679.37   601.8   682.1   645.5  682.33
#Mann= 5 ,-1 , 0
       0     .06       0  143.69     .12       0   231.6    .045       0
   250.7     .12       0  385.97     .06       0
Bank Sta=231.6,250.7
XS Rating Curve= 0 ,0
Exp/Cntr=0.3,0.1

Type RM Length L Ch R = 1 ,760     ,113.8,113.7,122.5
XS GIS Cut Line= 4
     1724591.736      401887.831     1724714.349      402000.679
     1724995.382      402306.668     1725098.296      402596.527
#Sta/Elev= 30
       0  696.34    47.6  690.65    99.2  688.29   111.1  685.47   130.9  676.96
   150.8  676.26   186.6  678.02   230.6  677.55   282.5  679.34   310.4  674.59
   334.4  674.13   362.4  671.08   382.4  667.02   422.3  665.14   438.3  661.36
   446.3  660.99   454.3   660.1   466.2  660.88   490.2  660.85   502.2  665.94
   530.2  666.43   554.1  671.22  601.78674.0424  687.83 678.211  758.48682.2859
  776.11682.8489  789.82682.7997  852.51683.4056  883.85682.4824   889.7  682.38
#Mann= 10 ,-1 , 0
       0     .12       0   446.3    .045       0   466.2     .12       0
  601.78     .06       0  687.83     .12       0  758.48     .08       0
  776.11     .06       0  789.82     .08       0  852.51    .016       0
  883.85     .06       0
Bank Sta=446.3,466.2
XS Rating Curve= 0 ,0
Exp/Cntr=0.3,0.1

Type RM Length L Ch R = 1 ,646.3   ,296.7,312.2,325.3
XS GIS Cut Line= 4
     1724507.386      401889.616     1724616.525      402026.214
     1724911.832      402361.645     1725011.658      402539.596
#Sta/Elev= 30
       0  679.36    15.9   678.4    47.7  673.34    63.6  671.84    91.4  670.96
   103.3  669.03   115.2  669.52   139.1  666.72   174.8  666.31   282.6  665.74
   330.5  667.36   382.3  667.69   406.3  665.01   418.2  665.63   422.2  665.24
   434.2  660.36   438.2  658.96   442.2   658.8   454.2  659.06   462.1  661.07
   474.1  664.67     510  665.52     526  666.82   569.9  674.92   585.8  677.26
   609.8  679.36   700.2  683.48   715.9  683.76   766.9  680.92   825.8  680.58
#Mann= 5 ,-1 , 0
       0     .12       0   115.2     .09       0   434.2    .045       0
   462.1     .12       0   569.9     .05       0
#XS Ineff= 2 , 0
       0     350     675               0
Permanent Ineff=
       F       F
Bank Sta=434.2,462.1
XS Rating Curve= 0 ,0
Exp/Cntr=0.3,0.1

Type RM Length L Ch R = 1 ,334.1   ,163.4,135.9,108.9
XS GIS Cut Line= 4
     1724418.989       401793.32     1724451.762      402092.548
     1724518.926      402253.741     1724756.229      402377.955
#Sta/Elev= 30
       0  679.58    15.8  673.34    31.7  668.55    51.5  667.34   130.7  666.97
   227.7 670.267  249.68670.9118   289.1  671.82   332.8  671.62   376.4  670.16
   384.4  668.76   400.2  660.12   404.2  659.12   412.1  657.54     424  657.27
     428  657.31     432  659.05   439.9  664.09   451.8  665.31   487.6  666.98
   511.6  666.27   551.6  667.04   583.6  665.74   603.6  666.27   627.6  668.69
   647.5  672.48   703.5  679.23   715.5  681.73   735.5  688.81   743.5  690.48
#Mann= 7 ,-1 , 0
       0     .12       0    51.5     .05       0   227.7    .045       0
  249.68     .12       0   384.4    .012       0   404.2    .045       0
   647.5     .08       0
#XS Ineff= 2 , 0
       0     305     675     551       0     675
Permanent Ineff=
       F       F
Bank Sta=404.2,432
XS Rating Curve= 0 ,0
Exp/Cntr=0.3,0.1

Type RM Length L Ch R = 1 ,198.2   ,168.8,150.2,131.2
XS GIS Cut Line= 3
       1724267.3      402151.142     1724311.329      402243.198
     1724506.015      402339.944
#Sta/Elev= 30
       0  673.12    31.4  673.19    62.8  674.09    70.6  673.98    82.4   674.8
    98.1  674.26     110   674.7   129.7  673.82   141.6   673.9   145.5   673.2
   149.5  671.09   153.4  668.54   157.4  667.11     185  662.08     189  660.98
  191.85 659.897   196.9  658.12   200.9  657.61   204.8  657.93   208.8  658.67
   212.7  659.86   220.6  662.41   228.5  664.33   240.4  665.21   252.2  667.36
   260.2   667.6   279.9  667.48   291.8  668.37   303.6  667.36   319.4  666.79
#Mann= 3 ,-1 , 0
       0     .12       0  191.85    .045       0   212.7     .12       0
#XS Ineff= 2 , 0
                          292.49          668.88
Permanent Ineff=
       F       F
Bank Sta=191.85,212.7
XS Rating Curve= 0 ,0
Exp/Cntr=0.3,0.1

Type RM Length L Ch R = 1 ,48      ,55,48,40.8
XS GIS Cut Line= 4
     1724332.947      402353.145     1724354.648      402435.611
     1724507.643       402431.27     1724535.855      402374.847
#Sta/Elev= 30
       0  671.62     7.8  671.16    23.3  669.68    27.1  669.11    34.9  666.96
    42.6  664.39    50.4  660.19    54.3  659.13    58.1  658.56   62.75658.3027
    72.7658.1066    81.4  658.06    89.2  658.73    93.1  658.72   136.3   657.6
     152  657.16   155.9  657.29   159.8  658.13   179.5   663.3   187.3  665.88
   191.2  666.77   195.2  667.34   206.9   667.5   218.7  667.12   234.4  667.94
   254.1  667.87     262  667.48   265.9  667.58   289.6  666.09   301.4  666.04
#Mann= 5 ,-1 , 0
       0     .12       0   62.75     .04       0    72.7     .12       0
   136.3    .045       0   159.8     .12       0
#XS Ineff= 2 , 0
       0    89.2  668.04  197.69       0  668.04
Permanent Ineff=
       F       F
Bank Sta=136.3,159.8
XS Rating Curve= 0 ,0
Exp/Cntr=0.3,0.1

Chan Stop Cuts=-1
Use User Specified Reach Order=0
Composite Channel Slope=5